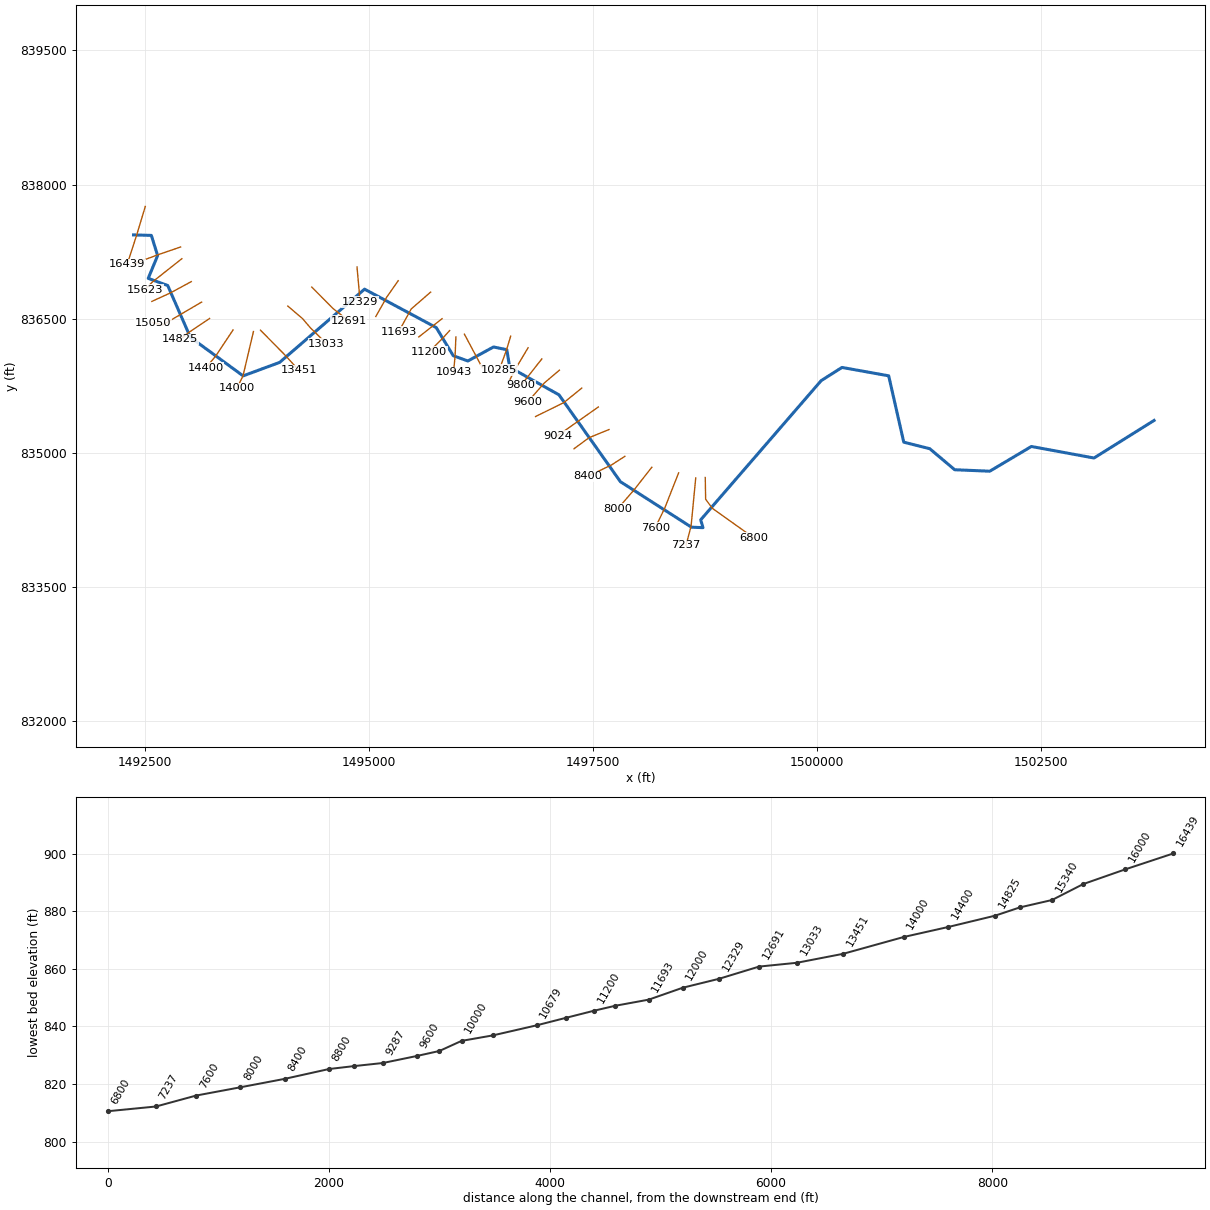
--- Dutchman Creek Tributary 6.prj (project) ---

Proj Title=Dutchman Creek Tributary 6 Limited Detail Study
Current Plan=p01
Default Exp/Contr=0.3,0.1
English Units
Geom File=g01
Flow File=f01
Plan File=p01
Y Axis Title=Elevation
X Axis Title(PF)=Main Channel Distance
X Axis Title(XS)=Station
BEGIN DESCRIPTION:
Dutchman Creek Tributary 6
END DESCRIPTION:
DSS Export Rating Curves= 0
DSS Export Rating Curve Sorted= 0
DSS Export Volume Flow Curves= 0
DXF OffsetX= 0
DXF OffsetY= 0
DXF ScaleX= 1
DXF ScaleY= 10

--- Dutchman Creek Tributary 6.p01 (plan) ---

Plan Title=Floodway Run
Program Version=3.12
Short Identifier=Floodway
Geom File=g01
Flow File=f01
Subcritical Flow
K Sum by GR= 0
Std Step Tol= 0.01
Critical Tol= 0.01
Num of Std Step Trials= 20
Max Error Tol= 0.3
Flow Tol Ratio= 0.001
Split Flow NTrial= 30
Split Flow Tol= 0.02
Split Flow Ratio= 0.02
Log Output Level= 0
Friction Slope Method= 1
Unsteady Friction Slope Method= 2
Unsteady Bridges Friction Slope Method= 1
Parabolic Critical Depth
Global Vel Dist= 0 , 0 , 0
Global Log Level= 0
CheckData=True
Encroach Param=-1 ,5,5, 2
Encroach River=Dutchman Creek T
Encroach Reach=Reach-1
Encroach Node=16439
       1    4960    5007
Encroach Node=16000
       1 4987.74  5014.3
Encroach Node=15623
       1    4993 5021.53
Encroach Node=15340
       1    4993 5027.97
Encroach Node=15050
       1 4986.98    5007
Encroach Node=14825
       1 4990.42 5012.43
Encroach Node=14400
       1 4981.08 5009.89
Encroach Node=14000
       1    4970    5007
Encroach Node=13451
       1    4935    5007
Encroach Node=13033
       1 4957.13 5011.42
Encroach Node=12691
       1 4939.99 5027.41
Encroach Node=12329
       1 4956.45    5014
Encroach Node=12000
       1 4975.79 5030.24
Encroach Node=11693
       1    4993 5089.46
Encroach Node=11391
       1 4977.92 5086.27
Encroach Node=11200
       1    4993 5064.21
Encroach Node=10943
       1 4960.99 5063.65
Encroach Node=10679
       1  4987.5  5027.8
Encroach Node=10285
       1 4983.81 5090.16
Encroach Node=10000
       1  4971.5 5025.81
Encroach Node=9800
       1    4975    5006
Encroach Node=9600
       1  4992.6 5024.85
Encroach Node=9287
       1  4961.9 5010.64
Encroach Node=9024
       1  4974.2 5009.27
Encroach Node=8800
       1 4941.49  5007.4
Encroach Node=8400
       1  4992.6 5099.23
Encroach Node=8000
       1  4992.6 5136.57
Encroach Node=7600
       1 4989.76 5104.39
Encroach Node=7237
       1 4864.38  5083.1
Encroach Node=6800
       1  4990.7  5171.4
Encroach Node=6387
       1 4955.98 5052.86
Encroach Node=6000
       1 4900.56 5086.99
Encroach Node=5600
       1 4964.34 5075.35
Encroach Node=5200
       1 4942.52 5029.14
Encroach Node=4892
       1    4971    5045
Encroach Node=4563
       1    4981    5018
Encroach Node=4443
       1    4985    5020
Encroach Node=4278
       1    4985    5015
Encroach Node=3890
       1    4983    5012
Encroach Node=3600
       1    4921 5013.51
Encroach Node=3200
       1    4847  5009.8
Encroach Node=2800
       1 4885.61  5009.8
Encroach Node=2496
       1 4895.82  5010.1
Encroach Node=2162
       1 4967.69 5087.21
Encroach Node=1887
       1    4960    5040
Encroach Node=1600
       1    4987    5102
Encroach Node=1348
       1  4963.7    5037
Encroach Node=1104
       1 4885.97  5030.1
Encroach Node=929
       1 4851.63  5015.1
Encroach Node=639
       1    4912 5071.02
Encroach Node=359
       1    4935  5020.1
BEGIN DESCRIPTION:
Floodway Run
END DESCRIPTION:
Computation Interval=1HOUR
Output Interval=1HOUR
Run HTab= 0
Run UNet= 0
Run PostProcess= 0
UNET Theta= 1
UNET Theta Warmup= 1
UNET ZTol= 0.02
UNET ZSATol= 0.05
UNET MxIter= 20
UNET MaxInSteps= 0
UNET DtIC= 0
UNET DtMin= 0
UNET MaxCRTS= 20
UNET WFStab= 2
UNET SFStab= 1
UNET WFX= 1
UNET SFX= 1
UNET DSS MLevel= 4
UNET DZMax Abort= 100
UNET Convert EG Bridges=-1
UNET Use Existing IB Tables=-1
UNET Froude Reduction=False
UNET Froude Limit= 1
UNET Froude Power= 10
Instantaneous Interval=1HOUR
Write IC File= 0
Echo Input=False
Echo Output=False
Write Detailed= 0
Detailed Automatic Start=False, 10

--- Dutchman Creek Tributary 6.f01 (steady flow) ---

Flow Title=Floodway
Number of Profiles=2
Profile Names=100-year,100-FW
River Rch & RM= Dutchman Creek T,Reach-1,16439
     642     642
River Rch & RM= Dutchman Creek T,Reach-1,14825
     693     693
River Rch & RM= Dutchman Creek T,Reach-1,13451
     757     757
River Rch & RM= Dutchman Creek T,Reach-1,12691
     822     822
River Rch & RM= Dutchman Creek T,Reach-1,11693
     922     922
River Rch & RM= Dutchman Creek T,Reach-1,10943
     970     970
River Rch & RM= Dutchman Creek T,Reach-1,9600
    1032    1032
River Rch & RM= Dutchman Creek T,Reach-1,6800
    1493    1493
River Rch & RM= Dutchman Creek T,Reach-1,5600
    1617    1617
River Rch & RM= Dutchman Creek T,Reach-1,2496
    1662    1662
Boundary for River Rch & Prof#=Dutchman Creek T,Reach-1,1
Up Type=0
Dn Type=3
Dn Slope=0.0079
Boundary for River Rch & Prof#=Dutchman Creek T,Reach-1,2
Up Type=0
Dn Type=3
Dn Slope=0.0079

--- Dutchman Creek Tributary 6.g01 (geometry) ---

Geom Title=Existing Conditions

River Reach=Dutchman Creek T,Reach-1
Reach XY= 30
      1492369.25       837436.63      1492568.13       837431.44
      1492638.25       837205.63      1492533.13       836951.31
      1492751.13       836870.88      1493004.13       836292.19
      1493593.13       835861.38      1494000.63       836011.94
      1494948.96       836830.53      1495749.90       836400.76
      1495939.50       836086.81      1496102.63       836027.94
      1496389.50       836184.38      1496538.28       836153.78
      1496569.56       835958.68      1497120.50       835649.38
      1497806.88       834678.63      1498599.38       834170.56
      1498728.63       834165.25      1498703.25       834252.56
      1500048.22       835807.96      1500280.64       835955.64
      1500802.51       835862.15      1500970.94       835120.60
      1501261.58       835047.26      1501539.57       834812.33
      1501931.36       834796.09      1502396.01       835072.38
      1503095.50       834943.56      1503766.18       835363.36

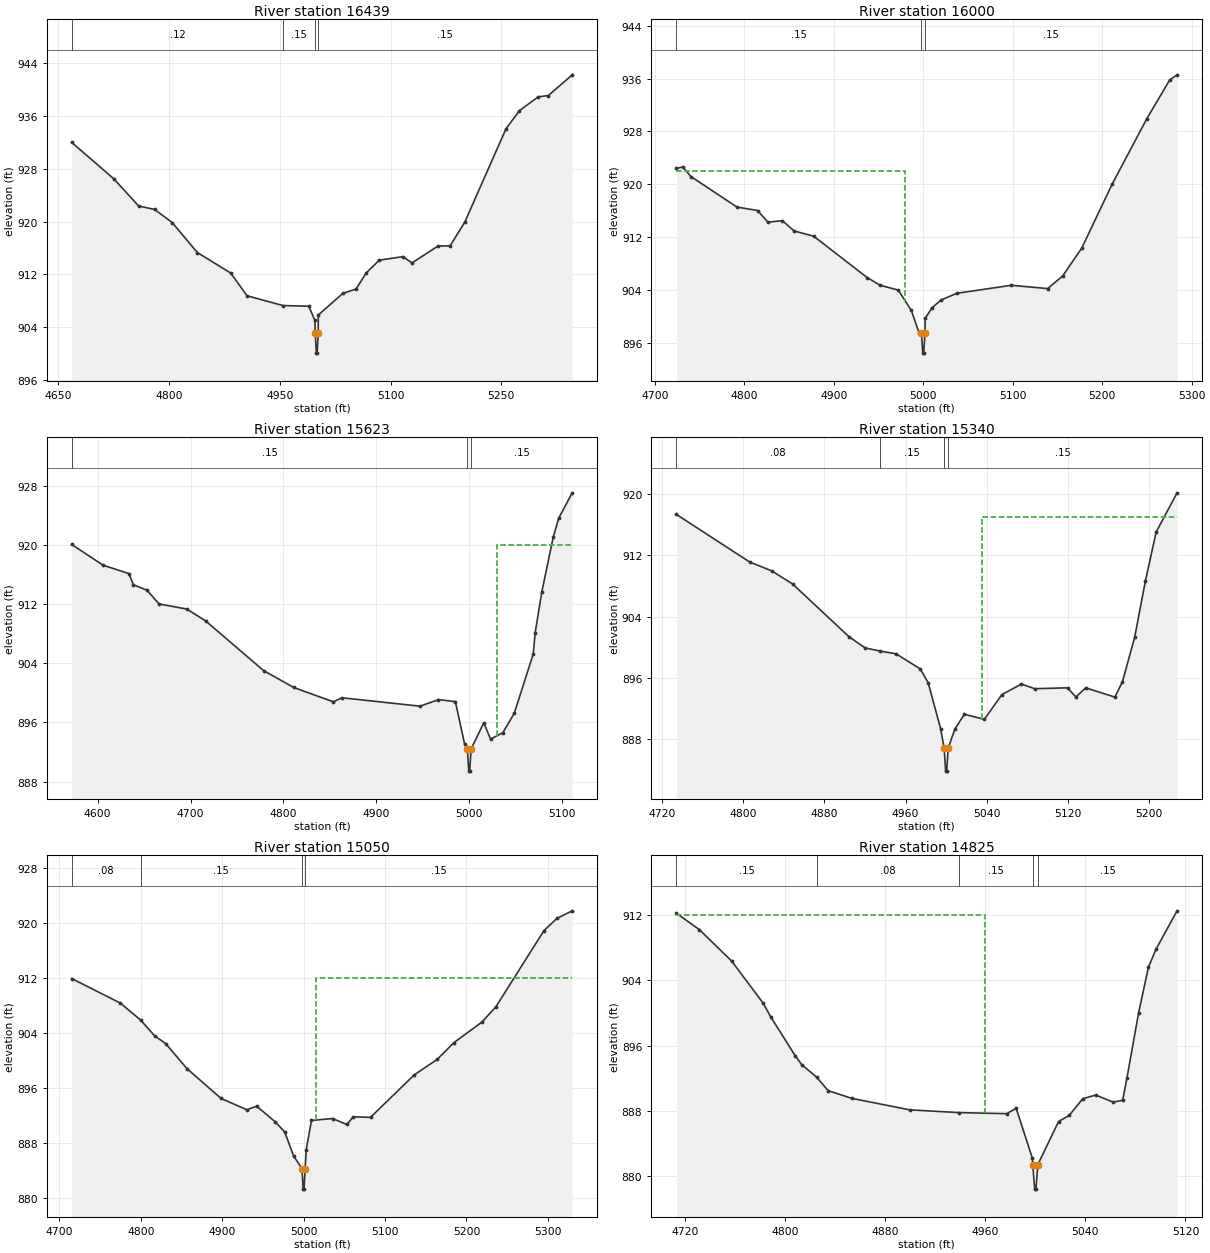
Type RM Length L Ch R = 1,16439,439,439,439
BEGIN DESCRIPTION:
Dutchman Creek Tributary 6 41.0
END DESCRIPTION:
XS GIS Cut Line= 3
      1492500.40       837754.65      1492403.03       837430.97
      1492297.77       837107.27
#Sta/Elev= 30
  4667.9  931.99  4724.9  926.48  4758.6  922.36  4780.3  921.83  4804.1  919.85
  4838.2  915.30  4883.6  912.18  4905.5  908.75  4954.4  907.27  4989.2  907.17
  4997.5  905.01  4998.0  903.06  4999.5  900.06  5000.5  900.06  5002.0  903.06
  5002.1  905.84  5035.6  909.13  5053.3  909.77  5067.2  912.23  5084.8  914.15
  5116.7  914.68  5129.2  913.74  5164.5  916.30  5180.7  916.31  5200.6  919.90
  5256.4  934.03  5274.6  936.79  5300.3  938.90  5313.9  939.09  5346.3  942.23
#Mann=4,-1,0
  4667.9    0.12       0  4954.4    0.15       0  4998.0    0.05       0
  5002.0    0.15       0
Bank Sta=4998,5002
XS Rating Curve= 0
Exp/Cntr=0.3,0.1

Type RM Length L Ch R = 1,16000,377,377,377
BEGIN DESCRIPTION:
Dutchman Creek Tributary 6 40.0
END DESCRIPTION:
XS GIS Cut Line= 3
      1492895.17       837302.00      1492634.35       837212.35
      1492368.80       837112.51
#Sta/Elev= 30
  4724.2  922.41  4731.2  922.64  4740.4  921.18  4791.8  916.57  4814.8  916.05
  4826.4  914.29  4842.6  914.51  4855.6  912.96  4877.6  912.16  4937.4  905.90
  4951.7  904.75  4972.1  904.01  4986.6  900.96  4995.3  897.56  4998.0  897.48
  4999.5  894.48  5000.5  894.48  5002.0  897.48  5002.1  899.72  5010.0  901.37
  5020.1  902.53  5037.6  903.53  5098.5  904.74  5139.1  904.24  5155.8  906.15
  5177.1  910.35  5211.2  920.05  5249.6  929.86  5275.4  935.78  5283.7  936.57
#Mann=3,-1,0
  4724.2    0.15       0  4998.0    0.05       0  5002.0    0.15       0
#XS Ineff=2,0
    0.00 4980.00  922.00               0
Permanent Ineff=
       F       F
Bank Sta=4998,5002
XS Rating Curve= 0
Exp/Cntr=0.3,0.1

Type RM Length L Ch R = 1,15623,283,283,283
BEGIN DESCRIPTION:
Dutchman Creek Tributary 6 39.0
END DESCRIPTION:
XS GIS Cut Line= 3
      1492908.36       837170.44      1492582.00       836912.50
      1492495.15       836825.66
#Sta/Elev= 30
  4572.1  920.06  4605.9  917.25  4633.7  916.12  4638.5  914.61  4653.2  913.87
  4666.2  912.01  4695.9  911.33  4716.4  909.71  4778.7  903.00  4811.1  900.72
  4853.8  898.78  4862.9  899.33  4947.1  898.19  4966.9  899.08  4985.1  898.81
  4995.1  893.03  4998.0  892.41  4999.5  889.41  5000.5  889.41  5002.0  892.41
  5015.7  895.95  5022.9  893.74  5036.2  894.60  5048.5  897.24  5068.9  905.25
  5071.0  908.13  5078.1  913.63  5090.4  921.03  5096.3  923.61  5110.9  927.04
#Mann=3,-1,0
  4572.1    0.15       0  4998.0    0.05       0  5002.0    0.15       0
#XS Ineff=2,0
       0                 5030.00    0.00  920.00
Permanent Ineff=
       F       F
Bank Sta=4998,5002
XS Rating Curve= 0
Exp/Cntr=0.3,0.1

Type RM Length L Ch R = 1,15340,290,290,290
BEGIN DESCRIPTION:
Dutchman Creek Tributary 6 38.0
END DESCRIPTION:
XS GIS Cut Line= 3
      1493014.23       836914.88      1492782.08       836789.04
      1492573.78       836693.57
#Sta/Elev= 30
  4734.3  917.30  4806.4  911.11  4828.0  909.96  4848.7  908.25  4904.2  901.38
  4920.2  899.92  4934.8  899.51  4950.6  899.15  4974.4  897.19  4982.2  895.41
  4994.5  889.42  4998.0  886.87  4999.5  883.87  5000.5  883.87  5002.0  886.87
  5008.6  889.36  5018.0  891.28  5037.6  890.61  5054.9  893.84  5074.1  895.21
  5087.2  894.61  5119.6  894.72  5127.8  893.52  5137.5  894.72  5166.2  893.51
  5173.6  895.48  5185.7  901.28  5196.2  908.57  5206.9  915.01  5227.5  920.12
#Mann=4,-1,0
  4734.3    0.08       0  4934.8    0.15       0  4998.0    0.05       0
  5002.0    0.15       0
#XS Ineff=2,0
       0                 5035.00    0.00  917.00
Permanent Ineff=
       F       F
Bank Sta=4998,5002
XS Rating Curve= 0
Exp/Cntr=0.3,0.1

Type RM Length L Ch R = 1,15050,225,225,225
BEGIN DESCRIPTION:
Dutchman Creek Tributary 6 37.5
END DESCRIPTION:
XS GIS Cut Line= 3
      1493129.42       836686.17      1492695.16       836430.88
      1492587.26       836457.20
#Sta/Elev= 30
  4715.2  911.97  4774.9  908.40  4799.8  905.93  4817.1  903.62  4830.5  902.51
  4856.9  898.84  4898.7  894.51  4930.2  892.87  4942.4  893.38  4965.5  891.08
  4976.9  889.61  4987.7  886.15  4998.0  884.31  4999.5  881.31  5000.5  881.31
  5002.0  884.31  5003.2  887.03  5009.7  891.31  5035.7  891.59  5053.1  890.72
  5061.1  891.84  5082.2  891.76  5136.1  897.96  5164.0  900.19  5184.8  902.65
  5218.9  905.62  5236.1  907.84  5295.2  918.94  5311.1  920.72  5330.0  921.83
#Mann=4,-1,0
  4715.2    0.08       0  4799.8    0.15       0  4998.0    0.05       0
  5002.0    0.15       0
#XS Ineff=2,0
       0                 5015.00    0.00  912.00
Permanent Ineff=
       F       F
Bank Sta=4998,5002
XS Rating Curve= 0
Exp/Cntr=0.3,0.1

Type RM Length L Ch R = 1,14825,425,425,425
BEGIN DESCRIPTION:
Dutchman Creek Tributary 6 37.0
END DESCRIPTION:
XS GIS Cut Line= 3
      1493218.17       836502.67      1492979.51       836342.11
      1492892.76       836270.54
#Sta/Elev= 30
  4713.2  912.21  4731.4  910.22  4757.3  906.36  4782.4  901.22  4788.4  899.55
  4808.0  894.79  4813.2  893.69  4825.3  892.13  4834.4  890.49  4853.2  889.55
  4899.6  888.14  4939.1  887.80  4977.1  887.67  4984.7  888.32  4997.6  882.25
  4998.0  881.43  4999.5  878.43  5000.5  878.43  5002.0  881.43  5018.6  886.71
  5027.1  887.45  5037.9  889.50  5048.3  889.95  5062.1  889.09  5069.8  889.30
  5073.3  892.08  5082.6  900.05  5090.4  905.59  5096.5  907.82  5113.3  912.51
#Mann=5,-1,0
  4713.2    0.15       0  4825.3    0.08       0  4939.1    0.15       0
  4998.0    0.05       0  5002.0    0.15       0
#XS Ineff=2,0
    0.00 4960.00  912.00               0
Permanent Ineff=
       F       F
Bank Sta=4998,5002
XS Rating Curve= 0
Exp/Cntr=0.3,0.1

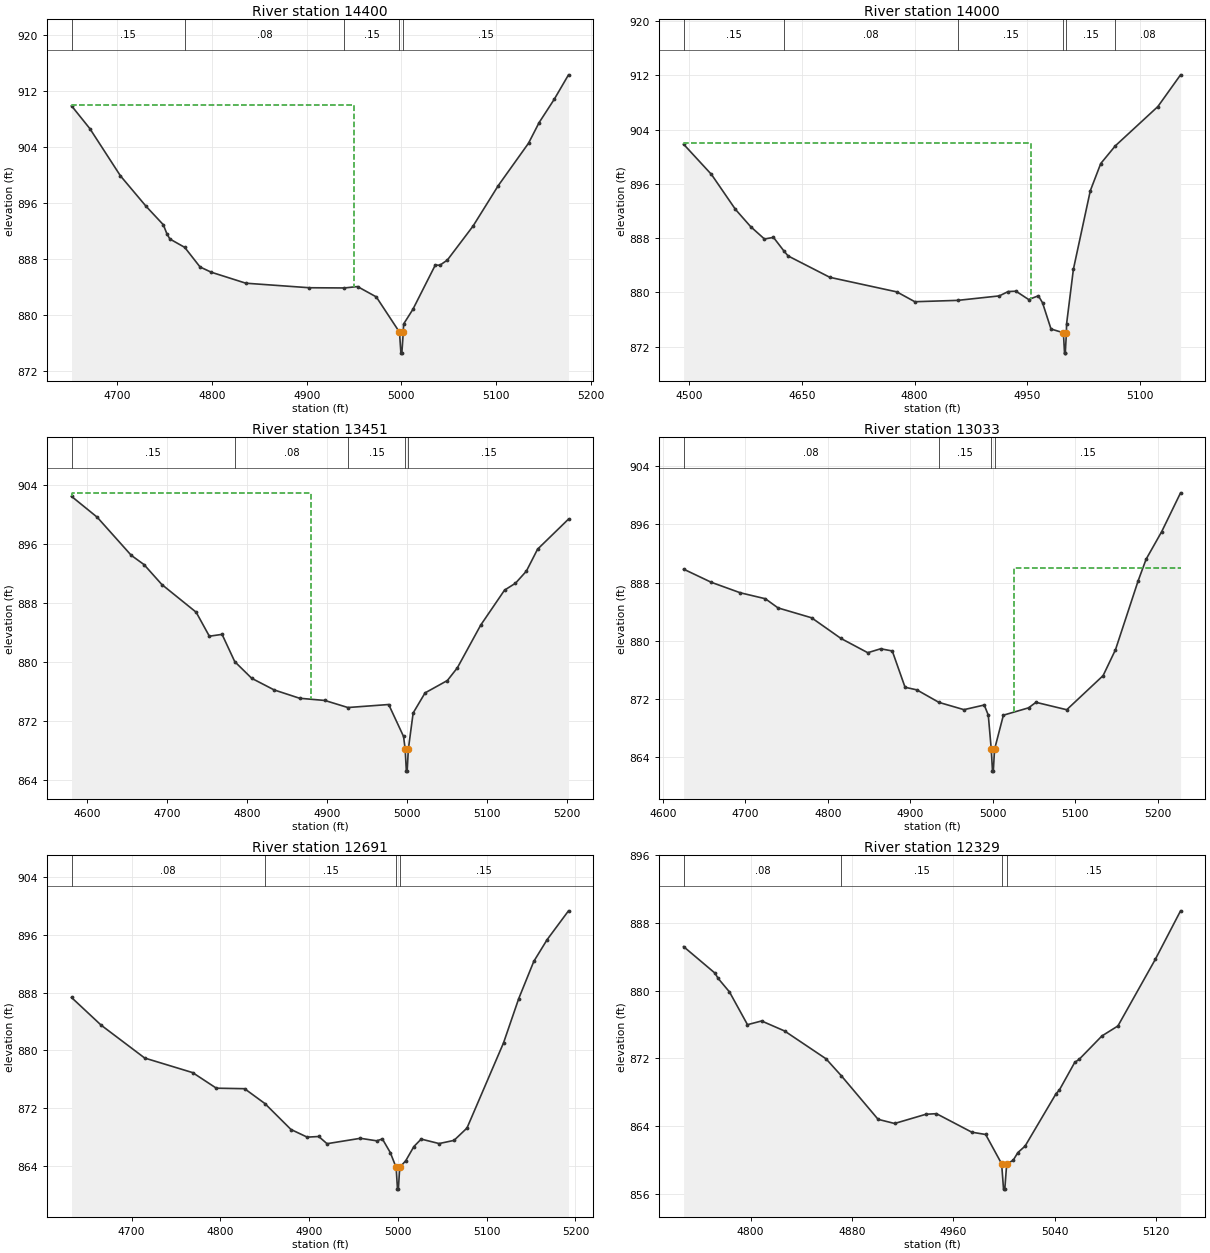
Type RM Length L Ch R = 1,14400,400,400,400
BEGIN DESCRIPTION:
Dutchman Creek Tributary 6 36.0
END DESCRIPTION:
XS GIS Cut Line= 3
      1493480.68       836374.67      1493287.91       836084.70
      1493174.74       835949.39
#Sta/Elev= 30
  4651.8  909.90  4671.2  906.62  4703.5  899.86  4730.5  895.51  4748.7  892.87
  4752.4  891.60  4755.6  890.83  4771.3  889.63  4787.5  886.82  4799.4  886.07
  4835.8  884.50  4902.9  883.85  4939.9  883.82  4953.7  884.02  4973.5  882.54
  4998.0  877.49  4999.5  874.49  5000.5  874.49  5002.0  877.49  5002.3  878.65
  5012.1  880.75  5035.8  887.10  5040.6  887.07  5048.5  887.81  5075.6  892.67
  5102.3  898.48  5134.2  904.54  5145.4  907.50  5161.3  910.82  5176.4  914.33
#Mann=5,-1,0
  4651.8    0.15       0  4771.3    0.08       0  4939.9    0.15       0
  4998.0    0.05       0  5002.0    0.15       0
#XS Ineff=2,0
    0.00 4950.00  910.00               0
Permanent Ineff=
       F       F
Bank Sta=4998,5002
XS Rating Curve= 0
Exp/Cntr=0.3,0.1

Type RM Length L Ch R = 1,14000,549,549,549
BEGIN DESCRIPTION:
Dutchman Creek Tributary 6 35.0
END DESCRIPTION:
XS GIS Cut Line= 3
      1493708.48       836357.31      1493592.16       835863.42
      1493524.98       835724.96
#Sta/Elev= 30
  4492.6  901.85  4529.7  897.39  4561.6  892.24  4581.8  889.70  4600.2  887.87
  4612.2  888.11  4626.5  886.05  4631.7  885.37  4687.2  882.22  4776.4  880.07
  4800.3  878.62  4857.5  878.82  4912.7  879.48  4924.5  880.12  4934.9  880.17
  4951.8  878.94  4964.7  879.50  4970.2  878.47  4981.5  874.60  4998.0  874.04
  4999.5  871.04  5000.5  871.04  5002.0  874.04  5002.2  875.32  5011.3  883.41
  5033.8  894.99  5047.7  899.00  5067.1  901.61  5123.7  907.40  5153.9  912.08
#Mann=6,-1,0
  4492.6    0.15       0  4626.5    0.08       0  4857.5    0.15       0
  4998.0    0.05       0  5002.0    0.15       0  5067.1    0.08       0
#XS Ineff=2,0
    0.00 4955.00  902.00               0
Permanent Ineff=
       F       F
Bank Sta=4998,5002
XS Rating Curve= 0
Exp/Cntr=0.3,0.1

Type RM Length L Ch R = 1,13451,418,418,418
BEGIN DESCRIPTION:
Dutchman Creek Tributary 6 34.0
END DESCRIPTION:
XS GIS Cut Line= 3
      1493786.56       836372.50      1494062.11       836092.62
      1494216.15       835923.39
#Sta/Elev= 30
  4580.7  902.52  4612.8  899.69  4655.4  894.51  4671.4  893.25  4693.7  890.54
  4736.6  886.78  4753.1  883.52  4769.0  883.77  4784.9  880.06  4806.1  877.80
  4834.2  876.22  4866.0  875.09  4897.6  874.79  4926.4  873.83  4977.4  874.24
  4996.0  869.90  4998.0  868.19  4999.5  865.19  5000.5  865.19  5002.0  868.19
  5008.0  873.09  5022.9  875.82  5050.8  877.50  5063.3  879.23  5092.5  885.03
  5122.3  889.78  5136.0  890.72  5149.6  892.36  5163.6  895.34  5202.3  899.43
#Mann=5,-1,0
  4580.7    0.15       0  4784.9    0.08       0  4926.4    0.15       0
  4998.0    0.05       0  5002.0    0.15       0
#XS Ineff=2,0
    0.00 4880.00  903.00               0
Permanent Ineff=
       F       F
Bank Sta=4998,5002
XS Rating Curve= 0
Exp/Cntr=0.3,0.1

Type RM Length L Ch R = 1,13033,342,342,342
BEGIN DESCRIPTION:
Dutchman Creek Tributary 6 33.0
END DESCRIPTION:
XS GIS Cut Line= 4
      1494092.49       836641.50      1494257.37       836500.49
      1494344.15       836398.52      1494524.25       836222.76
#Sta/Elev= 30
  4625.0  889.85  4658.6  888.04  4693.7  886.60  4724.1  885.78  4739.5  884.52
  4780.2  883.16  4815.8  880.32  4848.3  878.36  4863.9  878.90  4878.0  878.60
  4893.5  873.61  4907.8  873.25  4934.6  871.53  4964.9  870.53  4989.5  871.17
  4994.4  869.78  4998.0  865.08  4999.5  862.08  5000.5  862.08  5002.0  865.08
  5012.7  869.77  5043.2  870.78  5052.2  871.54  5089.5  870.52  5133.6  875.21
  5148.6  878.77  5176.0  888.22  5185.7  891.21  5204.6  895.00  5227.5  900.34
#Mann=4,-1,0
  4625.0    0.08       0  4934.6    0.15       0  4998.0    0.05       0
  5002.0    0.15       0
#XS Ineff=2,0
       0                 5025.00    0.00  890.00
Permanent Ineff=
       F       F
Bank Sta=4998,5002
XS Rating Curve= 0
Exp/Cntr=0.3,0.1

Type RM Length L Ch R = 1,12691,362,362,362
BEGIN DESCRIPTION:
Dutchman Creek Tributary 6 32.0
END DESCRIPTION:
XS GIS Cut Line= 3
      1494359.32       836854.14      1494597.99       836613.31
      1494771.56       836476.62
#Sta/Elev= 30
  4632.2  887.34  4665.6  883.50  4714.7  878.94  4768.7  876.92  4795.4  874.76
  4827.2  874.69  4850.1  872.63  4879.5  869.03  4897.8  867.97  4910.8  868.06
  4920.1  867.06  4957.7  867.81  4976.1  867.46  4982.5  867.72  4991.4  865.83
  4998.0  863.76  4999.5  860.76  5000.5  860.76  5002.0  863.76  5008.9  864.72
  5018.0  866.67  5026.2  867.70  5046.4  867.08  5063.2  867.52  5077.8  869.23
  5119.0  881.05  5136.1  887.18  5153.1  892.35  5168.1  895.36  5192.2  899.36
#Mann=4,-1,0
  4632.2    0.08       0  4850.1    0.15       0  4998.0    0.05       0
  5002.0    0.15       0
Bank Sta=4998,5002
XS Rating Curve= 0
Exp/Cntr=0.3,0.1

Type RM Length L Ch R = 1,12329,329,329,329
BEGIN DESCRIPTION:
Dutchman Creek Tributary 6 31.0
END DESCRIPTION:
XS GIS Cut Line= 3
      1494864.83       837077.63      1494888.70       836815.07
      1494897.38       836687.11
#Sta/Elev= 30
  4747.2  885.19  4772.0  882.05  4774.4  881.44  4783.4  879.83  4797.6  875.96
  4808.7  876.40  4826.8  875.22  4859.5  871.93  4871.6  869.92  4900.6  864.77
  4913.6  864.28  4938.3  865.37  4946.6  865.44  4974.5  863.25  4985.4  862.98
  4998.0  859.52  4999.5  856.52  5000.5  856.52  5002.0  859.52  5007.0  859.91
  5010.8  860.84  5016.5  861.61  5040.9  867.80  5043.5  868.23  5055.6  871.49
  5059.3  871.89  5077.1  874.63  5089.7  875.81  5119.2  883.69  5139.1  889.42
#Mann=4,-1,0
  4747.2    0.08       0  4871.6    0.15       0  4998.0    0.05       0
  5002.0    0.15       0
Bank Sta=4998,5002
XS Rating Curve= 0
Exp/Cntr=0.3,0.1

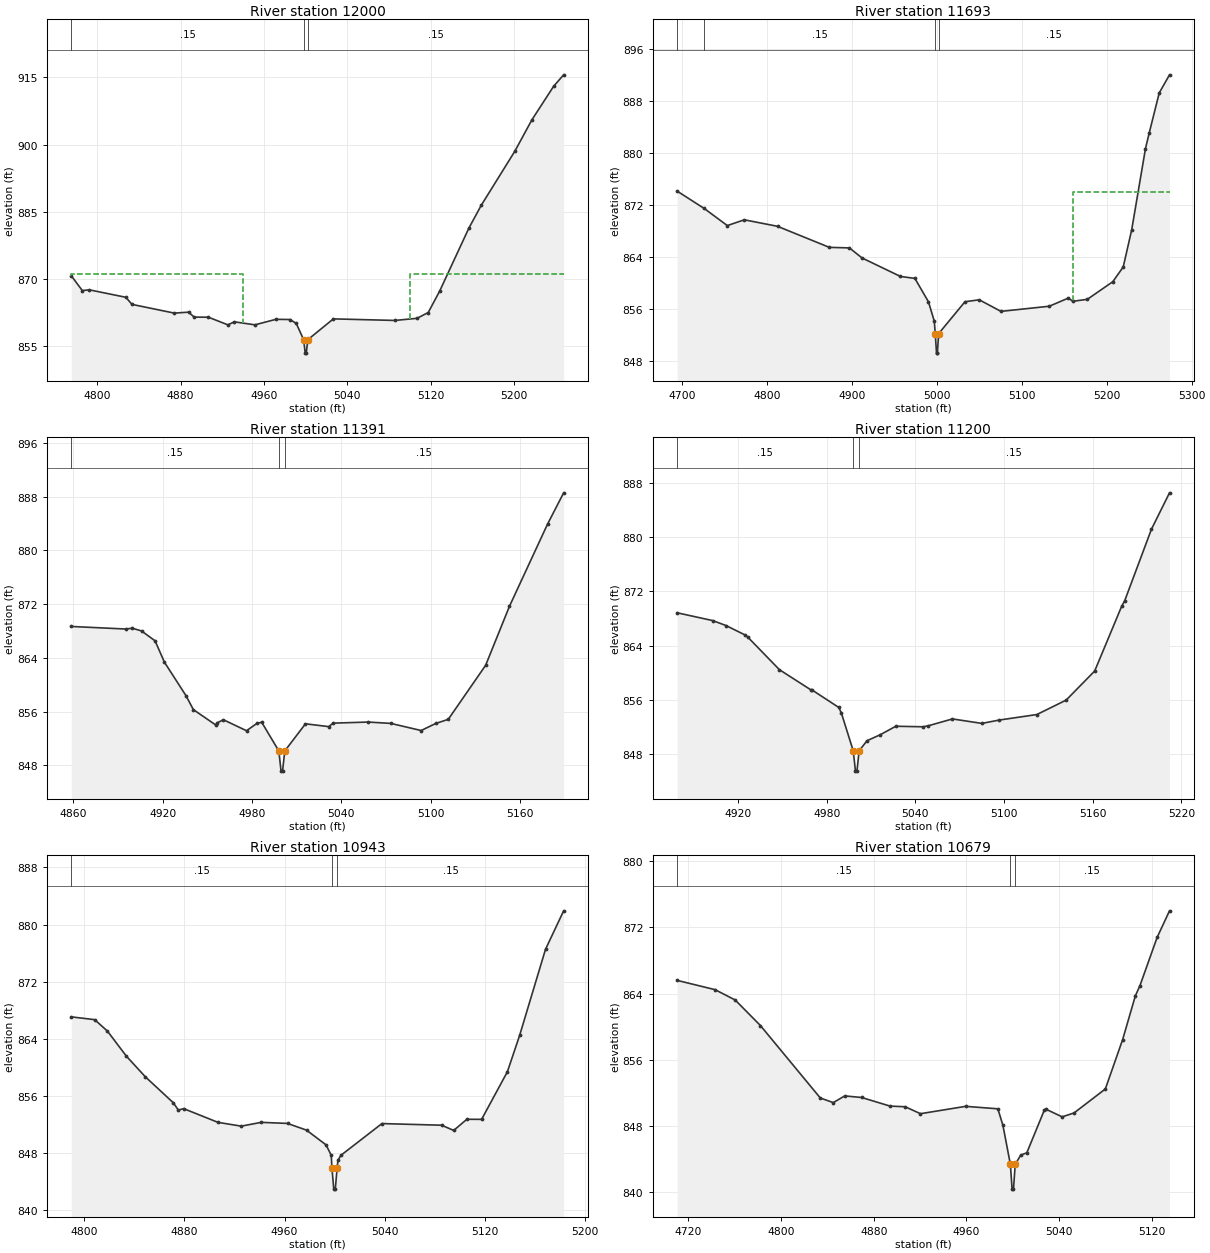
Type RM Length L Ch R = 1,12000,307,307,307
BEGIN DESCRIPTION:
Dutchman Creek Tributary 6 30.0
END DESCRIPTION:
XS GIS Cut Line= 3
      1495325.00       836925.01      1495196.35       836740.54
      1495074.98       836524.96
#Sta/Elev= 30
  4775.1  870.69  4785.7  867.38  4792.4  867.55  4827.5  865.88  4833.3  864.30
  4873.9  862.35  4887.6  862.56  4893.0  861.46  4906.7  861.43  4925.3  859.73
  4931.6  860.40  4951.2  859.73  4971.4  860.96  4984.9  860.92  4990.9  860.05
  4998.0  856.41  4999.5  853.41  5000.5  853.41  5002.0  856.41  5026.5  861.06
  5085.6  860.71  5106.8  861.19  5117.5  862.48  5128.4  867.23  5156.5  881.34
  5168.5  886.49  5200.6  898.52  5216.8  905.47  5237.8  913.02  5247.4  915.58
#Mann=3,-1,0
  4775.1    0.15       0  4998.0    0.05       0  5002.0    0.15       0
#XS Ineff=2,0
    0.00 4940.00  871.00 5100.00    0.00  871.00
Permanent Ineff=
       F       F
Bank Sta=4998,5002
XS Rating Curve= 0
Exp/Cntr=0.3,0.1

Type RM Length L Ch R = 1,11693,302,302,302
BEGIN DESCRIPTION:
Dutchman Creek Tributary 6 29.0
END DESCRIPTION:
XS GIS Cut Line= 3
      1495687.13       836797.74      1495470.14       836608.97
      1495329.11       836352.95
#Sta/Elev= 30
  4694.0  874.19  4725.8  871.53  4753.1  868.89  4773.1  869.78  4812.2  868.78
  4873.3  865.54  4896.9  865.46  4911.8  863.91  4957.0  861.07  4974.0  860.77
  4990.0  857.17  4996.9  854.18  4998.0  852.28  4999.5  849.28  5000.5  849.28
  5002.0  852.28  5033.0  857.18  5049.8  857.48  5075.4  855.70  5132.3  856.49
  5154.9  857.75  5160.0  857.25  5177.1  857.55  5207.1  860.26  5219.4  862.53
  5229.4  868.26  5245.6  880.73  5249.9  883.07  5261.8  889.29  5273.9  892.07
#Mann=4,-1,0
  4694.0     0.1       0  4725.8    0.15       0  4998.0    0.05       0
  5002.0    0.15       0
#XS Ineff=2,0
       0                 5160.00    0.00  874.00
Permanent Ineff=
       F       F
Bank Sta=4998,5002
XS Rating Curve= 0
Exp/Cntr=0.3,0.1

Type RM Length L Ch R = 1,11391,191,191,191
BEGIN DESCRIPTION:
Dutchman Creek Tributary 6 28.5
END DESCRIPTION:
XS GIS Cut Line= 2
      1495815.10       836500.49      1495554.76       836296.56
#Sta/Elev= 30
  4858.6  868.68  4895.1  868.30  4899.6  868.42  4905.8  868.01  4914.9  866.54
  4921.1  863.39  4935.6  858.40  4940.6  856.31  4955.8  854.00  4956.4  854.33
  4960.8  854.80  4976.3  853.17  4983.3  854.26  4986.5  854.43  4998.0  850.16
  4999.5  847.16  5000.5  847.16  5002.0  850.16  5015.9  854.20  5031.5  853.78
  5034.5  854.30  5058.1  854.46  5073.2  854.26  5093.6  853.20  5103.5  854.26
  5111.8  854.86  5136.9  862.90  5152.9  871.68  5178.5  883.91  5189.3  888.56
#Mann=3,-1,0
  4858.6    0.15       0  4998.0    0.05       0  5002.0    0.15       0
Bank Sta=4998,5002
XS Rating Curve= 0
Exp/Cntr=0.3,0.1

Type RM Length L Ch R = 1,11200,257,257,257
BEGIN DESCRIPTION:
Dutchman Creek Tributary 6 28.0
END DESCRIPTION:
XS GIS Cut Line= 3
      1495899.68       836368.11      1495818.47       836278.28
      1495667.58       836129.51
#Sta/Elev= 29
  4878.9  868.84  4903.1  867.68  4912.0  866.95  4924.6  865.59  4926.7  865.24
  4948.1  860.43  4969.1  857.49  4970.4  857.40  4988.2  854.86  4989.9  854.08
  4998.0  848.45  4999.5  845.45  5000.5  845.45  5002.0  848.45  5007.3  849.94
  5016.2  850.82  5026.8  852.08  5045.3  852.00  5048.6  852.14  5065.1  853.16
  5085.0  852.50  5096.6  852.99  5122.2  853.81  5142.0  855.94  5161.3  860.24
  5179.6  869.83  5181.6  870.62  5199.7  881.19  5211.9  886.56
#Mann=3,-1,0
  4878.9    0.15       0  4998.0    0.05       0  5002.0    0.15       0
Bank Sta=4998,5002
XS Rating Curve= 0
Exp/Cntr=0.3,0.1

Type RM Length L Ch R = 1,10943,264,264,264
BEGIN DESCRIPTION:
Dutchman Creek Tributary 6 27.0
END DESCRIPTION:
XS GIS Cut Line= 3
      1495969.13       836296.53      1495960.46       836086.11
      1495943.10       835903.83
#Sta/Elev= 30
  4789.5  867.07  4808.2  866.68  4818.4  865.08  4833.5  861.58  4848.7  858.68
  4871.1  855.04  4875.1  854.02  4879.4  854.22  4906.8  852.30  4925.4  851.77
  4941.4  852.30  4962.4  852.15  4977.6  851.21  4993.2  849.15  4997.4  847.68
  4997.9  845.95  4999.4  842.95  5000.6  842.95  5002.1  845.95  5002.7  846.96
  5005.0  847.67  5037.9  852.13  5085.6  851.90  5095.3  851.17  5105.8  852.73
  5117.6  852.72  5138.2  859.38  5148.0  864.47  5168.7  876.53  5183.2  881.92
#Mann=3,-1,0
  4789.5    0.15       0  4997.9    0.05       0  5002.1    0.15       0
Bank Sta=4997.9,5002.1
XS Rating Curve= 0
Exp/Cntr=0.3,0.1

Type RM Length L Ch R = 1,10679,394,394,394
BEGIN DESCRIPTION:
Dutchman Creek Tributary 6 26.5
END DESCRIPTION:
XS GIS Cut Line= 2
      1496064.61       836326.91      1496264.20       835951.58
#Sta/Elev= 30
  4710.2  865.60  4742.9  864.48  4760.3  863.23  4782.1  860.14  4833.8  851.38
  4845.0  850.82  4854.9  851.63  4869.5  851.44  4894.0  850.40  4907.1  850.32
  4920.3  849.48  4959.3  850.37  4987.1  850.07  4991.5  848.06  4997.9  843.36
  4999.4  840.36  5000.6  840.36  5002.1  843.36  5006.9  844.48  5012.1  844.75
  5027.1  849.87  5028.4  850.04  5042.6  849.10  5052.9  849.57  5079.9  852.47
  5094.8  858.42  5105.8  863.72  5109.8  864.97  5124.6  870.79  5135.3  874.01
#Mann=3,-1,0
  4710.2    0.15       0  4997.9    0.05       0  5002.1    0.15       0
Bank Sta=4997.9,5002.1
XS Rating Curve= 0
Exp/Cntr=0.3,0.1

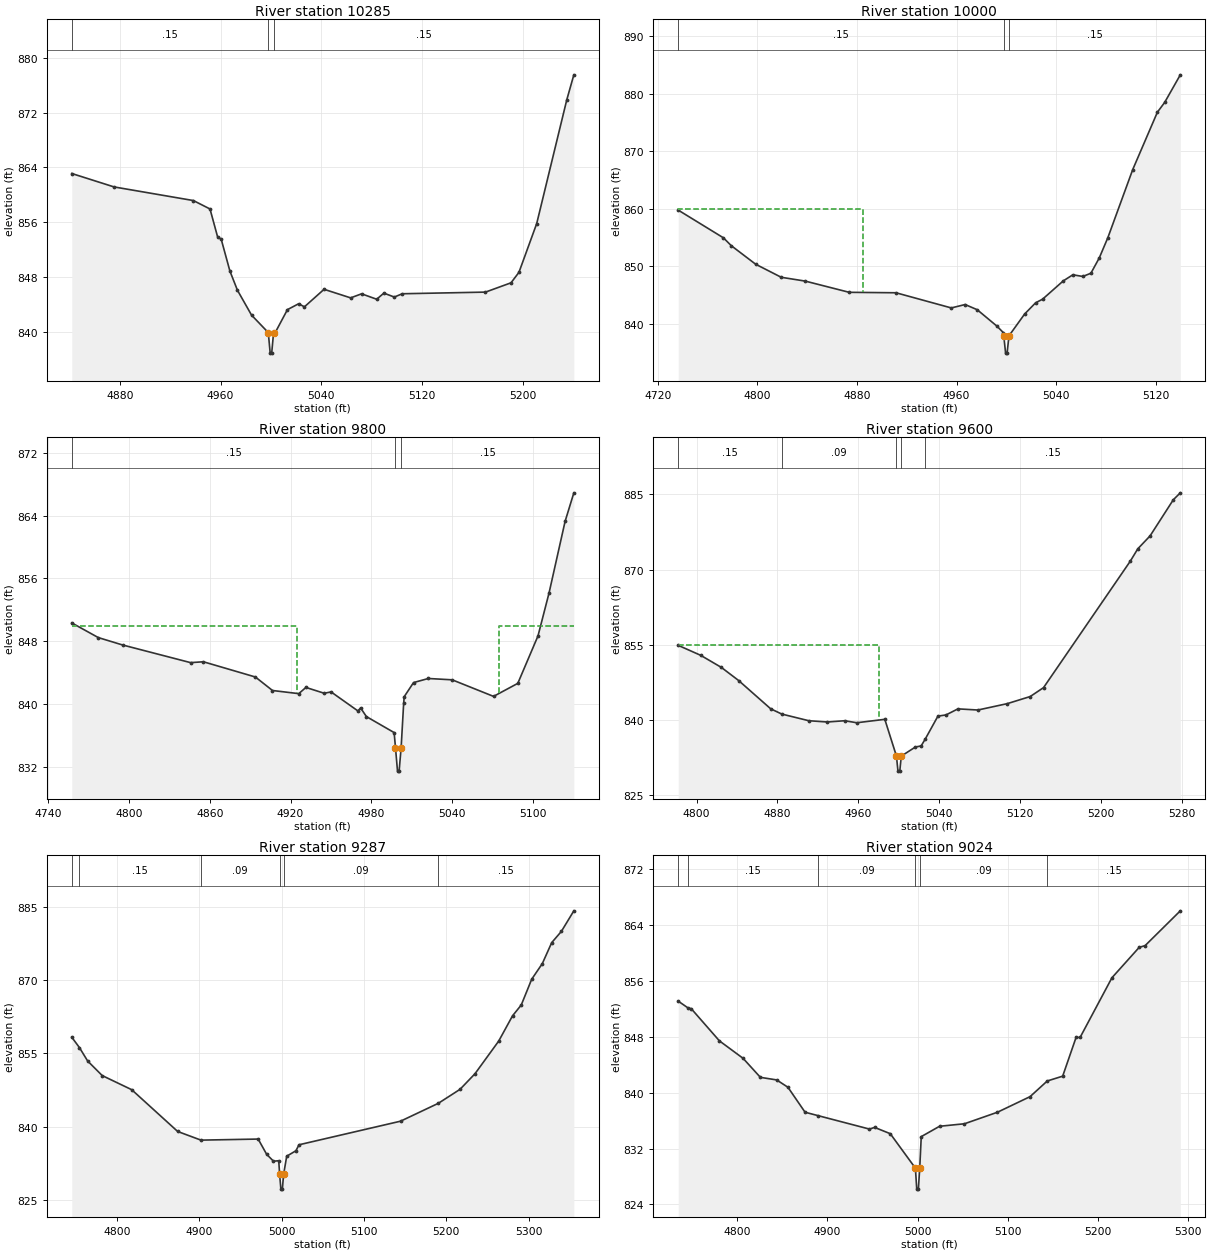
Type RM Length L Ch R = 1,10285,285,285,285
BEGIN DESCRIPTION:
Dutchman Creek Tributary 6 26.0
END DESCRIPTION:
XS GIS Cut Line= 3
      1496580.95       836305.25      1496533.22       836146.85
      1496452.94       835927.73
#Sta/Elev= 30
  4841.8  863.11  4875.4  861.15  4938.4  859.16  4951.6  857.93  4957.6  853.88
  4960.5  853.51  4967.4  848.87  4973.4  846.06  4984.6  842.43  4997.9  839.88
  4999.4  836.88  5000.6  836.88  5002.1  839.88  5003.4  839.88  5013.1  843.23
  5022.0  844.09  5026.6  843.64  5042.2  846.20  5063.3  844.95  5072.0  845.54
  5084.0  844.75  5089.7  845.64  5098.0  845.07  5104.3  845.55  5170.4  845.79
  5190.7  847.15  5197.0  848.68  5211.1  855.80  5235.0  873.88  5240.6  877.52
#Mann=3,-1,0
  4841.8    0.15       0  4997.9    0.05       0  5002.1    0.15       0
Bank Sta=4997.9,5002.1
XS Rating Curve= 0
Exp/Cntr=0.3,0.1

Type RM Length L Ch R = 1,10000,200,200,200
BEGIN DESCRIPTION:
Dutchman Creek Tributary 6 25.0
END DESCRIPTION:
XS GIS Cut Line= 3
      1496774.98       836174.96      1496639.74       835948.81
      1496575.01       835825.01
#Sta/Elev= 30
  4736.5  859.77  4772.8  854.96  4779.1  853.60  4798.7  850.38  4819.2  848.12
  4838.6  847.45  4873.8  845.51  4911.4  845.43  4955.8  842.80  4966.9  843.39
  4976.6  842.49  4992.5  839.63  4997.6  838.51  4997.9  837.96  4999.4  834.96
  5000.6  834.96  5002.1  837.96  5014.7  841.75  5023.5  843.69  5029.1  844.32
  5045.7  847.49  5053.4  848.55  5061.4  848.26  5067.9  848.82  5074.6  851.47
  5081.5  854.98  5101.5  866.81  5121.3  876.76  5127.1  878.44  5139.7  883.24
#Mann=3,-1,0
  4736.5    0.15       0  4997.9    0.05       0  5002.1    0.15       0
#XS Ineff=2,0
    0.00 4885.00  860.00               0
Permanent Ineff=
       F       F
Bank Sta=4997.9,5002.1
XS Rating Curve= 0
Exp/Cntr=0.3,0.1

Type RM Length L Ch R = 1,9800,200,200,200
BEGIN DESCRIPTION:
Dutchman Creek Tributary 6 24.5
END DESCRIPTION:
XS GIS Cut Line= 2
      1496928.63       836050.69      1496698.26       835757.72
#Sta/Elev= 30
  4757.6  850.34  4777.3  848.47  4795.3  847.53  4845.8  845.28  4855.3  845.39
  4893.9  843.45  4906.6  841.73  4926.1  841.33  4931.4  842.12  4945.0  841.38
  4950.1  841.55  4970.0  839.13  4972.0  839.51  4976.3  838.41  4996.9  836.37
  4997.9  834.46  4999.4  831.46  5000.6  831.46  5002.1  834.46  5004.0  840.18
  5004.4  840.95  5011.3  842.74  5022.3  843.26  5040.0  843.09  5070.7  840.98
  5088.7  842.64  5103.7  848.69  5111.9  854.16  5123.8  863.27  5130.3  866.91
#Mann=3,-1,0
  4757.6    0.15       0  4997.9    0.05       0  5002.1    0.15       0
#XS Ineff=2,0
    0.00 4925.00  850.00 5075.00    0.00  850.00
Permanent Ineff=
       F       F
Bank Sta=4997.9,5002.1
XS Rating Curve= 0
Exp/Cntr=0.3,0.1

Type RM Length L Ch R = 1,9600,313,313,313
BEGIN DESCRIPTION:
Dutchman Creek Tributary 6 24.0
END DESCRIPTION:
XS GIS Cut Line= 3
      1497125.00       835925.00      1496958.58       835784.04
      1496775.01       835575.01
#Sta/Elev= 30
  4781.9  854.86  4804.1  852.87  4824.5  850.46  4841.6  847.84  4873.3  842.19
  4884.3  841.14  4911.0  839.81  4929.3  839.56  4946.4  839.81  4958.4  839.41
  4986.1  840.09  4997.6  832.75  4999.1  829.75  5000.9  829.75  5002.4  832.75
  5016.3  834.56  5022.0  834.78  5025.9  836.09  5038.6  840.73  5046.6  840.97
  5058.4  842.18  5078.1  841.95  5107.1  843.22  5129.8  844.64  5143.0  846.42
  5228.7  871.65  5236.2  874.14  5248.3  876.71  5271.3  883.93  5278.2  885.31
#Mann=5,-1,0
  4781.9    0.15       0  4884.3    0.09       0  4997.6    0.05       0
  5002.4    0.09       0  5025.9    0.15       0
#XS Ineff=2,0
    0.00 4980.00  855.00               0
Permanent Ineff=
       F       F
Bank Sta=4997.6,5002.4
XS Rating Curve= 0
Exp/Cntr=0.3,0.1

Type RM Length L Ch R = 1,9287,263,263,263
BEGIN DESCRIPTION:
Dutchman Creek Tributary 6 23.0
END DESCRIPTION:
XS GIS Cut Line= 3
      1497374.98       835724.98      1497175.40       835563.25
      1496858.61       835407.02
#Sta/Elev= 30
  4745.0  858.31  4754.3  856.19  4764.3  853.45  4782.0  850.47  4817.8  847.59
  4873.7  839.05  4902.0  837.28  4971.5  837.50  4981.8  834.39  4990.1  832.98
  4996.5  833.07  4997.6  830.27  4999.1  827.27  5000.9  827.27  5002.4  830.27
  5006.2  834.00  5017.4  835.11  5021.1  836.33  5144.5  841.15  5190.4  844.80
  5216.8  847.66  5234.9  850.83  5263.8  857.52  5280.6  862.68  5291.2  864.89
  5303.9  870.16  5316.8  873.35  5328.2  877.63  5340.0  879.94  5355.1  884.13
#Mann=6,-1,0
  4745.0    0.09       0  4754.3    0.15       0  4902.0    0.09       0
  4997.6    0.05       0  5002.4    0.09       0  5190.4    0.15       0
Bank Sta=4997.6,5002.4
XS Rating Curve= 0
Exp/Cntr=0.3,0.1

Type RM Length L Ch R = 1,9024,224,224,224
BEGIN DESCRIPTION:
Dutchman Creek Tributary 6 22.5
END DESCRIPTION:
XS GIS Cut Line= 2
      1497559.45       835513.37      1497103.83       835192.27
#Sta/Elev= 30
  4734.3  853.08  4745.5  852.08  4748.7  852.01  4780.0  847.40  4806.3  844.90
  4825.5  842.18  4843.6  841.81  4856.1  840.76  4875.1  837.19  4889.9  836.69
  4946.6  834.78  4952.3  835.02  4969.7  834.12  4997.6  829.19  4999.1  826.19
  5000.9  826.19  5002.4  829.19  5004.1  833.70  5024.4  835.18  5052.1  835.54
  5088.7  837.19  5124.9  839.42  5144.0  841.66  5161.1  842.35  5176.0  847.90
  5180.4  847.88  5215.8  856.43  5246.1  860.78  5252.6  861.02  5291.7  866.00
#Mann=6,-1,0
  4734.3    0.09       0  4745.5    0.15       0  4889.9    0.09       0
  4997.6    0.05       0  5002.4    0.09       0  5144.0    0.15       0
Bank Sta=4997.6,5002.4
XS Rating Curve= 0
Exp/Cntr=0.3,0.1

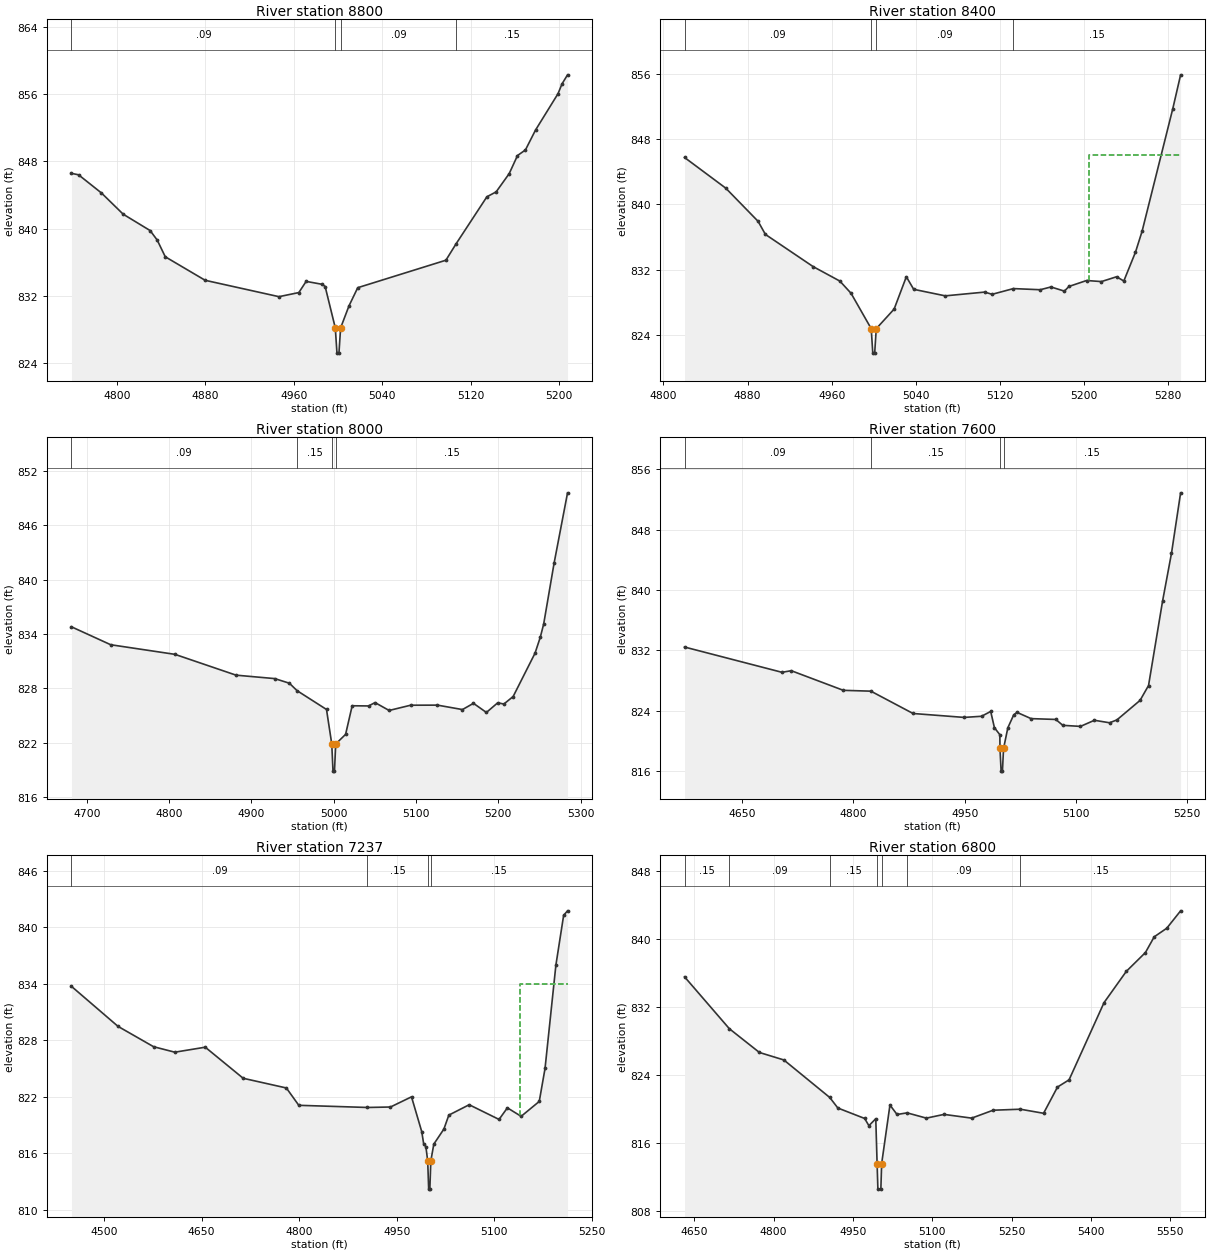
Type RM Length L Ch R = 1,8800,400,400,400
BEGIN DESCRIPTION:
Dutchman Creek Tributary 6 22.0
END DESCRIPTION:
XS GIS Cut Line= 3
      1497678.71       835261.67      1497455.56       835170.12
      1497288.23       835046.91
#Sta/Elev= 30
  4758.8  846.58  4765.2  846.41  4785.9  844.25  4805.6  841.72  4830.0  839.77
  4836.4  838.64  4843.7  836.65  4879.8  833.85  4946.6  831.90  4964.6  832.39
  4971.2  833.72  4985.8  833.37  4988.4  833.11  4997.6  828.18  4999.1  825.18
  5000.9  825.18  5002.4  828.18  5010.0  830.81  5017.9  832.97  5097.7  836.24
  5107.0  838.21  5134.8  843.79  5143.2  844.38  5155.0  846.55  5162.5  848.70
  5169.7  849.37  5178.8  851.73  5199.2  856.07  5202.8  857.23  5207.8  858.31
#Mann=4,-1,0
  4758.8    0.09       0  4997.6    0.05       0  5002.4    0.09       0
  5107.0    0.15       0
Bank Sta=4997.6,5002.4
XS Rating Curve= 0
Exp/Cntr=0.3,0.1

Type RM Length L Ch R = 1,8400,400,400,400
BEGIN DESCRIPTION:
Dutchman Creek Tributary 6 21.0
END DESCRIPTION:
XS GIS Cut Line= 3
      1497856.65       834962.29      1497705.29       834865.05
      1497442.22       834738.80
#Sta/Elev= 30
  4820.1  845.75  4859.3  841.99  4890.0  837.93  4897.0  836.32  4942.3  832.38
  4967.8  830.60  4978.4  829.11  4997.6  824.77  4999.1  821.77  5000.9  821.77
  5002.4  824.77  5019.4  827.17  5031.0  831.13  5038.0  829.59  5068.0  828.79
  5105.4  829.25  5112.6  828.98  5132.8  829.68  5158.3  829.54  5168.5  829.88
  5181.3  829.37  5185.6  829.94  5202.4  830.67  5216.5  830.54  5230.9  831.13
  5237.8  830.61  5248.9  834.15  5255.2  836.72  5284.4  851.75  5291.8  855.88
#Mann=4,-1,0
  4820.1    0.09       0  4997.6    0.05       0  5002.4    0.09       0
  5132.8    0.15       0
#XS Ineff=2,0
       0                 5205.00    0.00  846.00
Permanent Ineff=
       F       F
Bank Sta=4997.6,5002.4
XS Rating Curve= 0
Exp/Cntr=0.3,0.1

Type RM Length L Ch R = 1,8000,400,400,400
BEGIN DESCRIPTION:
Dutchman Creek Tributary 6 20.0
END DESCRIPTION:
XS GIS Cut Line= 3
      1498157.36       834840.82      1497960.94       834589.85
      1497775.02       834375.03
#Sta/Elev= 30
  4681.3  834.79  4729.0  832.81  4807.0  831.75  4881.3  829.45  4928.3  829.07
  4946.1  828.56  4955.4  827.74  4991.2  825.66  4997.6  821.85  4999.1  818.85
  5000.9  818.85  5002.4  821.85  5014.4  822.91  5022.4  826.07  5042.3  826.05
  5050.2  826.42  5067.3  825.55  5093.4  826.13  5126.0  826.14  5156.4  825.65
  5169.8  826.34  5185.5  825.33  5199.3  826.40  5206.7  826.26  5218.0  827.09
  5244.6  831.88  5251.0  833.64  5255.1  835.10  5267.7  841.79  5284.1  849.59
#Mann=4,-1,0
  4681.3    0.09       0  4955.4    0.15       0  4997.6    0.05       0
  5002.4    0.15       0
Bank Sta=4997.6,5002.4
XS Rating Curve= 0
Exp/Cntr=0.3,0.1

Type RM Length L Ch R = 1,7600,363,363,363
BEGIN DESCRIPTION:
Dutchman Creek Tributary 6 19.0
END DESCRIPTION:
XS GIS Cut Line= 3
      1498456.72       834777.85      1498300.08       834380.29
      1498194.22       834163.90
#Sta/Elev= 30
  4572.7  832.43  4703.9  829.08  4716.5  829.29  4786.6  826.69  4823.7  826.58
  4880.5  823.62  4949.3  823.10  4972.7  823.25  4985.1  823.89  4990.1  821.74
  4997.4  820.81  4997.6  818.98  4999.1  815.98  5000.9  815.98  5002.4  818.98
  5008.2  821.73  5016.1  823.44  5020.5  823.77  5039.5  822.94  5072.8  822.83
  5082.2  822.05  5106.0  821.91  5124.8  822.72  5145.2  822.39  5155.1  822.77
  5186.3  825.36  5197.7  827.33  5216.6  838.52  5228.6  844.85  5240.9  852.87
#Mann=4,-1,0
  4572.7    0.09       0  4823.7    0.15       0  4997.6    0.05       0
  5002.4    0.15       0
Bank Sta=4997.6,5002.4
XS Rating Curve= 0
Exp/Cntr=0.3,0.1

Type RM Length L Ch R = 1,7237,437,437,437
BEGIN DESCRIPTION:
Dutchman Creek Tributary 6 18.0
END DESCRIPTION:
XS GIS Cut Line= 3
      1498647.65       834721.47      1498595.58       834181.25
      1498539.17       833968.63
#Sta/Elev= 30
  4449.9  833.71  4521.5  829.46  4576.2  827.30  4608.8  826.72  4655.6  827.25
  4713.9  823.95  4780.3  822.92  4799.4  821.08  4905.0  820.85  4940.4  820.90
  4972.7  821.98  4988.5  818.27  4991.4  816.99  4994.8  816.69  4997.6  815.18
  4999.1  812.18  5000.9  812.18  5002.4  815.18  5007.0  816.96  5022.5  818.56
  5030.1  820.04  5061.4  821.14  5107.3  819.58  5120.1  820.81  5141.3  819.91
  5169.1  821.49  5178.0  824.99  5194.7  835.97  5206.6  841.25  5212.6  841.73
#Mann=4,-1,0
  4449.9    0.09       0  4905.0    0.15       0  4997.6    0.05       0
  5002.4    0.15       0
#XS Ineff=2,0
       0                 5140.00    0.00  834.00
Permanent Ineff=
       F       F
Bank Sta=4997.6,5002.4
XS Rating Curve= 0
Exp/Cntr=0.3,0.1

Type RM Length L Ch R = 1,6800,413,413,413
BEGIN DESCRIPTION:
Dutchman Creek Tributary 6 17.0
END DESCRIPTION:
XS GIS Cut Line= 4
      1498753.96       834725.75      1498758.30       834482.82
      1498832.58       834381.75      1499296.36       834051.07
#Sta/Elev= 30
  4631.6  835.53  4716.3  829.42  4773.2  826.62  4819.4  825.74  4906.2  821.32
  4921.5  820.08  4972.2  818.85  4980.2  818.00  4993.2  818.82  4995.7  813.53
  4997.2  810.53  5002.8  810.53  5004.3  813.53  5020.0  820.43  5033.4  819.32
  5052.5  819.51  5088.9  818.89  5122.3  819.33  5174.5  818.89  5215.0  819.82
  5266.6  819.94  5310.5  819.46  5336.8  822.55  5358.7  823.40  5424.8  832.49
  5466.9  836.17  5503.1  838.39  5519.7  840.24  5543.4  841.25  5569.6  843.30
#Mann=7,-1,0
  4631.6    0.15       0  4716.3    0.09       0  4906.2    0.15       0
  4995.7    0.05       0  5004.3    0.15       0  5052.5    0.09       0
  5266.6    0.15       0
Bank Sta=4995.7,5004.3
XS Rating Curve= 0
Exp/Cntr=0.3,0.1