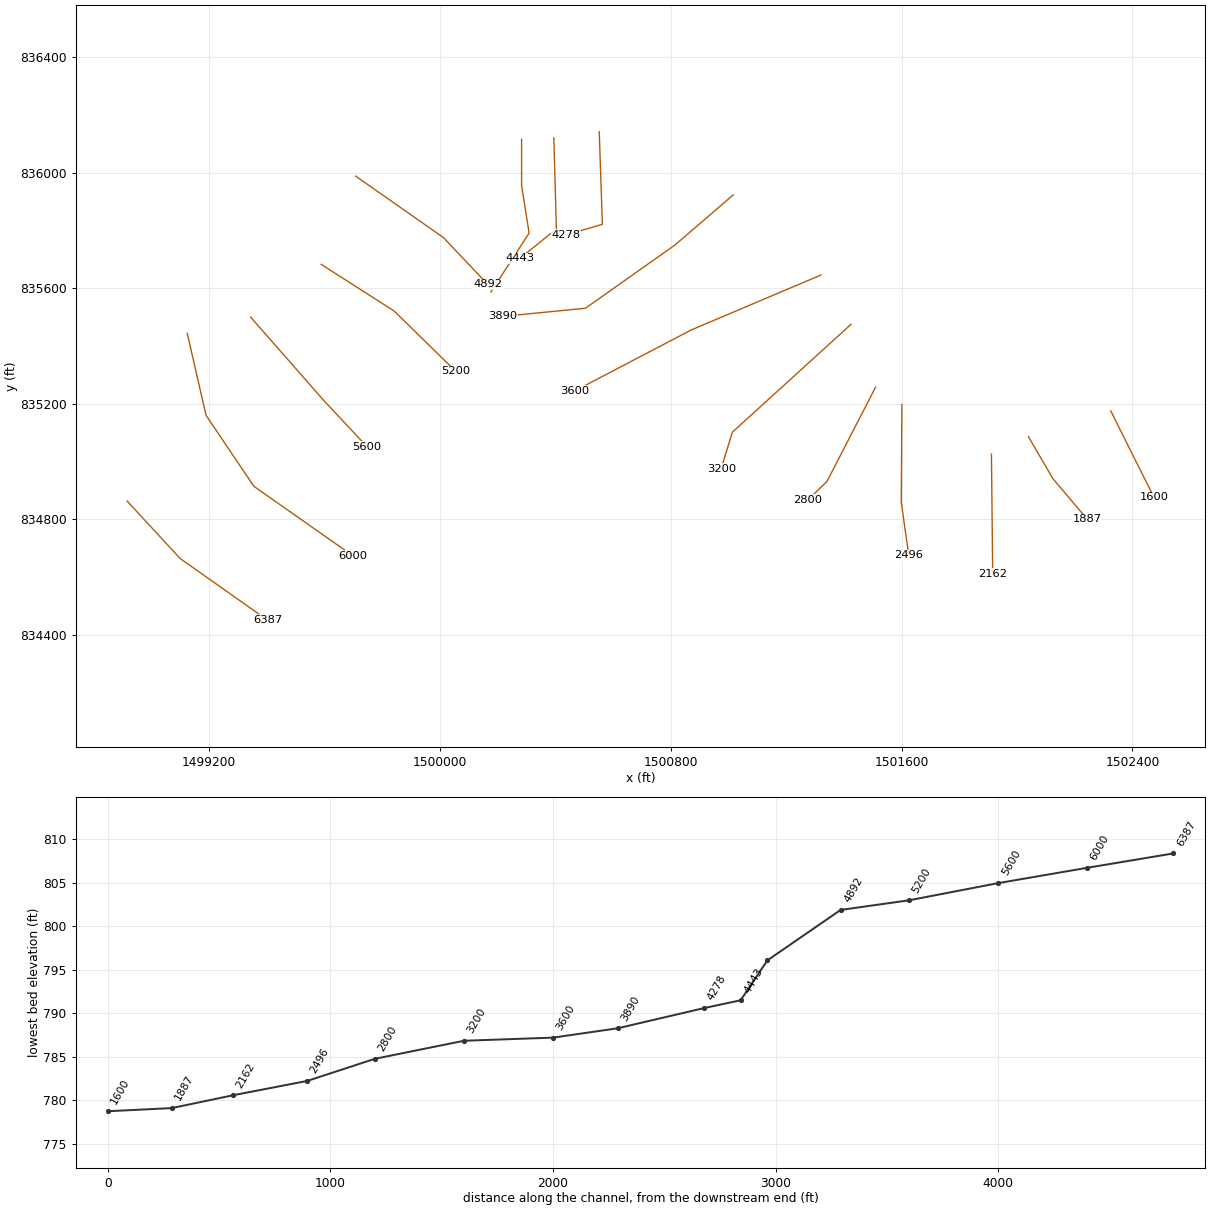
HEC-RAS study Dutchman Creek Tributary 6.prj: Dutchman Creek Tributary 6 Limited Detail Study

--- Dutchman Creek Tributary 6.g01 (geometry) --- (continued)

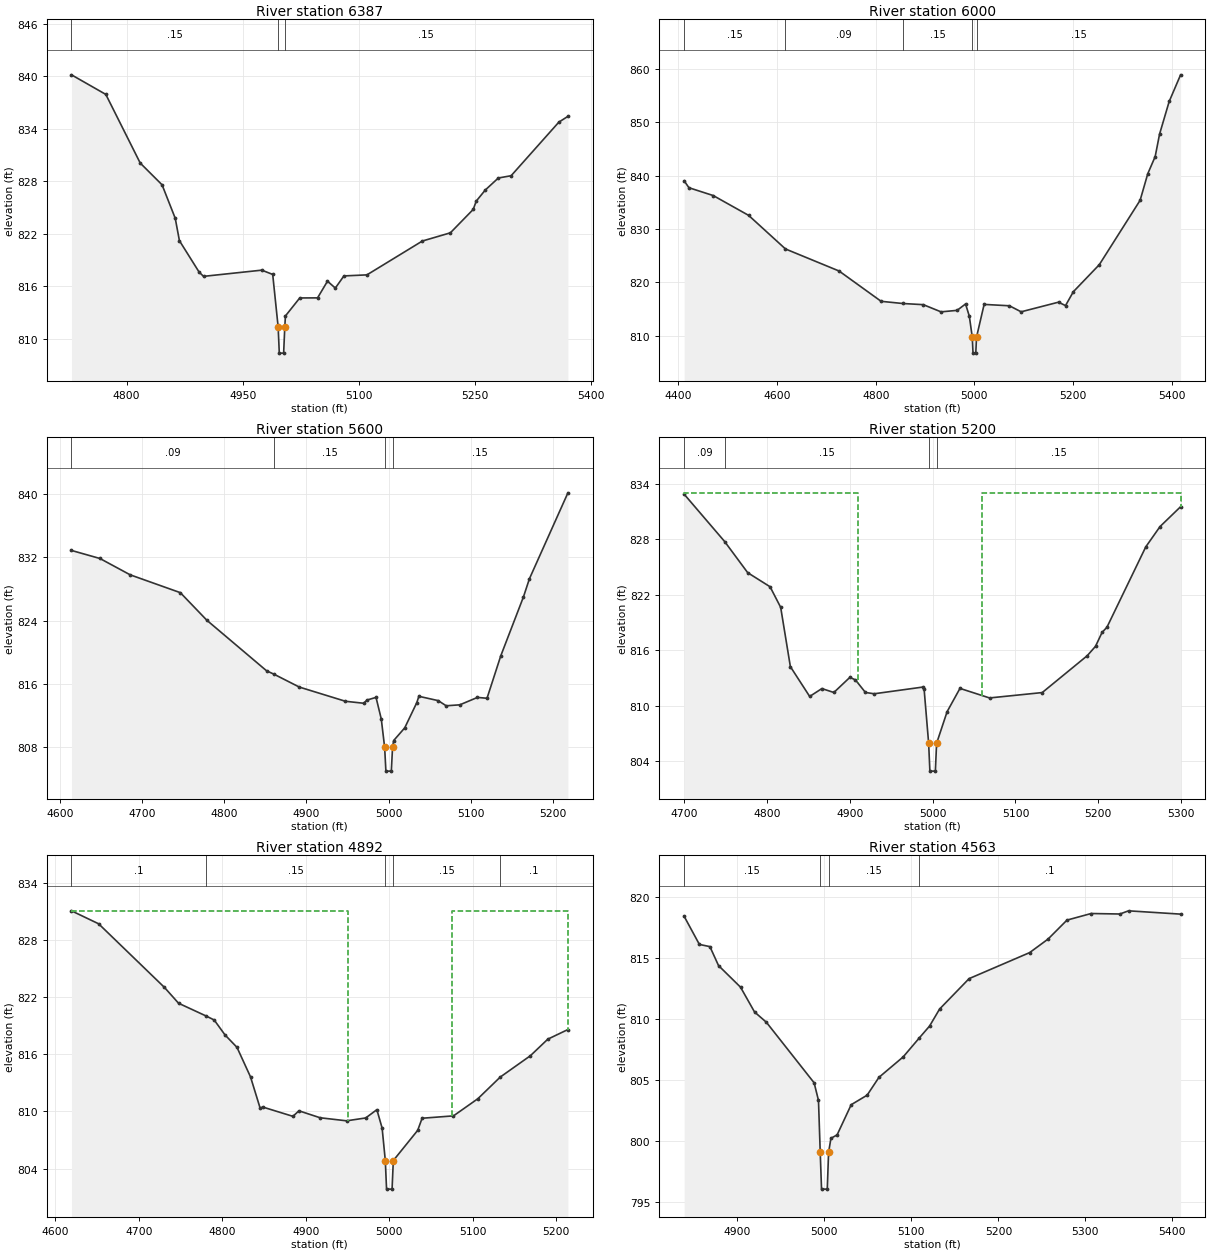
Type RM Length L Ch R = 1,6387,387,387,387
BEGIN DESCRIPTION:
Dutchman Creek Tributary 6 16.0
END DESCRIPTION:
XS GIS Cut Line= 3
      1498916.66       834862.50      1499101.09       834662.89
      1499402.61       834450.30
#Sta/Elev= 30
  4729.0  840.17  4773.3  837.93  4817.7  830.08  4845.9  827.59  4862.9  823.76
  4868.3  821.20  4893.7  817.61  4899.4  817.12  4974.6  817.83  4988.7  817.34
  4995.7  811.34  4997.2  808.34  5002.8  808.34  5004.3  811.34  5005.1  812.59
  5023.6  814.65  5046.6  814.66  5059.4  816.57  5069.5  815.78  5080.6  817.17
  5110.3  817.29  5181.8  821.16  5218.0  822.10  5247.5  824.78  5251.4  825.73
  5263.1  827.00  5279.9  828.37  5296.4  828.63  5358.0  834.76  5369.7  835.42
#Mann=3,-1,0
  4729.0    0.15       0  4995.7    0.05       0  5004.3    0.15       0
Bank Sta=4995.7,5004.3
XS Rating Curve= 0
Exp/Cntr=0.3,0.1

Type RM Length L Ch R = 1,6000,400,400,400
BEGIN DESCRIPTION:
Dutchman Creek Tributary 6 15.0
END DESCRIPTION:
XS GIS Cut Line= 4
      1499124.96       835443.88      1499190.04       835159.71
      1499355.75       834913.75      1499697.72       834673.73
#Sta/Elev= 30
  4411.9  839.04  4421.6  837.75  4470.8  836.28  4542.5  832.56  4617.2  826.25
  4725.8  822.11  4811.0  816.42  4854.6  816.01  4896.5  815.79  4932.4  814.44
  4964.9  814.72  4982.1  815.92  4989.7  813.63  4995.7  809.69  4997.2  806.69
  5002.8  806.69  5004.3  809.69  5019.7  815.84  5071.0  815.58  5094.7  814.45
  5170.5  816.26  5184.6  815.61  5200.5  818.22  5253.1  823.30  5335.8  835.39
  5351.3  840.38  5366.3  843.60  5375.2  847.82  5394.7  853.95  5417.8  858.95
#Mann=5,-1,0
  4411.9    0.15       0  4617.2    0.09       0  4854.6    0.15       0
  4995.7    0.05       0  5004.3    0.15       0
Bank Sta=4995.7,5004.3
XS Rating Curve= 0
Exp/Cntr=0.3,0.1

Type RM Length L Ch R = 1,5600,400,400,400
BEGIN DESCRIPTION:
Dutchman Creek Tributary 6 14.0
END DESCRIPTION:
XS GIS Cut Line= 3
      1499344.07       835500.34      1499598.56       835210.51
      1499747.58       835051.27
#Sta/Elev= 30
  4614.3  832.89  4648.9  831.87  4685.7  829.80  4746.7  827.54  4779.0  824.04
  4851.6  817.64  4860.8  817.20  4891.4  815.58  4947.5  813.78  4969.6  813.53
  4973.8  813.94  4984.7  814.27  4991.1  811.53  4995.2  807.93  4996.7  804.93
  5003.3  804.93  5004.8  807.93  5006.2  808.81  5019.6  810.41  5034.3  813.61
  5036.8  814.41  5060.4  813.86  5070.0  813.21  5086.6  813.33  5108.1  814.27
  5119.7  814.16  5136.4  819.53  5164.0  827.00  5171.3  829.31  5218.1  840.19
#Mann=4,-1,0
  4614.3    0.09       0  4860.8    0.15       0  4995.2    0.05       0
  5004.8    0.15       0
Bank Sta=4995.2,5004.8
XS Rating Curve= 0
Exp/Cntr=0.3,0.1

Type RM Length L Ch R = 1,5200,308,308,308
BEGIN DESCRIPTION:
Dutchman Creek Tributary 6 13.0
END DESCRIPTION:
XS GIS Cut Line= 3
      1499589.23       835682.57      1499841.95       835521.09
      1500055.69       835311.58
#Sta/Elev= 30
  4700.1  832.85  4749.0  827.74  4776.8  824.38  4803.8  822.86  4816.6  820.64
  4828.3  814.24  4851.6  811.02  4866.3  811.87  4880.8  811.45  4900.1  813.08
  4906.8  812.81  4918.9  811.45  4929.5  811.31  4987.9  812.03  4989.7  811.84
  4995.2  805.96  4996.7  802.96  5003.3  802.96  5004.8  805.96  5017.5  809.38
  5033.0  811.89  5068.7  810.86  5132.3  811.44  5186.5  815.41  5196.6  816.43
  5204.5  817.93  5210.4  818.49  5257.3  827.17  5274.5  829.36  5299.3  831.50
#Mann=4,-1,0
  4700.1    0.09       0  4749.0    0.15       0  4995.2    0.05       0
  5004.8    0.15       0
#XS Ineff=2,0
    0.00 4910.00  833.00 5060.00    0.00  833.00
Permanent Ineff=
       F       F
Bank Sta=4995.2,5004.8
XS Rating Curve= 0
Exp/Cntr=0.3,0.1

Type RM Length L Ch R = 1,4892,329,329,329
BEGIN DESCRIPTION:
Dutchman Creek Tributary 6 12.0
END DESCRIPTION:
XS GIS Cut Line= 3
      1499708.56       835988.48      1500012.29       835775.86
      1500166.32       835613.16
#Sta/Elev= 30
  4619.2  831.06  4651.7  829.70  4730.6  823.02  4747.5  821.36  4780.8  820.01
  4790.2  819.60  4803.1  818.04  4817.5  816.73  4833.7  813.63  4845.3  810.33
  4848.2  810.47  4884.5  809.49  4891.7  810.07  4917.1  809.34  4948.8  809.02
  4971.7  809.32  4985.1  810.19  4991.4  808.25  4995.2  804.85  4996.7  801.85
  5003.3  801.85  5004.8  804.85  5034.0  808.02  5039.3  809.29  5076.9  809.54
  5106.1  811.34  5132.9  813.61  5169.0  815.85  5189.9  817.59  5214.0  818.60
#Mann=5,-1,0
  4619.2     0.1       0  4780.8    0.15       0  4995.2    0.05       0
  5004.8    0.15       0  5132.9     0.1       0
#XS Ineff=2,0
    0.00 4950.00  831.00 5075.00    0.00  831.00
Permanent Ineff=
       F       F
Bank Sta=4995.2,5004.8
XS Rating Curve= 0
Exp/Cntr=0.3,0.1

Type RM Length L Ch R = 1,4563,120,120,120
BEGIN DESCRIPTION:
Dutchman Creek Tributary 6 11.0
END DESCRIPTION:
XS GIS Cut Line= 4
      1500283.49       836116.51      1500283.49       835955.93
      1500309.52       835791.05      1500177.19       835587.12
#Sta/Elev= 30
  4838.8  818.39  4856.3  816.09  4868.4  815.91  4878.3  814.36  4903.6  812.59
  4919.7  810.56  4933.3  809.72  4988.2  804.76  4993.2  803.32  4995.2  799.06
  4996.7  796.06  5003.3  796.06  5004.8  799.06  5007.5  800.22  5014.6  800.50
  5030.8  802.97  5049.1  803.75  5062.7  805.21  5090.5  806.88  5109.0  808.43
  5120.9  809.41  5132.4  810.80  5166.3  813.29  5235.9  815.42  5257.1  816.53
  5278.8  818.08  5306.6  818.62  5339.6  818.58  5349.6  818.84  5409.4  818.57
#Mann=4,-1,0
  4838.8    0.15       0  4995.2    0.05       0  5004.8    0.15       0
  5109.0     0.1       0
Bank Sta=4995.2,5004.8
XS Rating Curve= 0
Exp/Cntr=0.3,0.1

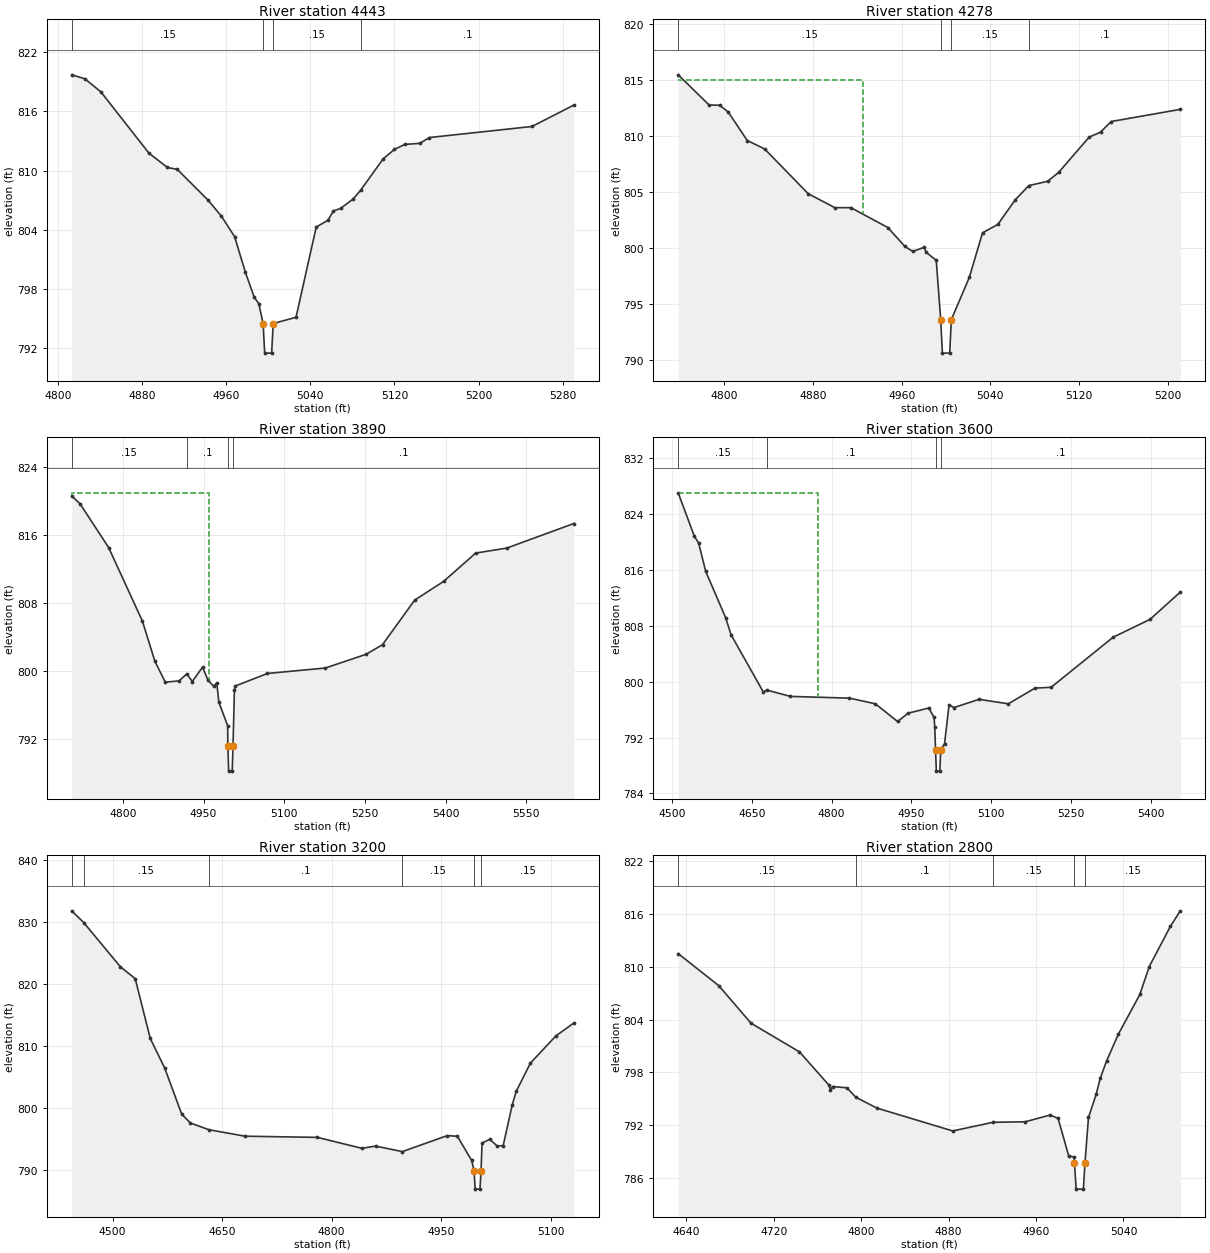
Type RM Length L Ch R = 1,4443,165,165,165
BEGIN DESCRIPTION:
Dutchman Creek Tributary 6 10.75
END DESCRIPTION:
XS GIS Cut Line= 3
      1500395.20       836120.96      1500404.03       835805.40
      1500278.26       835703.90
#Sta/Elev= 30
  4813.3  819.71  4825.7  819.31  4841.0  817.98  4886.7  811.76  4904.3  810.31
  4913.6  810.12  4942.6  807.03  4955.4  805.39  4968.1  803.30  4978.4  799.66
  4986.8  797.14  4991.1  796.50  4995.2  794.48  4996.7  791.48  5003.3  791.48
  5004.8  794.48  5026.5  795.12  5045.7  804.27  5056.9  804.96  5062.0  805.90
  5068.9  806.16  5081.1  807.14  5088.0  808.02  5109.3  811.18  5120.1  812.15
  5129.9  812.65  5144.2  812.76  5153.3  813.35  5250.8  814.47  5290.6  816.64
#Mann=4,-1,0
  4813.3    0.15       0  4995.2    0.05       0  5004.8    0.15       0
  5088.0     0.1       0
Bank Sta=4995.2,5004.8
XS Rating Curve= 0
Exp/Cntr=0.3,0.1

Type RM Length L Ch R = 1,4278,388,388,388
BEGIN DESCRIPTION:
Dutchman Creek Tributary 6 10.5
END DESCRIPTION:
XS GIS Cut Line= 3
      1500552.51       836142.52      1500563.36       835821.42
      1500437.54       835784.54
#Sta/Elev= 30
  4758.7  815.49  4786.5  812.79  4795.9  812.77  4803.7  812.17  4820.9  809.61
  4836.5  808.86  4875.8  804.85  4899.8  803.60  4914.2  803.60  4947.6  801.82
  4962.9  800.13  4970.1  799.68  4980.5  800.06  4981.9  799.62  4991.2  798.88
  4995.2  793.58  4996.7  790.58  5003.3  790.58  5004.8  793.58  5021.0  797.36
  5032.9  801.35  5046.7  802.10  5062.5  804.32  5074.7  805.58  5091.6  805.96
  5101.5  806.76  5128.9  809.91  5139.2  810.36  5148.8  811.31  5211.1  812.40
#Mann=4,-1,0
  4758.7    0.15       0  4995.2    0.05       0  5004.8    0.15       0
  5074.7     0.1       0
#XS Ineff=2,0
    0.00 4925.00  815.00               0
Permanent Ineff=
       F       F
Bank Sta=4995.2,5004.8
XS Rating Curve= 0
Exp/Cntr=0.3,0.1

Type RM Length L Ch R = 1,3890,290,290,290
BEGIN DESCRIPTION:
Dutchman Creek Tributary 6 10.0
END DESCRIPTION:
XS GIS Cut Line= 4
      1501016.82       835923.41      1500815.03       835749.83
      1500504.78       835530.70      1500218.37       835502.50
#Sta/Elev= 30
  4704.9  820.63  4720.3  819.71  4773.5  814.56  4836.3  805.91  4859.4  801.20
  4878.8  798.72  4904.5  798.88  4918.8  799.70  4929.1  798.80  4948.1  800.49
  4958.4  798.94  4968.6  798.25  4974.6  798.63  4978.4  796.38  4994.9  793.59
  4995.2  791.26  4996.7  788.26  5003.3  788.26  5004.8  791.26  5007.4  797.80
  5008.5  798.26  5068.9  799.75  5176.5  800.39  5252.6  802.01  5282.9  803.14
  5342.5  808.37  5396.5  810.58  5456.1  813.91  5514.0  814.50  5638.7  817.39
#Mann=4,-1,0
  4704.9    0.15       0  4918.8     0.1       0  4995.2    0.05       0
  5004.8     0.1       0
#XS Ineff=2,0
    0.00 4960.00  821.00               0
Permanent Ineff=
       F       F
Bank Sta=4995.2,5004.8
XS Rating Curve= 0
Exp/Cntr=0.3,0.1

Type RM Length L Ch R = 1,3600,400,400,400
BEGIN DESCRIPTION:
Dutchman Creek Tributary 6 9.0
END DESCRIPTION:
XS GIS Cut Line= 3
      1501320.53       835645.69      1500870.98       835455.32
      1500467.87       835244.31
#Sta/Elev= 30
  4511.8  826.98  4542.0  820.80  4550.2  819.80  4563.4  815.76  4600.8  809.15
  4611.0  806.70  4671.7  798.50  4678.0  798.79  4722.6  797.88  4833.5  797.63
  4882.2  796.82  4923.8  794.29  4943.9  795.48  4982.5  796.22  4992.4  794.87
  4993.7  793.49  4995.2  790.19  4996.7  787.19  5003.3  787.19  5004.8  790.19
  5012.1  791.12  5020.5  796.64  5030.1  796.29  5076.9  797.46  5131.9  796.82
  5182.1  799.07  5212.3  799.18  5328.7  806.34  5398.1  808.90  5455.0  812.80
#Mann=4,-1,0
  4511.8    0.15       0  4678.0     0.1       0  4995.2    0.05       0
  5004.8     0.1       0
#XS Ineff=2,0
    0.00 4775.00  827.00               0
Permanent Ineff=
       F       F
Bank Sta=4995.2,5004.8
XS Rating Curve= 0
Exp/Cntr=0.3,0.1

Type RM Length L Ch R = 1,3200,400,400,400
BEGIN DESCRIPTION:
Dutchman Creek Tributary 6 8.0
END DESCRIPTION:
XS GIS Cut Line= 3
      1501425.03       835475.02      1501013.73       835101.05
      1500974.99       834974.97
#Sta/Elev= 30
  4444.1  831.84  4460.4  829.95  4510.8  822.78  4531.0  820.88  4551.6  811.20
  4571.4  806.42  4594.6  798.98  4606.5  797.53  4631.9  796.44  4681.4  795.39
  4780.6  795.20  4841.5  793.43  4860.2  793.79  4897.0  792.90  4958.6  795.49
  4972.3  795.38  4991.8  791.50  4995.2  789.83  4996.7  786.83  5003.3  786.83
  5004.8  789.83  5006.1  794.29  5016.9  794.89  5026.7  793.82  5035.1  793.86
  5047.3  800.36  5053.0  802.66  5072.4  807.21  5107.1  811.59  5131.9  813.70
#Mann=6,-1,0
  4444.1     0.1       0  4460.4    0.15       0  4631.9     0.1       0
  4897.0    0.15       0  4995.2    0.05       0  5004.8    0.15       0
Bank Sta=4995.2,5004.8
XS Rating Curve= 0
Exp/Cntr=0.3,0.1

Type RM Length L Ch R = 1,2800,304,304,304
BEGIN DESCRIPTION:
Dutchman Creek Tributary 6 7.0
END DESCRIPTION:
XS GIS Cut Line= 3
      1501510.17       835257.38      1501341.83       834930.93
      1501275.84       834866.82
#Sta/Elev= 30
  4632.7  811.47  4669.8  807.84  4699.3  803.58  4743.6  800.33  4770.6  796.55
  4771.9  796.05  4774.1  796.40  4787.0  796.25  4795.2  795.18  4814.5  793.95
  4883.8  791.36  4920.6  792.34  4950.1  792.40  4973.0  793.17  4980.2  792.78
  4989.9  788.53  4994.7  788.41  4995.2  787.76  4996.7  784.76  5003.3  784.76
  5004.8  787.76  5008.0  792.89  5015.1  795.54  5018.7  797.31  5024.5  799.28
  5035.3  802.33  5055.0  806.84  5063.6  810.01  5082.9  814.56  5092.0  816.33
#Mann=5,-1,0
  4632.7    0.15       0  4795.2     0.1       0  4920.6    0.15       0
  4995.2    0.05       0  5004.8    0.15       0
Bank Sta=4995.2,5004.8
XS Rating Curve= 0
Exp/Cntr=0.3,0.1

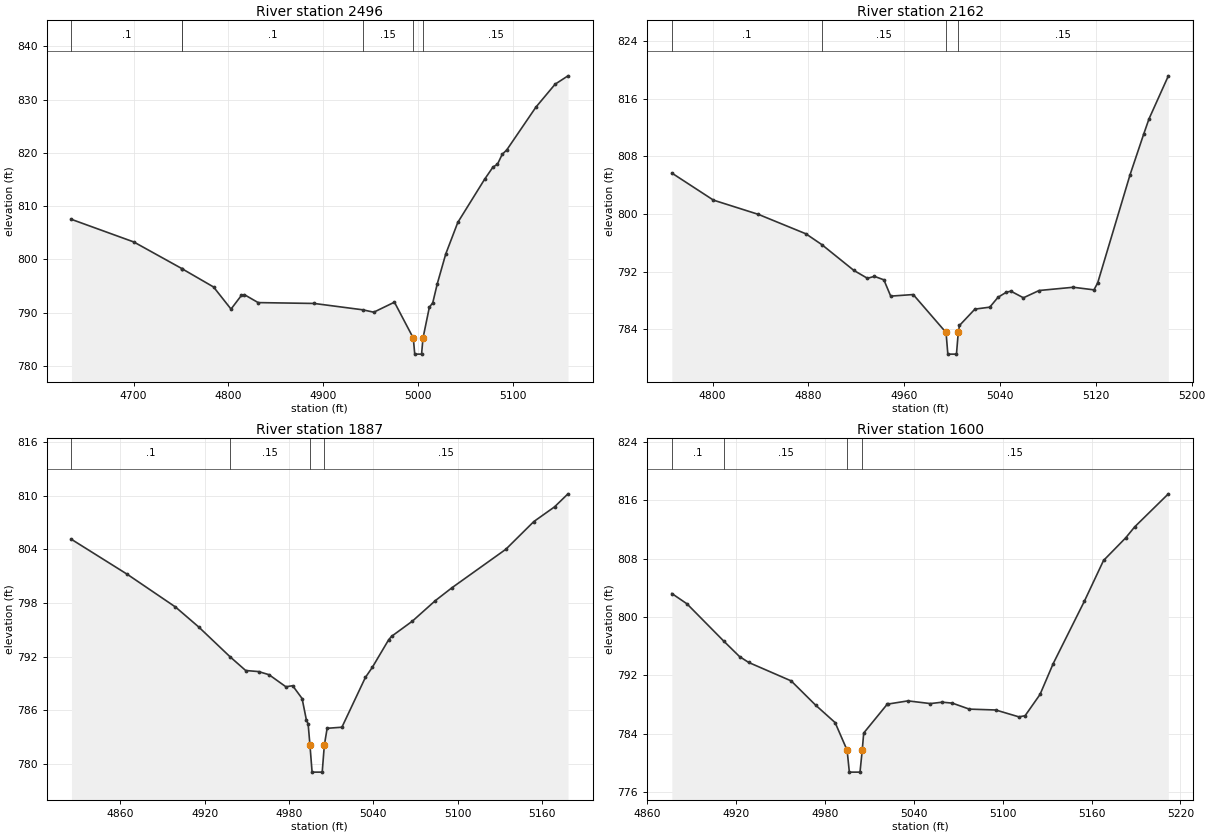
Type RM Length L Ch R = 1,2496,334,334,334
BEGIN DESCRIPTION:
Dutchman Creek Tributary 6 6.0
END DESCRIPTION:
XS GIS Cut Line= 3
      1501601.27       835196.63      1501599.10       834858.15
      1501625.01       834674.96
#Sta/Elev= 30
  4634.5  807.51  4700.2  803.27  4750.7  798.29  4751.4  798.21  4784.3  794.82
  4802.7  790.67  4813.6  793.23  4816.8  793.38  4831.3  791.89  4890.3  791.73
  4941.5  790.54  4953.2  790.09  4975.0  791.97  4994.9  785.22  4996.4  782.22
  5003.6  782.22  5005.1  785.22  5011.8  791.01  5015.4  791.86  5020.2  795.45
  5029.1  801.02  5041.8  806.94  5070.0  815.02  5078.9  817.33  5083.6  817.85
  5088.6  819.71  5093.4  820.54  5124.1  828.56  5144.4  832.88  5158.0  834.45
#Mann=6,-1,0
  4634.5     0.1       0  4750.7    0.15       0  4751.4     0.1       0
  4941.5    0.15       0  4994.9    0.05       0  5005.1    0.15       0
Bank Sta=4994.9,5005.1
XS Rating Curve= 0
Exp/Cntr=0.3,0.1

Type RM Length L Ch R = 1,2162,275,275,275
BEGIN DESCRIPTION:
Dutchman Creek Tributary 6 5.5
END DESCRIPTION:
XS GIS Cut Line= 2
      1501911.51       835025.25      1501915.85       834610.77
#Sta/Elev= 30
  4766.0  805.67  4800.7  801.92  4838.3  799.94  4877.9  797.25  4891.2  795.75
  4917.9  792.18  4929.3  791.08  4935.1  791.35  4943.0  790.87  4948.7  788.61
  4967.5  788.83  4994.9  783.57  4996.4  780.57  5003.6  780.57  5005.1  783.57
  5006.1  784.54  5019.0  786.81  5031.4  787.08  5038.3  788.45  5045.1  789.14
  5049.0  789.30  5059.5  788.38  5072.6  789.39  5101.1  789.84  5118.4  789.48
  5121.5  790.45  5148.5  805.43  5159.8  811.02  5164.3  813.17  5180.5  819.15
#Mann=4,-1,0
  4766.0     0.1       0  4891.2    0.15       0  4994.9    0.05       0
  5005.1    0.15       0
Bank Sta=4994.9,5005.1
XS Rating Curve= 0
Exp/Cntr=0.3,0.1

Type RM Length L Ch R = 1,1887,287,287,287
BEGIN DESCRIPTION:
Dutchman Creek Tributary 6 5.0
END DESCRIPTION:
XS GIS Cut Line= 3
      1502039.52       835085.93      1502124.13       834940.59
      1502243.45       834799.57
#Sta/Elev= 30
  4825.4  805.12  4865.1  801.21  4899.3  797.56  4915.8  795.33  4938.2  791.98
  4949.2  790.46  4958.4  790.34  4965.8  789.99  4977.8  788.64  4982.6  788.76
  4989.3  787.33  4992.3  784.97  4993.6  784.47  4994.9  782.10  4996.4  779.10
  5003.6  779.10  5005.1  782.10  5007.1  784.00  5017.6  784.12  5034.3  789.69
  5039.2  790.81  5050.8  793.89  5052.9  794.28  5067.7  795.98  5084.0  798.27
  5095.8  799.71  5134.1  804.01  5154.0  807.11  5168.7  808.75  5178.3  810.21
#Mann=4,-1,0
  4825.4     0.1       0  4938.2    0.15       0  4994.9    0.05       0
  5005.1    0.15       0
Bank Sta=4994.9,5005.1
XS Rating Curve= 0
Exp/Cntr=0.3,0.1

Type RM Length L Ch R = 1,1600,252,252,252
BEGIN DESCRIPTION:
Dutchman Creek Tributary 6 4.0
END DESCRIPTION:
XS GIS Cut Line= 3
      1502325.02       835174.96      1502380.10       835064.42
      1502475.02       834874.97
#Sta/Elev= 30
  4876.5  803.23  4886.7  801.82  4911.5  796.72  4922.2  794.59  4928.4  793.78
  4957.1  791.25  4973.6  787.93  4986.8  785.53  4994.9  781.74  4996.4  778.74
  5003.6  778.74  5005.1  781.74  5006.1  784.10  5021.9  788.03  5022.7  788.08
  5036.0  788.51  5051.1  788.14  5059.2  788.33  5066.0  788.20  5077.4  787.38
  5095.3  787.26  5110.9  786.32  5115.1  786.47  5125.2  789.39  5134.1  793.62
  5155.1  802.15  5168.1  807.76  5183.1  810.87  5189.1  812.36  5211.9  816.90
#Mann=4,-1,0
  4876.5     0.1       0  4911.5    0.15       0  4994.9    0.05       0
  5005.1    0.15       0
Bank Sta=4994.9,5005.1
XS Rating Curve= 0
Exp/Cntr=0.3,0.1