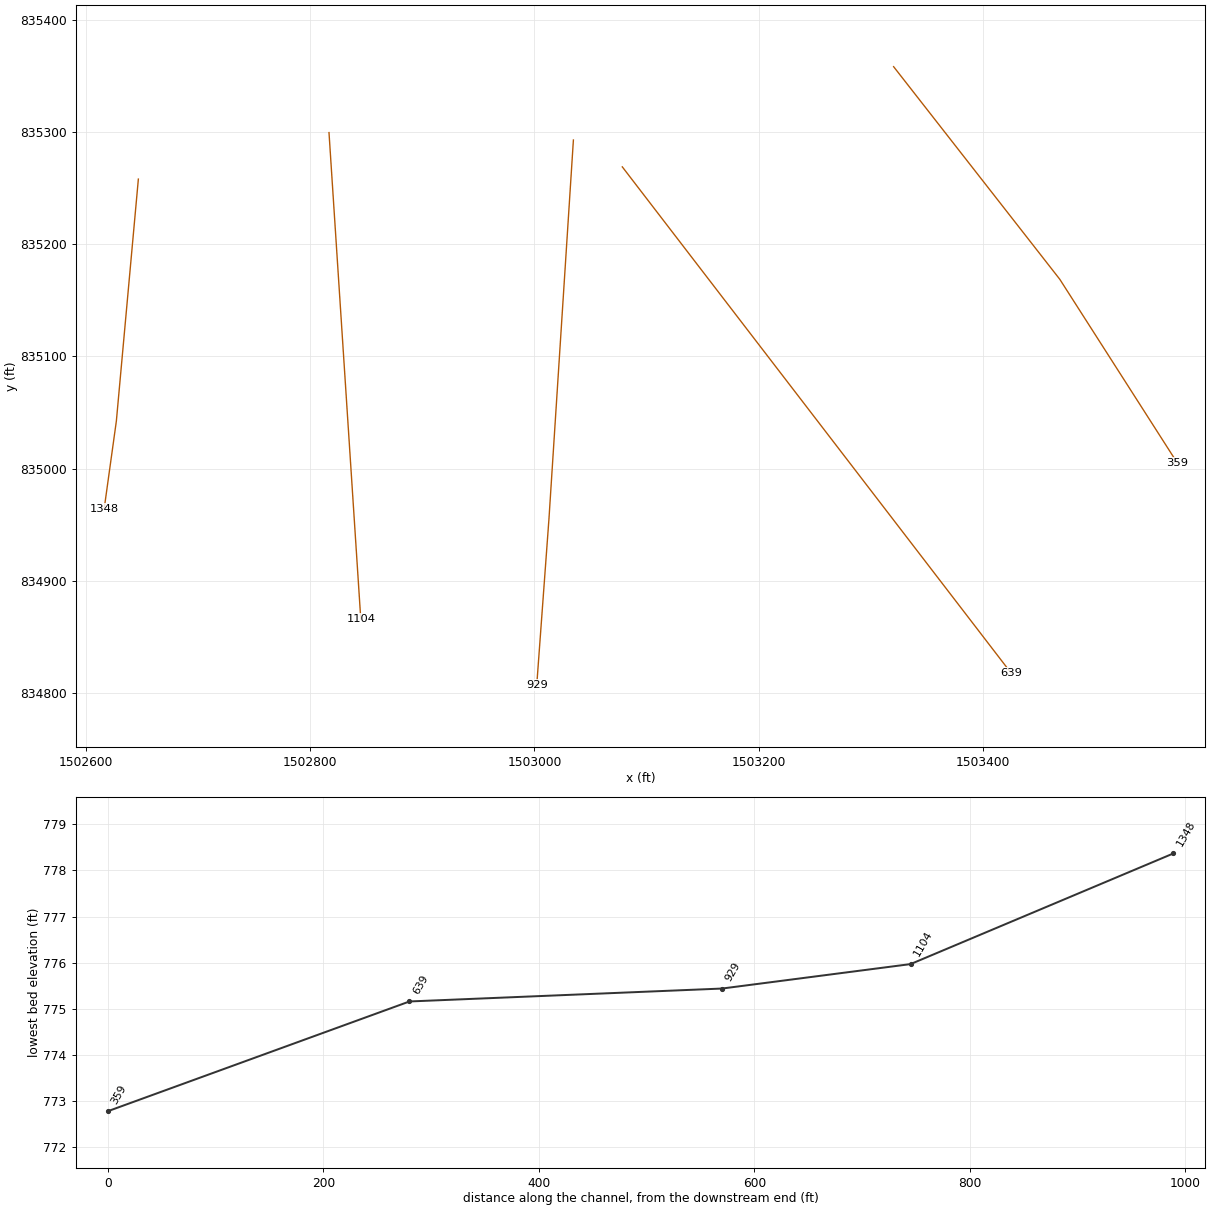
HEC-RAS study Dutchman Creek Tributary 6.prj: Dutchman Creek Tributary 6 Limited Detail Study

--- Dutchman Creek Tributary 6.g01 (geometry) --- (continued)

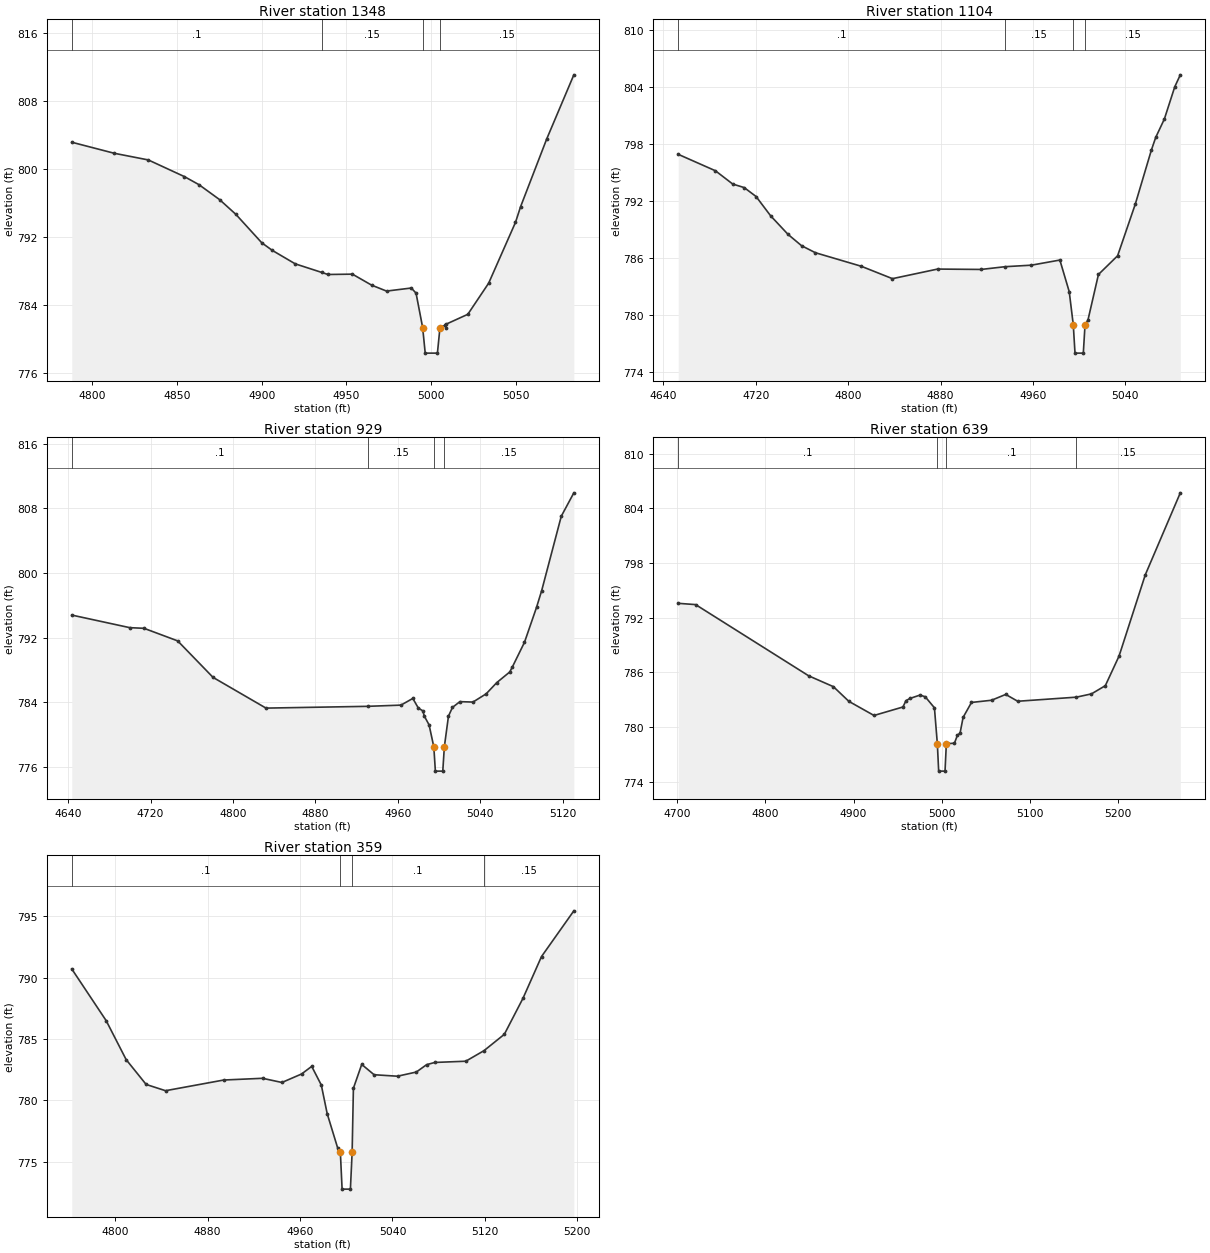
Type RM Length L Ch R = 1,1348,244,244,244
BEGIN DESCRIPTION:
Dutchman Creek Tributary 6 3.0
END DESCRIPTION:
XS GIS Cut Line= 3
      1502646.70       835258.19      1502627.08       835042.37
      1502616.18       834963.93
#Sta/Elev= 30
  4788.1  803.15  4813.2  801.85  4833.2  801.07  4854.5  799.11  4863.1  798.16
  4875.2  796.41  4884.8  794.68  4900.1  791.33  4906.3  790.44  4919.8  788.86
  4935.3  787.86  4939.1  787.61  4953.5  787.65  4964.8  786.36  4973.6  785.66
  4988.2  786.02  4991.0  785.42  4994.9  781.37  4996.4  778.37  5003.6  778.37
  5005.1  781.37  5008.2  781.64  5008.5  781.37  5008.6  781.76  5021.5  782.93
  5033.8  786.59  5049.6  793.73  5052.6  795.57  5068.0  803.53  5084.0  811.07
#Mann=4,-1,0
  4788.1     0.1       0  4935.3    0.15       0  4994.9    0.05       0
  5005.1    0.15       0
Bank Sta=4994.9,5005.1
XS Rating Curve= 0
Exp/Cntr=0.3,0.1

Type RM Length L Ch R = 1,1104,175,175,175
BEGIN DESCRIPTION:
Dutchman Creek Tributary 6 2.5
END DESCRIPTION:
XS GIS Cut Line= 2
      1502816.76       835299.67      1502845.10       834865.79
#Sta/Elev= 30
  4652.8  796.90  4685.0  795.17  4700.0  793.77  4709.9  793.40  4720.2  792.46
  4732.8  790.43  4747.9  788.47  4759.6  787.28  4771.6  786.54  4811.2  785.12
  4838.3  783.81  4877.4  784.82  4915.1  784.78  4935.9  785.07  4958.7  785.23
  4983.3  785.77  4991.4  782.44  4994.9  778.97  4996.4  775.97  5003.6  775.97
  5005.1  778.97  5007.6  779.44  5016.7  784.25  5033.3  786.22  5048.6  791.65
  5062.5  797.33  5066.3  798.68  5073.8  800.62  5082.8  804.01  5087.6  805.27
#Mann=4,-1,0
  4652.8     0.1       0  4935.9    0.15       0  4994.9    0.05       0
  5005.1    0.15       0
Bank Sta=4994.9,5005.1
XS Rating Curve= 0
Exp/Cntr=0.3,0.1

Type RM Length L Ch R = 1,929,290,290,290
BEGIN DESCRIPTION:
Dutchman Creek Tributary 6 2.0
END DESCRIPTION:
XS GIS Cut Line= 3
      1503034.78       835293.06      1503012.98       834955.16
      1503002.08       834806.86
#Sta/Elev= 30
  4643.5  794.78  4699.8  793.22  4713.6  793.14  4746.3  791.58  4780.6  787.06
  4832.0  783.25  4930.6  783.47  4963.0  783.62  4974.5  784.45  4979.9  783.25
  4984.1  782.92  4985.8  782.23  4990.3  781.17  4994.9  778.44  4996.4  775.44
  5003.6  775.44  5005.1  778.44  5009.1  782.25  5013.0  783.34  5020.2  784.05
  5032.9  784.00  5045.7  785.02  5056.0  786.41  5068.6  787.73  5071.1  788.34
  5082.9  791.41  5094.6  795.74  5099.6  797.82  5118.6  807.03  5130.8  809.93
#Mann=4,-1,0
  4643.5     0.1       0  4930.6    0.15       0  4994.9    0.05       0
  5005.1    0.15       0
Bank Sta=4994.9,5005.1
XS Rating Curve= 0
Exp/Cntr=0.3,0.1

Type RM Length L Ch R = 1,639,280,280,280
BEGIN DESCRIPTION:
Dutchman Creek Tributary 6 1.5
END DESCRIPTION:
XS GIS Cut Line= 2
      1503078.40       835269.10      1503425.07       834817.78
#Sta/Elev= 30
  4701.2  793.58  4720.9  793.44  4849.1  785.62  4877.1  784.43  4894.6  782.82
  4923.1  781.27  4955.9  782.20  4959.3  782.89  4963.9  783.14  4975.3  783.51
  4981.2  783.32  4991.6  782.11  4994.9  778.16  4996.4  775.16  5003.6  775.16
  5005.1  778.16  5014.3  778.23  5017.7  779.11  5020.6  779.31  5024.1  781.06
  5033.6  782.70  5056.3  782.94  5072.4  783.58  5086.0  782.83  5152.5  783.28
  5169.6  783.64  5185.3  784.54  5200.9  787.80  5230.6  796.71  5270.3  805.71
#Mann=4,-1,0
  4701.2     0.1       0  4994.9    0.05       0  5005.1     0.1       0
  5152.5    0.15       0
Bank Sta=4994.9,5005.1
XS Rating Curve= 0
Exp/Cntr=0.3,0.1

Type RM Length L Ch R = 1,359,0,0,0
BEGIN DESCRIPTION:
Dutchman Creek Tributary 6 1.0
END DESCRIPTION:
XS GIS Cut Line= 3
      1503320.43       835358.48      1503468.66       835168.83
      1503573.28       835005.35
#Sta/Elev= 30
  4762.3  790.70  4792.1  786.49  4809.4  783.32  4826.7  781.30  4843.5  780.79
  4893.9  781.66  4927.5  781.80  4944.3  781.46  4961.3  782.15  4970.1  782.77
  4978.4  781.25  4983.5  778.92  4992.5  776.15  4994.9  775.78  4996.4  772.78
  5003.6  772.78  5005.1  775.78  5006.2  780.99  5013.4  782.93  5024.1  782.09
  5044.4  781.97  5060.7  782.31  5069.6  782.91  5076.7  783.09  5103.5  783.19
  5119.3  784.05  5136.9  785.38  5153.1  788.32  5169.1  791.71  5197.1  795.43
#Mann=4,-1,0
  4762.3     0.1       0  4994.9    0.05       0  5005.1     0.1       0
  5119.3    0.15       0
Bank Sta=4994.9,5005.1
XS Rating Curve= 0
Exp/Cntr=0.3,0.1

Chan Stop Cuts=-1