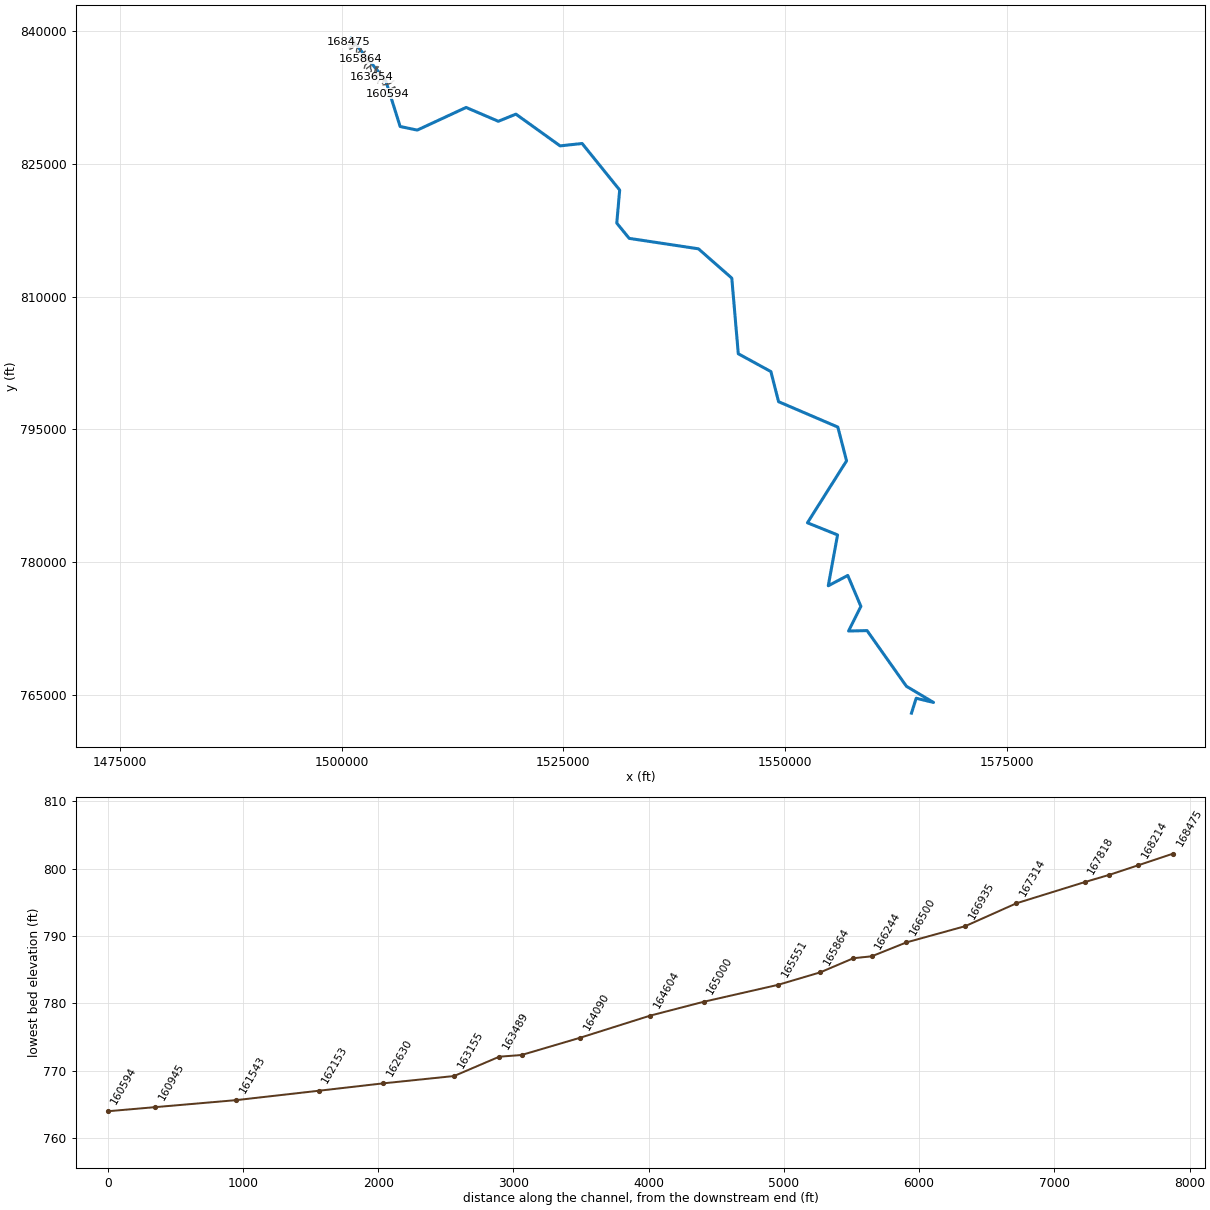
--- Dutchman Creek.prj (project) ---

Proj Title=Dutchman Creek Limited Detail Study
Current Plan=p01
Default Exp/Contr=0.3,0.1
English Units
Geom File=g01
Flow File=f01
Plan File=p01
Y Axis Title=Elevation
X Axis Title(PF)=Main Channel Distance
X Axis Title(XS)=Station
BEGIN DESCRIPTION:
Dutchman Creek
END DESCRIPTION:
DSS Export Rating Curves= 0
DSS Export Rating Curve Sorted= 0
DSS Export Volume Flow Curves= 0
DXF OffsetX= 0
DXF OffsetY= 0
DXF ScaleX= 1
DXF ScaleY= 10

--- Dutchman Creek.p01 (plan) ---

Plan Title=Floodway Run
Program Version=3.12
Short Identifier=Floodway
Geom File=g01
Flow File=f01
Subcritical Flow
K Sum by GR= 0
Std Step Tol= 0.01
Critical Tol= 0.01
Num of Std Step Trials= 20
Max Error Tol= 0.3
Flow Tol Ratio= 0.001
Split Flow NTrial= 30
Split Flow Tol= 0.02
Split Flow Ratio= 0.02
Log Output Level= 0
Friction Slope Method= 0
Unsteady Friction Slope Method= 2
Unsteady Bridges Friction Slope Method= 1
Calc Critical at every XS
Parabolic Critical Depth
Global Vel Dist= 0 , 0 , 0
Global Log Level= 0
CheckData=True
Encroach Param=-1 ,10,10, 2
Encroach River=Dutchman Creek
Encroach Reach=Reach-1
Encroach Node=168475
       1    4962    5015
Encroach Node=168214
       1    4983    5014
Encroach Node=168002
       1    4979    5019
Encroach Node=167818
       1    4975    5045
Encroach Node=167314
       1    4975    5030
Encroach Node=166935
       1    4910    5012
Encroach Node=166500
       1    4817    5012
Encroach Node=166244
       1    4930    5070
Encroach Node=166108
       1    4930    5070
Encroach Node=165864
       1    4906    5013
Encroach Node=165551
       1    4905    5013
Encroach Node=165000
       1    4878    5007
Encroach Node=164604
       1    4920    5010
Encroach Node=164090
       1    4975    5053
Encroach Node=163654
       1    4920    5080
Encroach Node=163489
       1    4905    5095
Encroach Node=163155
       1    4977    5095
Encroach Node=162630
       1    4979    5177
Encroach Node=162153
       1    4933    5139
Encroach Node=161543
       1    4849    5181
Encroach Node=160945
       1    4745    5169
Encroach Node=160594
       1    4708    5111
Encroach Node=160272
       1    4894    5244
Encroach Node=159635
       1    4596    5018
Encroach Node=158975
       1    4635    5078
Encroach Node=158295
       1    4644    5024
Encroach Node=158003
       1    4563    5052
Encroach Node=157021
       1    4756    5366
Encroach Node=155639
       1    4500    5184
Encroach Node=154445
       1    4410    5285
Encroach Node=152854
       1    4615    5410
Encroach Node=151677
       1    4400    5565
Encroach Node=150896
       1    4400    5300
Encroach Node=150618
       1    4970    5030
Encroach Node=150564
       1    4973    5027
Encroach Node=150360
       1    4979    5027
Encroach Node=150159
       1    4950    5050
Encroach Node=149153
       1    4900    5250
Encroach Node=148256
       1    4700    5250
Encroach Node=147245
       1    4496    5026
Encroach Node=146257
       1    4445    5026
Encroach Node=145500
       1    4459    5028
Encroach Node=144413
       1    4850    5210
Encroach Node=143233
       1    4600    5200
Encroach Node=142351
       1    4647    5295
Encroach Node=141315
       1    4971    5389
Encroach Node=140855
       1    4874    5350
Encroach Node=139876
       1    4641    5054
Encroach Node=139426
       1    4651    5183
Encroach Node=138743
       1    4969    5350
Encroach Node=138424
       1    4920    5135
Encroach Node=137662
       1    4960    5350
Encroach Node=137279
       1    4893    5352
Encroach Node=136724
       1    4828    5106
Encroach Node=136377
       1    4920    5080
Encroach Node=136221
       1    4920    5080
Encroach Node=135438
       1    4913    5036
Encroach Node=135000
       1    4965    5148
Encroach Node=134232
       1    4922    5145
Encroach Node=133383
       1    4880    5034
Encroach Node=132659
       1    4960    5230
Encroach Node=132038
       1    4965    5423
Encroach Node=131502
       1    4641    5157
Encroach Node=130500
       1    4471    5034
Encroach Node=129778
       1    4249    5034
Encroach Node=128922
       1    4173    5034
Encroach Node=127808
       1    4930    5513
Encroach Node=127682
       1    4930    5513
Encroach Node=126988
       1    4701    5327
Encroach Node=126357
       1    4975    5332
Encroach Node=126051
       1    4967    5385
Encroach Node=125574
       1    4657    5317
Encroach Node=125153
       1    4584    5265
Encroach Node=124544
       1    4550    5030
Encroach Node=124242
       1 4423.24    5029
Encroach Node=124141
       1 4423.24    5029
Encroach Node=123223
       1    4950    5425
Encroach Node=122359
       1    4350    5250
Encroach Node=121602
       1    4232    5389
Encroach Node=120711
       1    4118    5144
Encroach Node=119921
       1    4033    5026
Encroach Node=118438
       1    4826    5349
Encroach Node=117928
       1    4973    5632
Encroach Node=117294
       1    4973    5492
Encroach Node=116837
       1    4823    5283
Encroach Node=116215
       1    4972    5344
Encroach Node=115742
       1    4788    5373
Encroach Node=114423
       1    4525    5475
Encroach Node=113398
       1    4256    5417
Encroach Node=112014
       1    4613    5567
Encroach Node=111226
       1    4570    5610
Encroach Node=110738
       1    4751    5701
Encroach Node=110131
       1    4800    5100
Encroach Node=109936
       1    4800    5100
Encroach Node=108863
       1    4556    5988
Encroach Node=108010
       1    4977    5974
Encroach Node=107446
       1    4913    5893
Encroach Node=106477
       1    4792    5217
Encroach Node=105885
       1    4432    5042
Encroach Node=104702
       1    4249    5481
Encroach Node=103754
       1    4389    5658
Encroach Node=102792
       1    4672    5505
Encroach Node=101601
       1    4437    5686
Encroach Node=99645
       1    4970    5925
Encroach Node=98369
       1    4625    5480
Encroach Node=97709
       1    4755    5275
Encroach Node=96884
       1    4970    5600
Encroach Node=95841
       1    4450    5525
Encroach Node=95037
       1    3950    5030
Encroach Node=94485
       1    4090    5030
Encroach Node=93318
       1    4925    5480
Encroach Node=92440
       1    4830    5550
Encroach Node=91269
       1    4970    5750
Encroach Node=90712
       1    4970    5425
Encroach Node=89685
       1    4840    5075
Encroach Node=89319
       1    4945    5225
Encroach Node=88795
       1    4840    5200
Encroach Node=88509
       1    4700    5080
Encroach Node=88006
       1    4955    5235
Encroach Node=87622
       1    4675    5060
Encroach Node=87098
       1    4855    5225
Encroach Node=86808
       1    4845    5215
Encroach Node=86089
       1    4755    5035
Encroach Node=85631
       1    4705    5100
Encroach Node=85084
       1    4865    5145
Encroach Node=84254
       1    4850    5270
Encroach Node=83806
       1    4750    5190
Encroach Node=83502
       1    4850    5150
Encroach Node=83190
       1    4865    5150
Encroach Node=82282
       1    4965    5440
Encroach Node=81573
       1    4700    5180
Encroach Node=81030
       1    4760    5090
Encroach Node=80485
       1    4912 5059.15
Encroach Node=80352
       1    4912    5085
Encroach Node=80234
       1    4880    5050
Encroach Node=79511
       1    4795    5125
Encroach Node=78838
       1    4702    5142
Encroach Node=78391
       1    4848    5070
Encroach Node=77988
       1    4890    5035
Encroach Node=77461
       1    4960    5135
Encroach Node=77048
       1    4900    5205
Encroach Node=76391
       1    4810    5395
Encroach Node=75294
       1    4240    5370
Encroach Node=74371
       1    4362    5060
Encroach Node=73124
       1    4965    5845
Encroach Node=72180
       1    4920    5805
Encroach Node=71252
       1    4295    5040
Encroach Node=70090
       1    4960    5665
Encroach Node=69294
       1    4650    5535
Encroach Node=68687
       1    4565    5355
Encroach Node=67698
       1    4625    5035
Encroach Node=67312
       1    4510    5040
Encroach Node=66530
       1    4570    5115
Encroach Node=65517
       1    4750    5040
Encroach Node=64810
       1    4930    5145
Encroach Node=64548
       1 4932.35 5126.62
Encroach Node=64436
       1 4925.34 5126.62
Encroach Node=63919
       1    4855    5165
Encroach Node=63222
       1    4770    5100
Encroach Node=62296
       1    4865    5525
Encroach Node=61225
       1    4955    6160
Encroach Node=60447
       1    4625    5975
Encroach Node=59718
       1    4235    5540
Encroach Node=58364
       1    4325    5600
Encroach Node=56828
       1    4685    5510
Encroach Node=56315
       1 4390.22    5190
Encroach Node=56152
       1  4460.1    5190
Encroach Node=54878
       1    4950    5625
Encroach Node=54214
       1    4770    5480
Encroach Node=53607
       1    4900    5480
Encroach Node=53049
       1    4950    5700
Encroach Node=52381
       1    4810    5610
Encroach Node=51728
       1    4935    5800
Encroach Node=50885
       1    4955    5935
Encroach Node=49676
       1    4955    6045
Encroach Node=48654
       1    4955    5975
Encroach Node=47771
       1    4860    5620
Encroach Node=46298
       1    4730    5335
Encroach Node=45594
       1    4955    5500
Encroach Node=43948
       1    4175    5050
Encroach Node=42927
       1    4700    5205
Encroach Node=42290
       1    4725    5445
Encroach Node=41595
       1    4950    5375
Encroach Node=41075
       1    4775    5155
Encroach Node=40128
       1    4835    5060
Encroach Node=39462
       1    4930    5225
Encroach Node=38891
       1    4900    5090
Encroach Node=38121
       1    4788    5128
Encroach Node=37486
       1    4935    5250
Encroach Node=36493
       1    4925    5088
Encroach Node=35608
       1    4900    5160
Encroach Node=35359
       1    4925    5170
Encroach Node=34877
       1    4875    5120
Encroach Node=34723
       1    4875    5120
Encroach Node=34389
       1    4960    5320
Encroach Node=33742
       1    4575    5080
Encroach Node=32997
       1    4855    5385
Encroach Node=32612
       1    4715    5240
Encroach Node=32038
       1    4800    5072
Encroach Node=31433
       1    4900    5095
Encroach Node=30836
       1    4925    5225
Encroach Node=29399
       1    4835    5055
Encroach Node=28226
       1    4930    5120
Encroach Node=27751
       1    4890    5115
Encroach Node=27203
       1    4830    5155
Encroach Node=25932
       1    4805    5060
Encroach Node=24563
       1    4950    5115
Encroach Node=23810
       1    4790    5040
Encroach Node=23251
       1    4945    5325
Encroach Node=22152
       1    4325    5040
Encroach Node=21443
       1    3900    5065
Encroach Node=20604
       1    3435    5225
Encroach Node=18266
       1    4225    5625
Encroach Node=16619
       1    4210    5075
Encroach Node=15118
       1    3680    5085
Encroach Node=14285
       1    3705    5050
Encroach Node=12250
       1    4415    5125
Encroach Node=11844
       1    4815    5200
Encroach Node=11434
       1    4939    5170
Encroach Node=11286
       1    4914    5170
Encroach Node=10468
       1    4880    5065
Encroach Node=9533
       1    4865    5090
Encroach Node=8178
       1    4650    5035
Encroach Node=7417
       1    4850    5325
Encroach Node=5786
       1    4760    5500
Encroach Node=3871
       1    4954    5720
Encroach Node=2279
       1    4630    5425
BEGIN DESCRIPTION:
Floodway Run
END DESCRIPTION:
Computation Interval=1HOUR
Output Interval=1HOUR
Run HTab= 0
Run UNet= 0
Run PostProcess= 0
UNET Theta= 1
UNET Theta Warmup= 1
UNET ZTol= 0.02
UNET ZSATol= 0.05
UNET MxIter= 20
UNET MaxInSteps= 0
UNET DtIC= 0
UNET DtMin= 0
UNET MaxCRTS= 20
UNET WFStab= 2
UNET SFStab= 1
UNET WFX= 1
UNET SFX= 1
UNET DSS MLevel= 4
UNET DZMax Abort= 100
UNET Convert EG Bridges=-1
UNET Use Existing IB Tables=-1
UNET Froude Reduction=False
UNET Froude Limit= 1
UNET Froude Power= 10
Instantaneous Interval=1HOUR
Write IC File= 0
Echo Input=False
Echo Output=False
Write Detailed= 0
Detailed Automatic Start=False, 10

--- Dutchman Creek.f01 (steady flow) ---

Flow Title=Floodway
Number of Profiles=2
Profile Names=100-year,100-FW
River Rch & RM= Dutchman Creek,Reach-1,168475
    1104    1104
River Rch & RM= Dutchman Creek,Reach-1,167314
    1136    1136
River Rch & RM= Dutchman Creek,Reach-1,166500
    1246    1246
River Rch & RM= Dutchman Creek,Reach-1,163654
    2325    2325
River Rch & RM= Dutchman Creek,Reach-1,162153
    2418    2418
River Rch & RM= Dutchman Creek,Reach-1,160945
    2446    2446
River Rch & RM= Dutchman Creek,Reach-1,158975
    2556    2556
River Rch & RM= Dutchman Creek,Reach-1,155639
    3439    3439
River Rch & RM= Dutchman Creek,Reach-1,154445
    3645    3645
River Rch & RM= Dutchman Creek,Reach-1,151677
    3730    3730
River Rch & RM= Dutchman Creek,Reach-1,149153
    3770    3770
River Rch & RM= Dutchman Creek,Reach-1,147245
    4883    4883
River Rch & RM= Dutchman Creek,Reach-1,146257
    5367    5367
River Rch & RM= Dutchman Creek,Reach-1,140855
    5760    5760
River Rch & RM= Dutchman Creek,Reach-1,138743
    6527    6527
River Rch & RM= Dutchman Creek,Reach-1,128922
    6672    6672
River Rch & RM= Dutchman Creek,Reach-1,122359
    7037    7037
River Rch & RM= Dutchman Creek,Reach-1,116215
    7139    7139
River Rch & RM= Dutchman Creek,Reach-1,111226
    7477    7477
River Rch & RM= Dutchman Creek,Reach-1,110131
    7861    7861
River Rch & RM= Dutchman Creek,Reach-1,96884
    8445    8445
River Rch & RM= Dutchman Creek,Reach-1,89685
    9086    9086
River Rch & RM= Dutchman Creek,Reach-1,84254
    9140    9140
River Rch & RM= Dutchman Creek,Reach-1,81030
    9416    9416
River Rch & RM= Dutchman Creek,Reach-1,76391
    9473    9473
River Rch & RM= Dutchman Creek,Reach-1,72180
    9672    9672
River Rch & RM= Dutchman Creek,Reach-1,64810
   11892   11892
River Rch & RM= Dutchman Creek,Reach-1,58364
   12527   12527
River Rch & RM= Dutchman Creek,Reach-1,43948
   13444   13444
River Rch & RM= Dutchman Creek,Reach-1,40128
   13936   13936
River Rch & RM= Dutchman Creek,Reach-1,35359
   14425   14425
River Rch & RM= Dutchman Creek,Reach-1,32612
   14511   14511
River Rch & RM= Dutchman Creek,Reach-1,25932
   14805   14805
River Rch & RM= Dutchman Creek,Reach-1,12250
   15227   15227
River Rch & RM= Dutchman Creek,Reach-1,5786
   15368   15368
River Rch & RM= Dutchman Creek,Reach-1,3871
   15567   15567
Boundary for River Rch & Prof#=Dutchman Creek,Reach-1,1
Up Type=0
Dn Type=3
Dn Slope=0.000446
Boundary for River Rch & Prof#=Dutchman Creek,Reach-1,2
Up Type=0
Dn Type=3
Dn Slope=0.000446

--- Dutchman Creek.g01 (geometry) ---

Geom Title=Existing Conditions

River Reach=Dutchman Creek,Reach-1
Reach XY= 30
      1501028.84       839160.03      1504963.01       834394.03
      1506590.10       829201.67      1508519.62       828793.11
      1514029.18       831352.35      1517660.19       829790.73
      1519645.94       830597.39      1524629.16       827012.67
      1527110.80       827280.59      1531345.75       822021.54
      1531016.32       818291.73      1532417.35       816565.69
      1540227.47       815386.32      1543986.96       812074.78
      1544718.90       803534.37      1548395.81       801520.44
      1549262.13       798120.10      1555943.90       795251.53
      1556927.49       791437.72      1552516.27       784441.07
      1555911.57       783073.75      1554865.56       777328.95
      1557063.91       778494.32      1558543.95       775000.61
      1557152.89       772218.49      1559238.39       772265.59
      1563676.33       765977.61      1566736.22       764149.27
      1564778.76       764628.87      1564248.04       762943.33

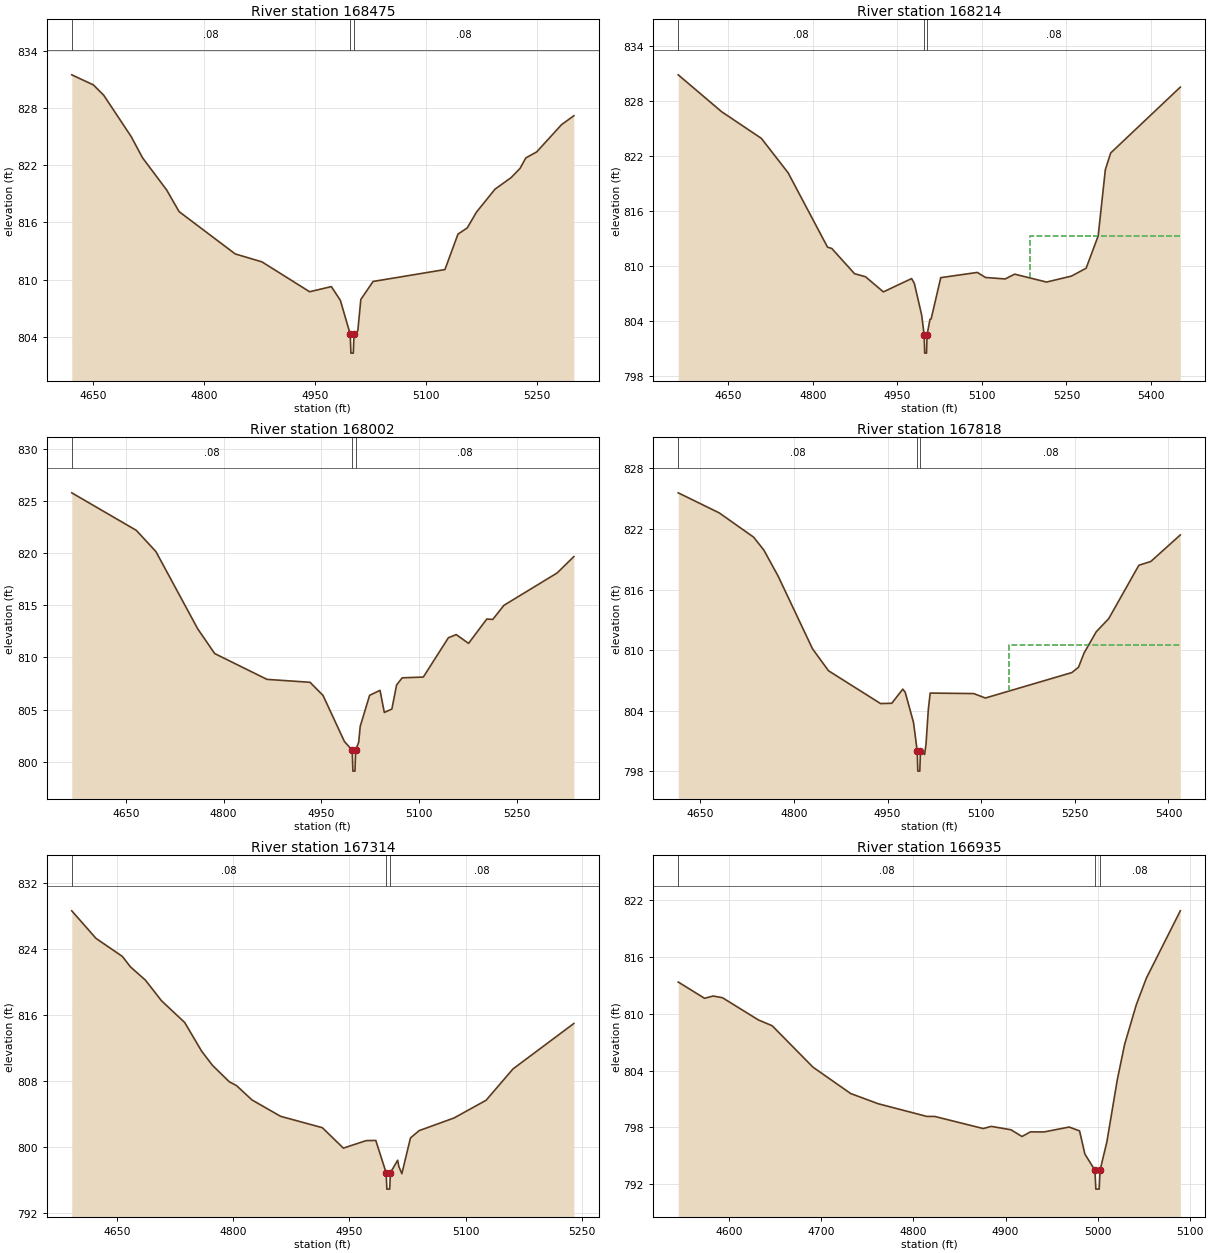
Type RM Length L Ch R = 1,168475,261,261,261
BEGIN DESCRIPTION:
Dutchman Creek 202.0
END DESCRIPTION:
XS GIS Cut Line= 4
      1501458.18       838730.94      1501203.71       838719.99
      1501001.22       838698.10      1500782.35       838728.20
#Sta/Elev= 30
  4620.7  831.51  4650.0  830.45  4664.0  829.36  4701.1  825.02  4716.4  822.80
  4749.2  819.40  4765.9  817.14  4841.9  812.69  4878.0  811.86  4942.5  808.72
  4971.9  809.26  4984.1  807.82  4997.4  804.27  4998.4  802.27  5001.6  802.27
  5002.6  804.27  5007.7  804.61  5011.8  807.91  5028.4  809.80  5125.6  811.05
  5143.2  814.77  5155.8  815.43  5168.3  817.09  5193.4  819.50  5215.1  820.71
  5227.2  821.68  5235.0  822.78  5249.7  823.41  5283.3  826.27  5300.0  827.21
#Mann=3,-1,0
  4620.7    0.08       0  4997.4   0.045       0  5002.6    0.08       0
Bank Sta=4997.4,5002.6
XS Rating Curve= 0
Exp/Cntr=0.3,0.1

Type RM Length L Ch R = 1,168214,212,212,212
BEGIN DESCRIPTION:
Dutchman Creek 201.0
END DESCRIPTION:
XS GIS Cut Line= 3
      1501525.04       838625.02      1501181.82       838457.31
      1500672.89       838435.42
#Sta/Elev= 30
  4560.8  830.83  4637.7  826.82  4708.4  823.91  4755.8  820.17  4825.9  812.06
  4833.4  811.92  4873.8  809.17  4893.3  808.84  4925.0  807.19  4975.1  808.64
  4980.0  808.11  4993.0  804.67  4997.4  802.52  4998.4  800.52  5001.6  800.52
  5002.6  802.52  5007.8  804.20  5009.8  804.24  5026.9  808.74  5091.8  809.31
  5106.4  808.76  5141.2  808.60  5158.2  809.12  5214.7  808.26  5259.0  808.91
  5285.0  809.77  5306.4  813.29  5319.1  820.50  5328.6  822.32  5452.2  829.49
#Mann=3,-1,0
  4560.8    0.08       0  4997.4   0.045       0  5002.6    0.08       0
#XS Ineff=2,0
       0                 5185.50    0.00  813.25
Permanent Ineff=
       F       F
Bank Sta=4997.4,5002.6
XS Rating Curve= 0
Exp/Cntr=0.3,0.1

Type RM Length L Ch R = 1,168002,184,184,184
BEGIN DESCRIPTION:
Dutchman Creek 200.0
END DESCRIPTION:
XS GIS Cut Line= 4
      1501542.98       838446.35      1501288.53       838334.18
      1501045.00       838189.16      1500847.96       838120.74
#Sta/Elev= 30
  4567.2  825.77  4666.1  822.18  4696.2  820.15  4760.4  812.74  4786.5  810.37
  4866.6  807.90  4932.7  807.62  4952.6  806.36  4985.4  801.95  4997.4  801.11
  4998.4  799.11  5001.6  799.11  5002.6  801.11  5007.3  801.88  5009.6  803.39
  5024.0  806.37  5040.0  806.85  5046.6  804.73  5058.2  805.06  5065.4  807.36
  5074.0  808.05  5106.4  808.12  5144.9  811.89  5156.9  812.19  5175.8  811.35
  5203.8  813.68  5212.9  813.64  5230.0  814.99  5311.6  818.09  5337.3  819.66
#Mann=3,-1,0
  4567.2    0.08       0  4997.4   0.045       0  5002.6    0.08       0
Bank Sta=4997.4,5002.6
XS Rating Curve= 0
Exp/Cntr=0.3,0.1

Type RM Length L Ch R = 1,167818,504,504,504
BEGIN DESCRIPTION:
Dutchman Creek 199.0
END DESCRIPTION:
XS GIS Cut Line= 4
      1501546.14       838426.61      1501430.50       838282.06
      1501213.66       838053.65      1500933.24       837935.12
#Sta/Elev= 30
  4614.5  825.58  4680.3  823.59  4735.3  821.19  4751.7  819.91  4774.5  817.34
  4829.7  810.13  4855.3  807.96  4938.7  804.71  4956.7  804.74  4974.3  806.14
  4978.2  805.83  4991.5  802.84  4997.4  800.02  4998.4  798.02  5001.6  798.02
  5002.6  800.02  5009.3  799.67  5011.5  800.67  5015.2  804.10  5018.2  805.75
  5088.0  805.70  5106.6  805.26  5245.2  807.78  5255.9  808.31  5264.7  809.71
  5284.3  811.82  5304.3  813.12  5352.6  818.41  5371.7  818.78  5419.0  821.41
#Mann=3,-1,0
  4614.5    0.08       0  4997.4   0.045       0  5002.6    0.08       0
#XS Ineff=2,0
       0                 5144.30    0.00  810.50
Permanent Ineff=
       F       F
Bank Sta=4997.4,5002.6
XS Rating Curve= 0
Exp/Cntr=0.3,0.1

Type RM Length L Ch R = 1,167314,379,379,379
BEGIN DESCRIPTION:
Dutchman Creek 198.0
END DESCRIPTION:
XS GIS Cut Line= 4
      1501867.19       838218.07      1501704.95       837974.70
      1501675.26       837796.62      1501677.24       837622.46
#Sta/Elev= 30
  4592.0  828.67  4623.3  825.32  4657.3  823.13  4667.6  821.87  4686.9  820.26
  4707.6  817.76  4737.6  815.11  4759.4  811.63  4773.4  809.91  4795.1  807.91
  4804.4  807.45  4824.3  805.71  4861.2  803.72  4915.0  802.34  4942.1  799.86
  4971.5  800.77  4983.9  800.79  4997.2  796.88  4998.2  794.88  5001.8  794.88
  5002.8  796.88  5012.1  798.39  5013.6  797.63  5017.5  796.76  5028.6  801.09
  5039.7  801.98  5084.8  803.52  5126.1  805.67  5160.7  809.47  5239.2  814.99
#Mann=3,-1,0
  4592.0    0.08       0  4997.2   0.045       0  5002.8    0.08       0
Bank Sta=4997.2,5002.8
XS Rating Curve= 0
Exp/Cntr=0.3,0.1

Type RM Length L Ch R = 1,166935,435,435,435
BEGIN DESCRIPTION:
Dutchman Creek 197.0
END DESCRIPTION:
XS GIS Cut Line= 4
      1502188.00       837984.31      1502164.87       837839.71
      1501994.29       837634.43      1501881.56       837565.06
#Sta/Elev= 30
  4544.3  813.36  4572.9  811.64  4582.3  811.88  4592.4  811.70  4631.5  809.35
  4646.4  808.74  4690.7  804.37  4731.7  801.58  4761.7  800.50  4814.5  799.16
  4823.0  799.16  4875.8  797.88  4884.5  798.11  4906.0  797.75  4917.9  797.04
  4927.2  797.53  4941.8  797.52  4969.2  798.04  4980.5  797.63  4986.3  795.18
  4997.2  793.48  4998.2  791.48  5001.8  791.48  5002.8  793.48  5010.2  796.48
  5021.5  803.03  5029.5  806.78  5042.2  810.97  5053.1  813.77  5090.0  820.88
#Mann=3,-1,0
  4544.3    0.08       0  4997.2   0.045       0  5002.8    0.08       0
Bank Sta=4997.2,5002.8
XS Rating Curve= 0
Exp/Cntr=0.3,0.1

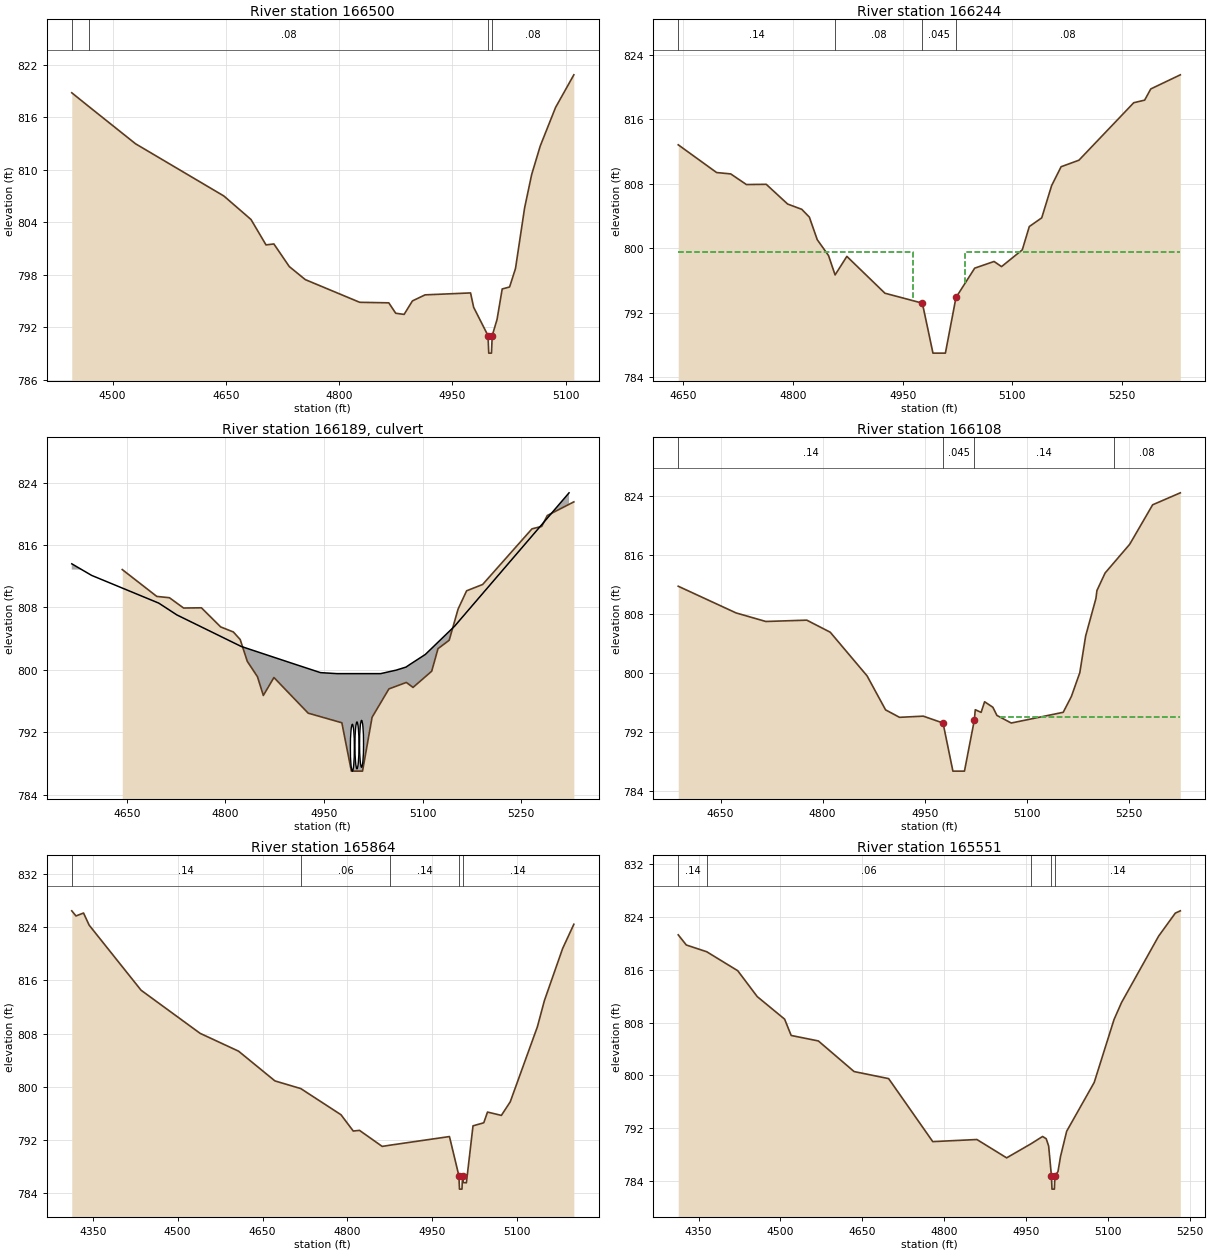
Type RM Length L Ch R = 1,166500,256,256,256
BEGIN DESCRIPTION:
Dutchman Creek 196.0
END DESCRIPTION:
XS GIS Cut Line= 4
      1502642.48       837695.14      1502414.64       837443.37
      1502231.63       837331.42      1502142.87       837264.92
#Sta/Elev= 30
  4445.9  818.78  4468.4  817.22  4530.4  812.96  4647.4  807.00  4683.3  804.32
  4703.2  801.42  4713.6  801.53  4734.0  798.95  4755.2  797.46  4827.3  794.87
  4865.8  794.81  4875.0  793.62  4886.1  793.49  4897.1  795.03  4913.9  795.72
  4974.1  795.94  4978.2  794.30  4997.2  791.07  4998.2  789.07  5001.8  789.07
  5002.8  791.07  5009.2  792.92  5016.0  796.39  5025.8  796.62  5033.6  798.72
  5045.7  805.65  5055.0  809.44  5066.4  812.71  5086.7  817.11  5110.9  820.83
#Mann=4,-1,0
  4445.9    0.14       0  4468.4    0.08       0  4997.2   0.045       0
  5002.8    0.08       0
Bank Sta=4997.2,5002.8
XS Rating Curve= 0
Exp/Cntr=0.5,0.3

Type RM Length L Ch R = 1,166244,136,136,136
BEGIN DESCRIPTION:
Amber Hill Rd (DC) us
END DESCRIPTION:
XS GIS Cut Line= 4
      1502786.33       837159.94      1502523.60       837202.49
      1502399.63       837191.39      1502103.56       837180.28
#Sta/Elev= 30
  4643.0  812.85  4695.5  809.41  4714.8  809.24  4736.3  807.92  4763.4  807.95
  4792.7  805.50  4812.0  804.85  4822.4  803.88  4833.2  801.08  4848.6  799.12
  4857.6  796.71  4873.7  799.01  4925.8  794.44  4977.0  793.21  4991.5  787.01
  5008.5  787.01  5023.0  793.91  5048.6  797.55  5075.1  798.38  5085.3  797.74
  5113.7  799.82  5123.3  802.71  5140.3  803.79  5153.8  807.78  5166.8  810.13
  5191.2  810.94  5266.2  818.07  5281.1  818.39  5289.5  819.78  5329.9  821.53
#Mann=4,-1,0
  4643.0    0.14       0  4857.6    0.08       0  4977.0   0.045       0
  5023.0    0.08       0
#XS Ineff=2,0
    0.00 4964.00  799.57 5036.00    0.00  799.51
Permanent Ineff=
       F       F
Bank Sta=4977,5023
XS Rating Curve= 0
Exp/Cntr=0.5,0.3

Type RM Length L Ch R =2,166189,,,
BEGIN DESCRIPTION:
Amber Hill Rd (DC) tor
Structure ID: LDS_DC_16
Approximate Survey Structure
END DESCRIPTION:
Bridge Culvert--1,0,-1,-1,0
Deck Dist Width WeirC Skew NumUp NumDn MinLoCord MaxHiCord MaxSubmerge Is_Ogee
26,58,3,,15,15,,,0.95,0,1,1,,,
  4566.2  4596.5  4698.5  4726.0  4823.8  4903.3  4944.5  4969.5  5036.0  5059.7
  5074.6  5080.2  5104.0  5148.6  5322.6
  813.59  812.10  808.55  807.04  803.00  800.78  799.64  799.51  799.51  799.96
  800.35  800.67  801.97  805.60  822.69
  767.01  767.01  767.01  767.01  767.01  767.01  767.01  767.01  767.01  767.01
  767.01  767.01  767.01  767.01  767.01
  4566.2  4596.5  4698.5  4726.0  4823.8  4903.3  4944.5  4969.5  5036.0  5059.7
  5074.6  5080.2  5104.0  5148.6  5322.6
  813.59  812.10  808.55  807.04  803.00  800.78  799.64  799.51  799.51  799.96
  800.35  800.67  801.97  805.60  822.69
  766.72  766.72  766.72  766.72  766.72  766.72  766.72  766.72  766.72  766.72
  766.72  766.72  766.72  766.72  766.72
Culvert=1,6,,58,0.024,0.9,1,2,3,787.01,4993,786.72,4993,Culvert #1,0,26
Culvert Bottom n=0.024
Culvert Bottom Depth=0
Culvert Depth Blocked=0
Culvert=1,6,,58,0.024,0.9,1,2,3,787.31,5000,786.72,5000,Culvert #2,0,26
Culvert Bottom n=0.024
Culvert Bottom Depth=0
Culvert Depth Blocked=0
Culvert=1,6,,58,0.024,0.9,1,2,3,787.51,5007,786.72,5007,Culvert #3,0,26
Culvert Bottom n=0.024
Culvert Bottom Depth=0
Culvert Depth Blocked=0
BC Design=,,0,,0,,,,,,

Type RM Length L Ch R = 1,166108,244,244,244
BEGIN DESCRIPTION:
Amber Hill Rd (DC) ds
END DESCRIPTION:
XS GIS Cut Line= 5
      1502834.48       837063.71      1502625.37       837067.41
      1502468.09       837060.01      1502279.36       837071.11
      1502101.74       837113.67
#Sta/Elev= 30
  4587.6  811.74  4672.6  808.13  4716.4  806.97  4776.6  807.15  4811.1  805.52
  4865.3  799.61  4892.5  795.01  4913.0  794.00  4947.9  794.16  4977.0  793.23
  4991.5  786.72  5008.5  786.72  5023.0  793.62  5024.4  795.03  5033.0  794.67
  5038.1  796.11  5050.3  795.36  5056.2  794.26  5077.3  793.23  5153.7  794.68
  5165.7  796.82  5178.1  800.04  5186.7  805.01  5201.8  810.08  5203.3  811.16
  5215.3  813.53  5228.6  814.96  5251.5  817.42  5285.2  822.76  5325.9  824.38
#Mann=4,-1,0
  4587.6    0.14       0  4977.0   0.045       0  5023.0    0.14       0
  5228.6    0.08       0
#XS Ineff=2,0
    0.00 4938.00  794.00 5062.00    0.00  794.00
Permanent Ineff=
       F       F
Bank Sta=4977,5023
XS Rating Curve= 0
Exp/Cntr=0.5,0.3

Type RM Length L Ch R = 1,165864,313,313,313
BEGIN DESCRIPTION:
Dutchman Creek 195.0
END DESCRIPTION:
XS GIS Cut Line= 4
      1503061.60       836936.81      1502775.13       836901.00
      1502337.49       836833.36      1502182.28       836837.34
#Sta/Elev= 30
  4313.0  826.45  4320.4  825.68  4333.8  826.12  4343.7  824.30  4435.4  814.52
  4539.7  808.04  4607.6  805.36  4671.9  800.89  4717.5  799.74  4788.5  795.81
  4810.2  793.36  4821.2  793.46  4861.3  791.05  4874.8  791.23  4980.1  792.53
  4996.8  786.63  4997.8  784.63  5002.2  784.63  5003.2  786.63  5004.6  785.62
  5010.0  785.58  5021.7  794.14  5040.7  794.60  5047.3  796.21  5071.8  795.71
  5087.4  797.74  5135.4  809.02  5147.8  812.96  5180.0  820.79  5199.8  824.43
#Mann=5,-1,0
  4313.0    0.14       0  4717.5    0.06       0  4874.8    0.14       0
  4996.8   0.045       0  5003.2    0.14       0
Bank Sta=4996.8,5003.2
XS Rating Curve= 0
Exp/Cntr=0.3,0.1

Type RM Length L Ch R = 1,165551,551,551,551
BEGIN DESCRIPTION:
Dutchman Creek 194.0
END DESCRIPTION:
XS GIS Cut Line= 4
      1503105.33       836777.65      1502695.56       836590.67
      1502389.21       836534.97      1502289.76       836411.66
#Sta/Elev= 30
  4312.8  821.31  4327.6  819.77  4365.0  818.75  4421.9  815.87  4457.6  811.95
  4507.8  808.53  4519.8  806.06  4569.6  805.23  4635.1  800.59  4698.4  799.52
  4779.3  789.97  4860.2  790.29  4914.7  787.51  4959.3  789.64  4980.6  790.75
  4987.2  790.41  4991.7  789.30  4996.8  784.77  4997.8  782.77  5002.2  782.77
  5003.2  784.77  5008.8  785.43  5013.5  787.73  5024.7  791.54  5075.2  798.94
  5111.5  808.47  5125.2  811.04  5193.3  821.12  5223.8  824.60  5233.0  824.95
#Mann=5,-1,0
  4312.8    0.14       0  4365.0    0.06       0  4959.3    0.14       0
  4996.8   0.045       0  5003.2    0.14       0
Bank Sta=4996.8,5003.2
XS Rating Curve= 0
Exp/Cntr=0.3,0.1

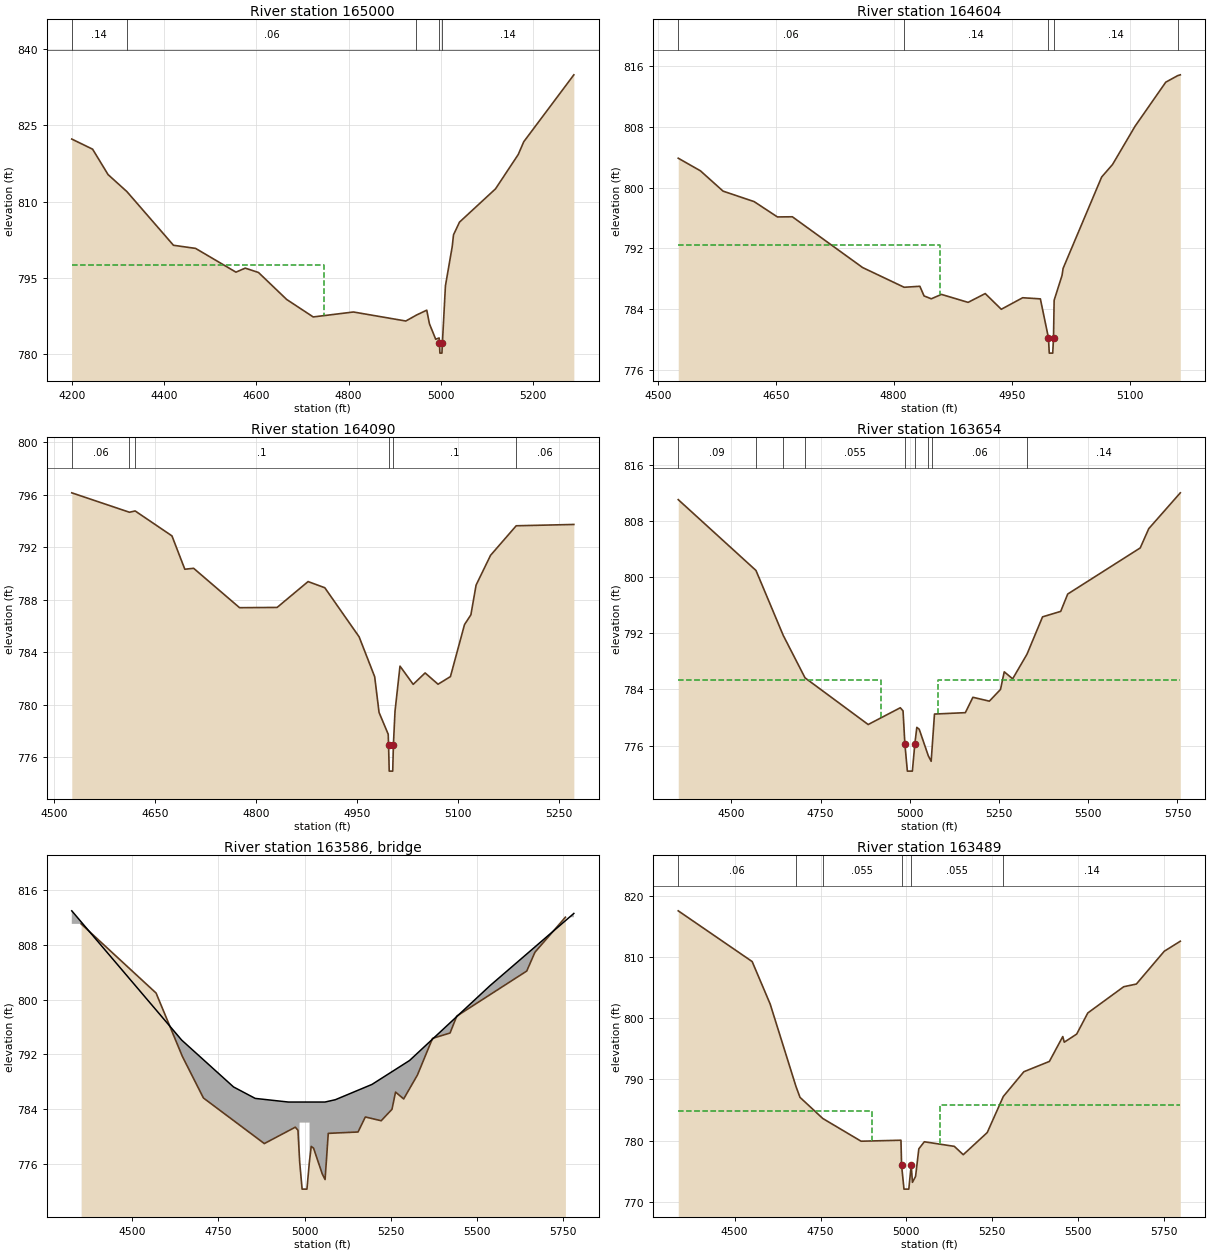
Type RM Length L Ch R = 1,165000,396,396,396
BEGIN DESCRIPTION:
Dutchman Creek 193.0
END DESCRIPTION:
XS GIS Cut Line= 4
      1503232.64       836586.67      1502822.11       836297.24
      1502618.62       836079.40      1502552.33       835798.93
#Sta/Elev= 30
  4199.6  822.31  4244.8  820.32  4278.3  815.33  4319.2  811.98  4420.1  801.44
  4468.0  800.83  4555.6  796.16  4575.7  796.95  4604.5  796.09  4665.6  790.79
  4723.1  787.36  4810.4  788.33  4923.9  786.56  4946.8  787.72  4969.3  788.69
  4975.1  786.01  4988.7  782.98  4996.1  783.23  4996.8  782.25  4997.8  780.25
  5002.2  780.25  5003.2  782.25  5009.8  793.48  5024.5  801.18  5027.3  803.50
  5040.3  805.99  5118.4  812.53  5167.6  819.27  5179.6  821.78  5288.2  834.93
#Mann=5,-1,0
  4199.6    0.14       0  4319.2    0.06       0  4946.8    0.14       0
  4996.8   0.045       0  5003.2    0.14       0
#XS Ineff=2,0
    0.00 4745.70  797.57               0
Permanent Ineff=
       F       F
Bank Sta=4996.8,5003.2
XS Rating Curve= 0
Exp/Cntr=0.3,0.1

Type RM Length L Ch R = 1,164604,514,514,514
BEGIN DESCRIPTION:
Dutchman Creek 192.0
END DESCRIPTION:
XS GIS Cut Line= 4
      1503297.84       836151.15      1503101.10       835957.00
      1502899.15       835832.72      1502816.26       835739.48
#Sta/Elev= 30
  4526.1  803.88  4554.3  802.22  4583.1  799.54  4622.6  798.16  4652.2  796.14
  4671.2  796.16  4760.5  789.47  4813.3  786.87  4833.3  787.00  4838.6  785.73
  4847.8  785.35  4860.7  785.93  4894.6  784.88  4916.4  786.04  4936.8  783.97
  4964.0  785.49  4986.5  785.34  4996.8  780.19  4997.8  778.19  5002.2  778.19
  5003.2  780.19  5004.0  785.16  5014.0  788.42  5015.4  789.36  5064.4  801.40
  5078.3  803.06  5106.9  808.10  5145.9  813.90  5161.0  814.76  5164.4  814.87
#Mann=5,-1,0
  4526.1    0.06       0  4813.3    0.14       0  4996.8   0.045       0
  5003.2    0.14       0  5161.0    0.06       0
#XS Ineff=2,0
    0.00 4859.20  792.44               0
Permanent Ineff=
       F       F
Bank Sta=4996.8,5003.2
XS Rating Curve= 0
Exp/Cntr=0.3,0.1

Type RM Length L Ch R = 1,164090,436,436,436
BEGIN DESCRIPTION:
Dutchman Creek 191.0
END DESCRIPTION:
XS GIS Cut Line= 6
      1503269.40       836001.02      1503251.27       835752.45
      1503316.00       835643.71      1503339.31       835576.39
      1503341.89       835439.16      1503235.77       835317.51
#Sta/Elev= 30
  4525.9  796.13  4611.6  794.65  4620.0  794.75  4674.7  792.85  4693.8  790.31
  4706.9  790.38  4775.1  787.38  4830.9  787.40  4876.9  789.37  4901.7  788.90
  4952.7  785.16  4975.8  782.12  4982.3  779.40  4995.9  777.74  4996.4  776.93
  4997.4  774.93  5002.6  774.93  5003.6  776.93  5006.0  779.49  5013.4  782.93
  5033.0  781.54  5050.7  782.41  5069.9  781.55  5088.3  782.13  5109.2  786.09
  5118.7  786.84  5126.4  789.10  5147.9  791.37  5186.0  793.62  5271.6  793.72
#Mann=6,-1,0
  4525.9    0.06       0  4611.6    0.09       0  4620.0     0.1       0
  4996.4   0.045       0  5003.6     0.1       0  5186.0    0.06       0
Bank Sta=4996.4,5003.6
XS Rating Curve= 0
Exp/Cntr=0.5,0.3

Type RM Length L Ch R = 1,163654,165,165,165
BEGIN DESCRIPTION:
Ollie Harkey Rd (DC) us
END DESCRIPTION:
XS GIS Cut Line= 6
      1503980.67       835974.01      1503893.12       835882.48
      1503773.76       835580.11      1503682.25       835154.40
      1503638.49       834983.32      1503387.81       834748.56
#Sta/Elev= 30
  4350.8  811.03  4568.7  800.94  4645.1  791.69  4706.2  785.64  4883.2  778.99
  4973.2  781.38  4980.9  780.93  4986.0  776.25  4993.0  772.35  5007.0  772.35
  5014.0  776.25  5019.5  778.58  5026.2  778.32  5051.6  774.55  5059.7  773.75
  5062.1  775.47  5069.0  780.48  5155.5  780.68  5176.7  782.87  5222.8  782.32
  5254.1  783.99  5264.5  786.50  5288.1  785.50  5328.3  789.01  5371.9  794.33
  5422.8  795.11  5442.4  797.58  5645.7  804.15  5669.5  806.89  5758.0  812.00
#Mann=9,-1,0
  4350.8    0.09       0  4568.7    0.06       0  4645.1    0.12       0
  4706.2   0.055       0  4986.0   0.045       0  5014.0    0.06       0
  5051.6    0.05       0  5062.1    0.06       0  5328.3    0.14       0
#XS Ineff=2,0
    0.00 4920.00  785.29 5080.00    0.00  785.36
Permanent Ineff=
       F       F
Bank Sta=4986,5014
XS Rating Curve= 0
Exp/Cntr=0.5,0.3

Type RM Length L Ch R =3,163586,,,
BEGIN DESCRIPTION:
Ollie Harkey Rd (DC) tor
Structure ID: LDS_DC_15
Approximate Survey Structure
END DESCRIPTION:
Bridge Culvert--1,0,-1,-1,0
Deck Dist Width WeirC Skew NumUp NumDn MinLoCord MaxHiCord MaxSubmerge Is_Ogee
55.5,25,3,,15,15,,,0.95,0,1,1,,,
  4323.7  4643.1  4793.7  4856.7  4952.9  4985.5  4985.5  5014.5  5014.5  5059.4
  5089.6  5196.0  5305.2  5538.9  5782.5
  812.93  794.08  787.25  785.58  785.05  785.05  785.05  785.05  785.05  785.05
  785.39  787.62  791.11  802.02  812.55
  752.35  752.35  752.35  752.35  752.35  752.35  782.05  782.05  752.35  752.35
  752.35  752.35  752.35  752.35  752.35
  4323.7  4643.1  4793.7  4856.7  4952.9  4985.5  4985.5  5014.5  5014.5  5059.4
  5089.6  5196.0  5305.2  5538.9  5782.5
  812.93  794.08  787.25  785.58  785.05  785.05  785.05  785.05  785.05  785.05
  785.39  787.62  791.11  802.02  812.55
  752.35  752.35  752.35  752.35  752.35  752.35  782.05  782.05  752.35  752.35
  752.35  752.35  752.35  752.35  752.35
Abutment Skew #Up #Dn=,2,2
  4985.5  4986.5
  782.05  775.97
  4985.5  4986.5
  782.05  775.72
Abutment Skew #Up #Dn=,2,2
  5013.5  5014.5
  775.97  782.05
  5013.5  5014.5
  775.72  782.05
BR Coef=1,1,0,1.25,0,,,0.8,0,2,0,
WSPro=,,,, 1 ,,,, 0 ,,,, 0 ,,,,-1 ,-1 ,-1 , 0 , 0 , 0 , 0 , 0
BC Design=,,0,,0,,,,,,

Type RM Length L Ch R = 1,163489,334,334,334
BEGIN DESCRIPTION:
Ollie Harkey Rd (DC) ds
END DESCRIPTION:
XS GIS Cut Line= 5
      1504127.83       835930.19      1503972.69       835711.40
      1503825.48       835118.59      1503753.86       834999.24
      1503415.70       834712.79
#Sta/Elev= 30
  4335.9  817.52  4551.1  809.24  4603.5  802.31  4678.7  788.84  4690.3  787.08
  4756.6  783.63  4868.1  779.92  4984.2  780.08  4986.0  776.00  4993.0  772.10
  5007.0  772.10  5014.0  776.00  5017.6  773.21  5026.7  774.17  5036.2  778.68
  5052.2  779.83  5139.5  779.08  5165.5  777.72  5235.3  781.33  5282.1  787.22
  5341.9  791.26  5416.2  792.94  5455.2  797.00  5459.5  796.08  5495.6  797.40
  5528.0  800.85  5632.5  805.13  5669.4  805.57  5750.5  810.92  5797.3  812.56
#Mann=6,-1,0
  4335.9    0.06       0  4678.7    0.12       0  4756.6   0.055       0
  4986.0   0.045       0  5014.0   0.055       0  5282.1    0.14       0
#XS Ineff=2,0
    0.00 4901.00  784.93 5099.00    0.00  785.78
Permanent Ineff=
       F       F
Bank Sta=4986,5014
XS Rating Curve= 0
Exp/Cntr=0.5,0.3

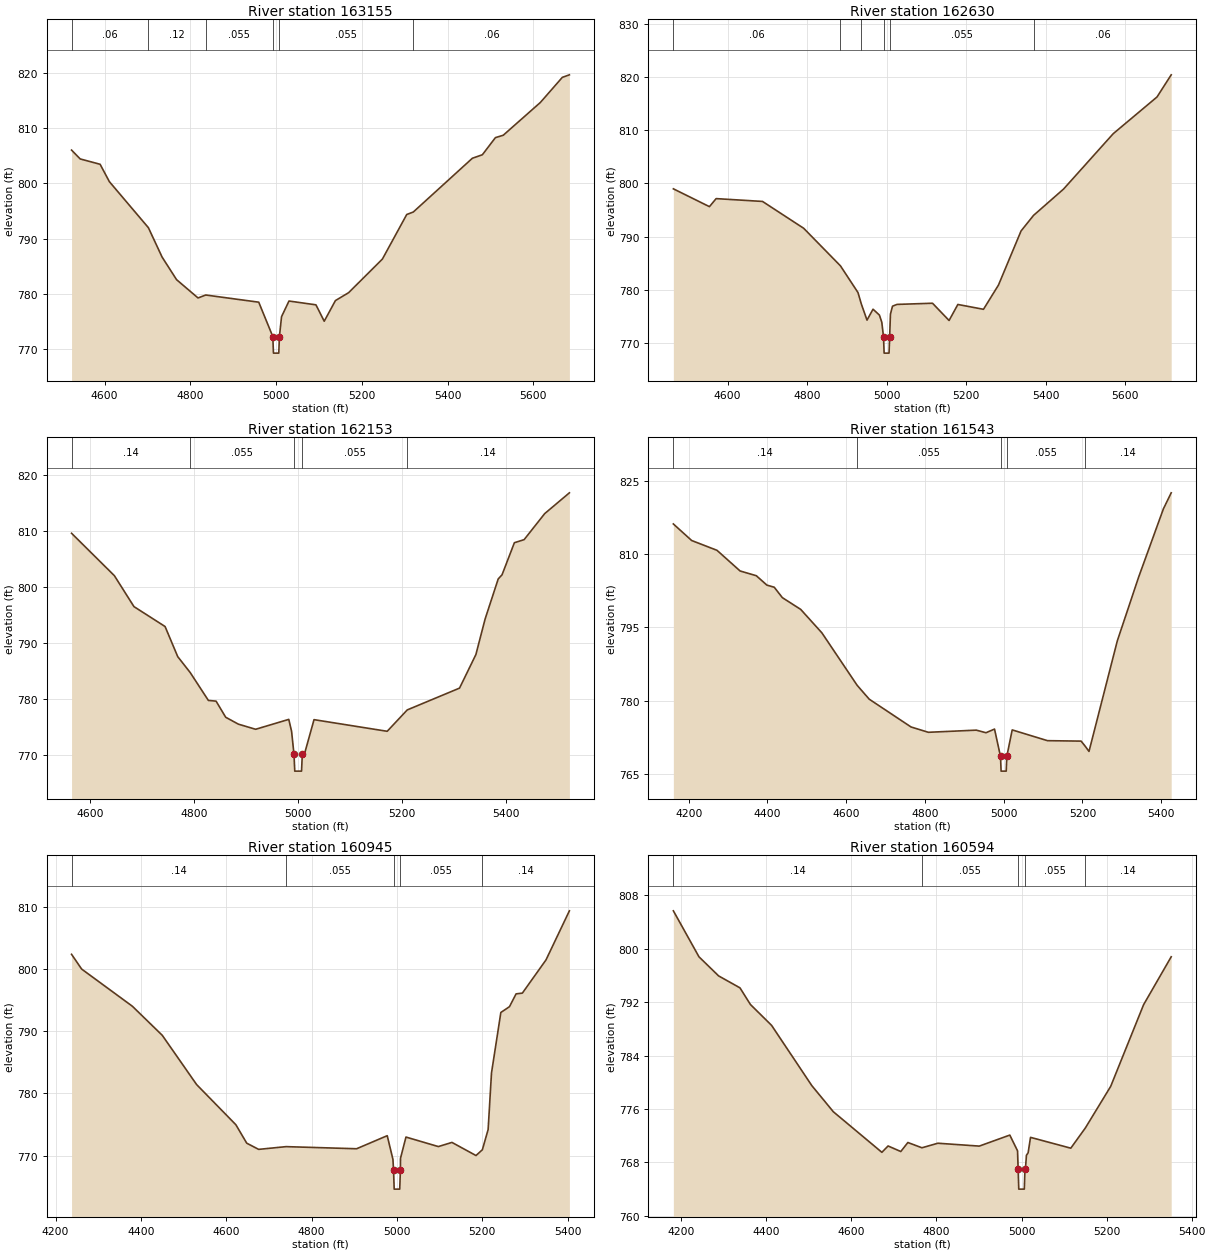
Type RM Length L Ch R = 1,163155,525,525,525
BEGIN DESCRIPTION:
Dutchman Creek 190.0
END DESCRIPTION:
XS GIS Cut Line= 4
      1504342.69       835468.70      1504231.30       835214.08
      1503956.77       834939.56      1503726.02       834501.92
#Sta/Elev= 30
  4523.0  806.02  4543.1  804.42  4589.6  803.45  4611.2  800.30  4702.2  791.96
  4734.1  786.64  4767.9  782.54  4817.9  779.23  4836.0  779.76  4959.5  778.46
  4992.3  772.23  4993.8  769.23  5006.2  769.23  5007.7  772.23  5012.7  775.84
  5030.0  778.67  5092.9  777.98  5112.2  775.01  5138.3  778.75  5169.2  780.19
  5247.9  786.28  5304.6  794.35  5319.9  794.80  5457.6  804.54  5481.0  805.18
  5511.4  808.28  5529.6  808.71  5616.2  814.65  5667.4  819.20  5683.9  819.66
#Mann=6,-1,0
  4523.0    0.06       0  4702.2    0.12       0  4836.0   0.055       0
  4992.3   0.045       0  5007.7   0.055       0  5319.9    0.06       0
Bank Sta=4992.3,5007.7
XS Rating Curve= 0
Exp/Cntr=0.3,0.1

Type RM Length L Ch R = 1,162630,477,477,477
BEGIN DESCRIPTION:
Dutchman Creek 189.0
END DESCRIPTION:
XS GIS Cut Line= 6
      1504537.65       835253.83      1504553.56       834959.45
      1504541.63       834820.20      1504326.78       834501.91
      1504203.45       834394.49      1504068.16       834159.73
#Sta/Elev= 30
  4463.3  799.00  4554.1  795.65  4571.0  797.16  4687.7  796.63  4791.3  791.59
  4883.9  784.53  4928.0  779.52  4936.4  777.38  4950.7  774.34  4965.9  776.39
  4982.0  775.28  4988.0  773.93  4992.3  771.14  4993.8  768.14  5006.2  768.14
  5007.7  771.14  5009.7  775.46  5014.9  776.96  5026.2  777.29  5115.6  777.51
  5157.3  774.27  5179.4  777.28  5243.9  776.37  5281.6  780.92  5338.5  791.09
  5369.9  794.01  5445.4  798.95  5570.4  809.35  5680.7  816.25  5716.4  820.41
#Mann=6,-1,0
  4463.3    0.06       0  4883.9    0.12       0  4936.4   0.055       0
  4992.3   0.045       0  5007.7   0.055       0  5369.9    0.06       0
Bank Sta=4992.3,5007.7
XS Rating Curve= 0
Exp/Cntr=0.3,0.1

Type RM Length L Ch R = 1,162153,610,610,610
BEGIN DESCRIPTION:
Dutchman Creek 188.0
END DESCRIPTION:
XS GIS Cut Line= 4
      1505178.22       834828.19      1504999.16       834613.31
      1504704.75       834406.43      1504609.27       834104.08
#Sta/Elev= 30
  4564.6  809.56  4646.9  801.98  4684.5  796.45  4744.3  792.89  4768.6  787.51
  4792.6  784.66  4827.5  779.68  4842.3  779.55  4860.8  776.67  4885.1  775.44
  4918.3  774.52  4982.0  776.29  4987.4  774.15  4992.0  770.04  4993.5  767.04
  5006.5  767.04  5008.0  770.04  5012.3  770.16  5030.5  776.24  5171.1  774.16
  5209.6  777.98  5310.1  781.88  5341.5  787.87  5359.2  794.22  5384.4  801.39
  5391.8  802.14  5415.5  807.87  5434.2  808.42  5473.7  813.07  5521.2  816.79
#Mann=5,-1,0
  4564.6    0.14       0  4792.6   0.055       0  4992.0   0.045       0
  5008.0   0.055       0  5209.6    0.14       0
Bank Sta=4992,5008
XS Rating Curve= 0
Exp/Cntr=0.3,0.1

Type RM Length L Ch R = 1,161543,598,598,598
BEGIN DESCRIPTION:
Dutchman Creek 187.0
END DESCRIPTION:
XS GIS Cut Line= 5
      1505822.74       834350.74      1505607.89       834159.75
      1505345.30       834016.52      1504836.04       833921.04
      1504676.94       833905.13
#Sta/Elev= 30
  4161.0  816.13  4207.5  812.75  4271.8  810.75  4330.5  806.53  4371.7  805.56
  4398.6  803.64  4417.2  803.21  4437.9  801.08  4484.5  798.68  4538.3  793.89
  4627.9  783.17  4658.6  780.34  4764.7  774.67  4808.7  773.58  4930.5  774.02
  4955.1  773.49  4976.8  774.24  4992.0  768.65  4993.5  765.65  5006.5  765.65
  5008.0  768.65  5021.7  774.07  5111.4  771.87  5196.7  771.78  5205.5  770.91
  5216.8  769.68  5288.7  792.25  5342.8  805.26  5405.8  819.22  5425.6  822.49
#Mann=5,-1,0
  4161.0    0.14       0  4627.9   0.055       0  4992.0   0.045       0
  5008.0   0.055       0  5205.5    0.14       0
Bank Sta=4992,5008
XS Rating Curve= 0
Exp/Cntr=0.3,0.1

Type RM Length L Ch R = 1,160945,351,351,351
BEGIN DESCRIPTION:
Dutchman Creek 186.0
END DESCRIPTION:
XS GIS Cut Line= 4
      1505946.03       833666.39      1505552.19       833447.59
      1505011.10       833356.08      1504844.01       833356.08
#Sta/Elev= 30
  4237.6  802.36  4261.2  799.99  4380.1  794.01  4450.1  789.34  4530.6  781.42
  4622.6  774.96  4648.0  772.00  4675.9  771.00  4740.2  771.44  4905.4  771.10
  4977.2  773.20  4990.6  769.38  4992.0  767.61  4993.5  764.61  5006.5  764.61
  5008.0  767.61  5008.3  769.57  5021.1  772.98  5097.0  771.45  5128.8  772.12
  5185.2  770.01  5200.1  770.94  5213.6  774.19  5221.5  783.29  5243.4  793.01
  5263.6  793.94  5279.1  796.00  5293.8  796.12  5349.2  801.46  5404.0  809.35
#Mann=5,-1,0
  4237.6    0.14       0  4740.2   0.055       0  4992.0   0.045       0
  5008.0   0.055       0  5200.1    0.14       0
Bank Sta=4992,5008
XS Rating Curve= 0
Exp/Cntr=0.3,0.1

Type RM Length L Ch R = 1,160594,322,322,322
BEGIN DESCRIPTION:
Dutchman Creek 185.0
END DESCRIPTION:
XS GIS Cut Line= 4
      1506009.69       833630.57      1505727.24       833312.31
      1505245.84       833005.96      1505118.56       832886.64
#Sta/Elev= 30
  4181.3  805.66  4241.6  798.77  4287.7  795.92  4337.9  794.13  4362.5  791.64
  4412.3  788.51  4506.8  779.50  4557.5  775.58  4671.6  769.51  4686.2  770.46
  4716.1  769.63  4732.7  770.98  4765.8  770.19  4803.2  770.87  4900.6  770.44
  4972.4  772.09  4990.6  769.73  4992.0  767.00  4993.5  764.00  5006.5  764.00
  5008.0  767.00  5009.4  767.23  5011.5  769.07  5015.5  769.44  5021.1  771.75
  5115.8  770.13  5150.2  773.17  5209.6  779.38  5287.0  791.61  5351.9  798.78
#Mann=5,-1,0
  4181.3    0.14       0  4765.8   0.055       0  4992.0   0.045       0
  5008.0   0.055       0  5150.2    0.14       0
Bank Sta=4992,5008
XS Rating Curve= 0
Exp/Cntr=0.3,0.1