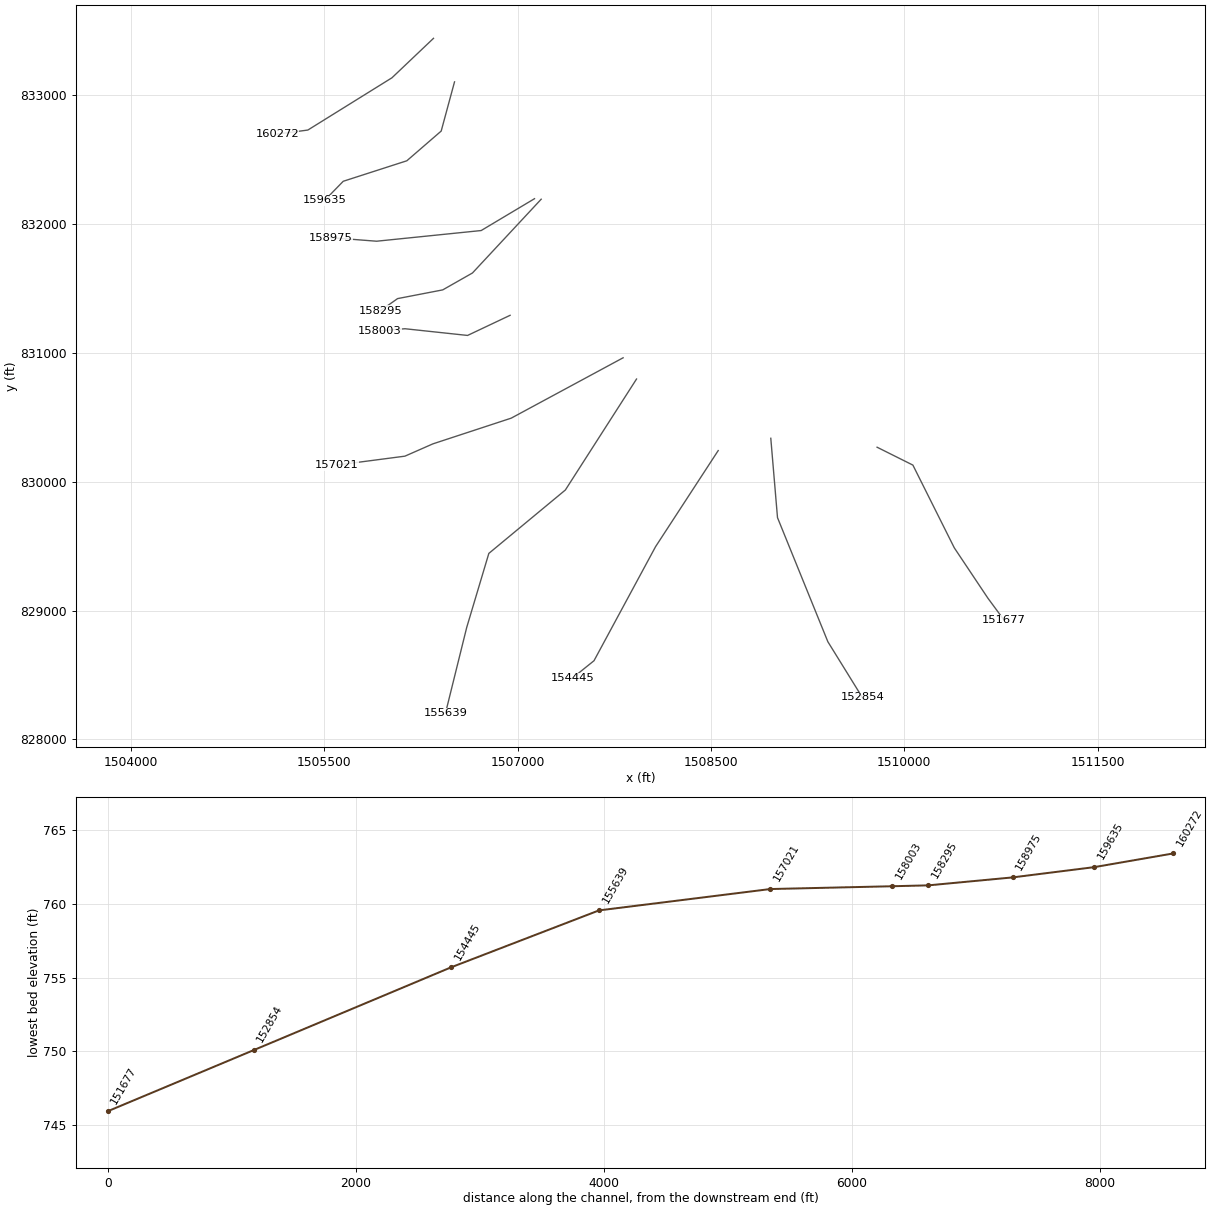
HEC-RAS study Dutchman Creek.prj: Dutchman Creek Limited Detail Study

--- Dutchman Creek.g01 (geometry) --- (continued)

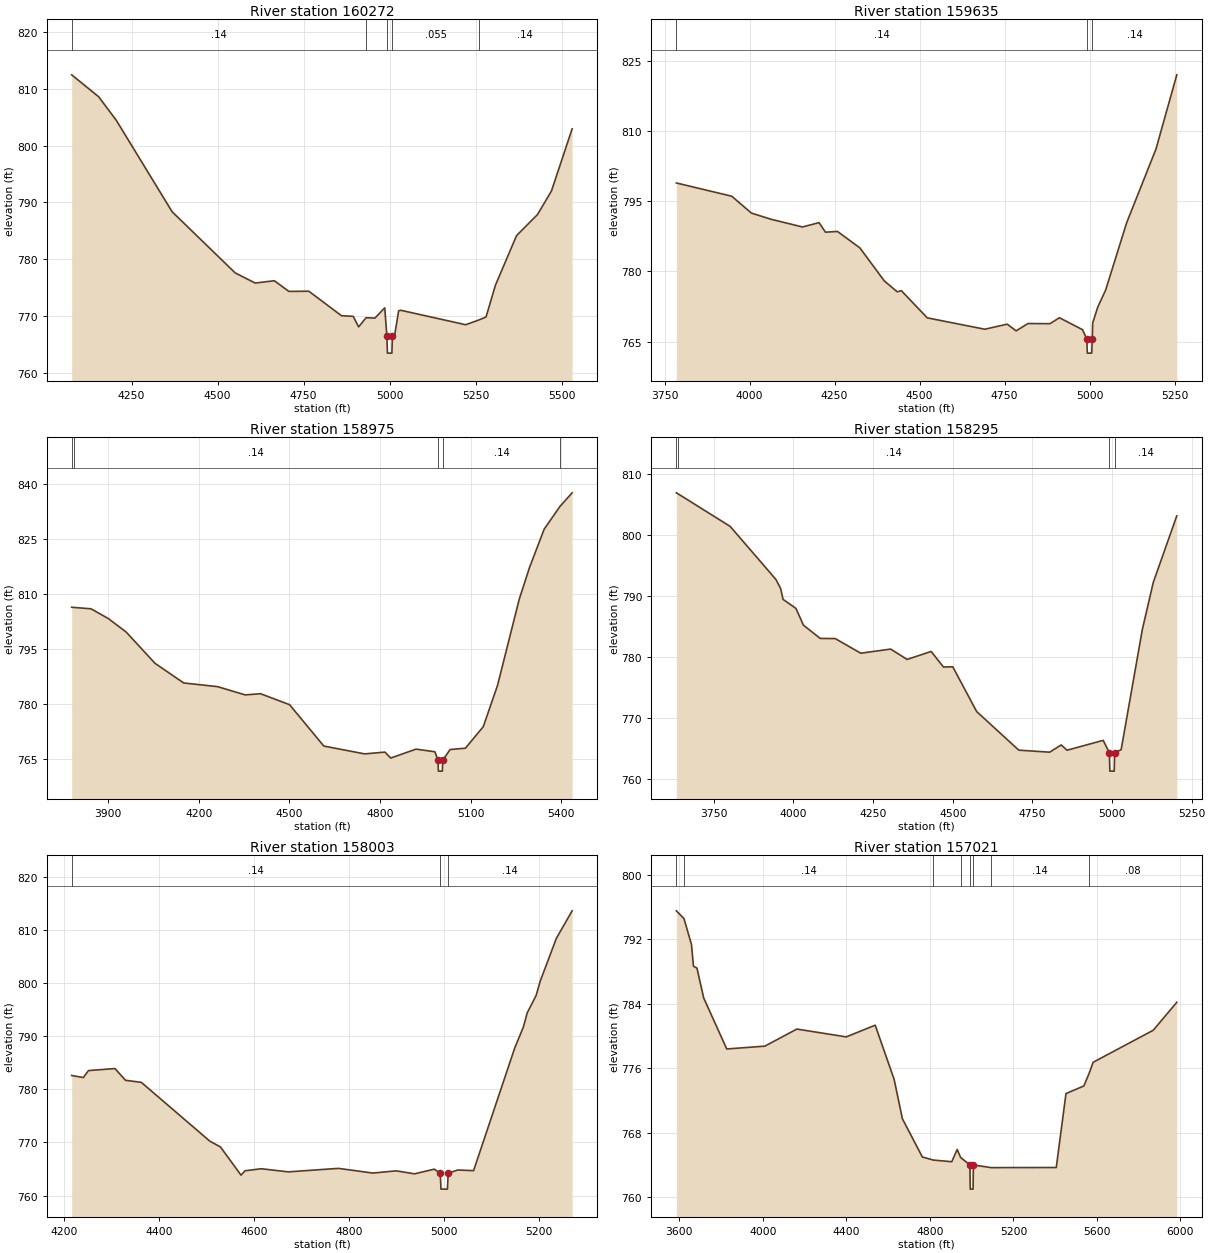
Type RM Length L Ch R = 1,160272,637,637,637
BEGIN DESCRIPTION:
Dutchman Creek 184.0
END DESCRIPTION:
XS GIS Cut Line= 4
      1506347.92       833443.62      1506025.64       833137.26
      1505373.15       832731.44      1505134.41       832699.61
#Sta/Elev= 30
  4076.2  812.45  4154.4  808.60  4205.8  804.44  4368.1  788.33  4551.2  777.57
  4609.3  775.78  4664.9  776.19  4707.2  774.31  4765.3  774.34  4860.0  770.03
  4894.2  769.92  4909.8  768.06  4931.6  769.68  4957.0  769.60  4985.7  771.41
  4992.0  766.44  4993.5  763.44  5006.5  763.44  5008.0  766.44  5014.3  766.52
  5026.1  770.89  5032.1  770.99  5220.9  768.44  5258.4  769.26  5280.0  769.80
  5307.2  775.39  5368.7  784.14  5429.6  787.85  5470.1  792.00  5530.1  802.93
#Mann=5,-1,0
  4076.2    0.14       0  4931.6   0.055       0  4992.0   0.045       0
  5008.0   0.055       0  5258.4    0.14       0
Bank Sta=4992,5008
XS Rating Curve= 0
Exp/Cntr=0.3,0.1

Type RM Length L Ch R = 1,159635,660,660,660
BEGIN DESCRIPTION:
Dutchman Creek 183.0
END DESCRIPTION:
XS GIS Cut Line= 5
      1506511.03       833105.44      1506407.58       832723.48
      1506141.02       832492.73      1505647.67       832333.58
      1505504.41       832186.34
#Sta/Elev= 30
  3784.6  798.97  3947.6  796.13  4005.4  792.52  4063.2  791.19  4155.5  789.54
  4204.5  790.47  4223.1  788.43  4258.6  788.58  4324.6  785.05  4396.1  778.00
  4434.3  775.65  4446.6  775.88  4522.7  770.07  4691.9  767.63  4758.0  768.72
  4784.1  767.28  4818.9  768.85  4883.6  768.82  4911.5  770.09  4979.4  767.54
  4992.0  765.51  4993.5  762.51  5006.5  762.51  5008.0  765.51  5009.3  768.96
  5024.2  772.37  5047.5  776.04  5109.2  790.44  5195.4  806.22  5256.7  822.14
#Mann=3,-1,0
  3784.6    0.14       0  4992.0   0.045       0  5008.0    0.14       0
Bank Sta=4992,5008
XS Rating Curve= 0
Exp/Cntr=0.3,0.1

Type RM Length L Ch R = 1,158975,680,680,680
BEGIN DESCRIPTION:
Dutchman Creek 182.0
END DESCRIPTION:
XS GIS Cut Line= 4
      1507131.65       832198.29      1506717.85       831951.00
      1505906.28       831868.09      1505548.21       831895.94
#Sta/Elev= 30
  3779.3  806.50  3788.5  806.44  3843.4  806.08  3900.6  803.42  3959.5  799.76
  4055.0  791.23  4150.3  785.85  4262.4  784.85  4353.8  782.60  4404.6  782.92
  4500.8  779.93  4614.1  768.65  4749.3  766.51  4816.4  767.00  4835.7  765.38
  4919.5  767.81  4982.0  767.09  4992.0  764.81  4993.5  761.81  5006.5  761.81
  5008.0  764.81  5032.4  767.70  5082.9  768.06  5142.1  773.93  5189.3  785.19
  5261.2  808.69  5295.1  817.31  5343.6  827.78  5396.3  834.02  5436.3  837.71
#Mann=5,-1,0
  3779.3    0.08       0  3788.5    0.14       0  4992.0   0.045       0
  5008.0    0.14       0  5396.3    0.06       0
Bank Sta=4992,5008
XS Rating Curve= 0
Exp/Cntr=0.3,0.1

Type RM Length L Ch R = 1,158295,292,292,292
BEGIN DESCRIPTION:
Dutchman Creek 181.0
END DESCRIPTION:
XS GIS Cut Line= 5
      1507183.41       832194.33      1506650.28       831621.41
      1506419.52       831490.12      1506069.40       831422.48
      1505934.10       831326.98
#Sta/Elev= 30
  3632.9  806.94  3637.3  806.81  3801.8  801.43  3945.6  792.71  3960.2  791.22
  3967.8  789.45  4008.1  787.98  4031.7  785.22  4084.3  783.05  4131.5  783.02
  4211.6  780.62  4305.3  781.30  4357.1  779.60  4432.4  780.91  4471.0  778.36
  4500.3  778.39  4575.2  771.05  4707.4  764.71  4804.3  764.38  4840.5  765.57
  4858.8  764.70  4972.3  766.32  4991.7  764.27  4993.2  761.27  5006.8  761.27
  5008.3  764.27  5028.6  764.79  5095.3  784.56  5129.5  792.26  5203.2  803.16
#Mann=4,-1,0
  3632.9    0.08       0  3637.3    0.14       0  4991.7   0.045       0
  5008.3    0.14       0
Bank Sta=4991.7,5008.3
XS Rating Curve= 0
Exp/Cntr=0.3,0.1

Type RM Length L Ch R = 1,158003,982,982,982
BEGIN DESCRIPTION:
Dutchman Creek 180.0
END DESCRIPTION:
XS GIS Cut Line= 4
      1506942.16       831292.64      1506612.30       831136.39
      1506126.19       831188.47      1505926.53       831171.11
#Sta/Elev= 30
  4215.2  782.61  4239.8  782.23  4250.6  783.54  4306.4  783.92  4328.6  781.71
  4361.9  781.32  4506.5  770.23  4528.6  769.16  4571.9  763.85  4580.6  764.67
  4614.7  765.05  4671.5  764.46  4777.1  765.12  4849.5  764.24  4899.0  764.65
  4937.5  764.09  4979.1  764.97  4991.7  764.21  4993.2  761.21  5006.8  761.21
  5008.3  764.21  5028.3  764.81  5061.9  764.69  5148.6  787.80  5166.6  791.69
  5174.9  794.41  5193.6  797.68  5202.1  800.34  5236.3  808.45  5269.5  813.63
#Mann=3,-1,0
  4215.2    0.14       0  4991.7   0.045       0  5008.3    0.14       0
Bank Sta=4991.7,5008.3
XS Rating Curve= 0
Exp/Cntr=0.3,0.1

Type RM Length L Ch R = 1,157021,1382,1382,1382
BEGIN DESCRIPTION:
Dutchman Creek 179.0
END DESCRIPTION:
XS GIS Cut Line= 5
      1507818.93       830962.80      1506950.84       830494.03
      1506343.20       830294.37      1506126.19       830198.89
      1505596.69       830129.45
#Sta/Elev= 30
  3585.4  795.55  3621.9  794.59  3658.0  791.36  3667.3  788.68  3684.0  788.45
  3716.5  784.73  3826.9  778.41  4009.3  778.76  4162.7  780.88  4399.4  779.91
  4538.0  781.36  4628.8  774.63  4668.2  769.75  4763.8  765.01  4815.6  764.63
  4904.7  764.42  4930.8  765.94  4947.0  764.95  4991.7  764.02  4993.2  761.02
  5006.8  761.02  5008.3  764.02  5092.4  763.69  5405.3  763.70  5451.9  772.88
  5537.5  773.82  5562.8  775.39  5582.0  776.76  5869.8  780.73  5982.7  784.20
#Mann=8,-1,0
  3585.4     0.1       0  3621.9    0.14       0  4815.6    0.06       0
  4947.0    0.06       0  4991.7   0.045       0  5008.3    0.06       0
  5092.4    0.14       0  5562.8    0.08       0
Bank Sta=4991.7,5008.3
XS Rating Curve= 0
Exp/Cntr=0.3,0.1

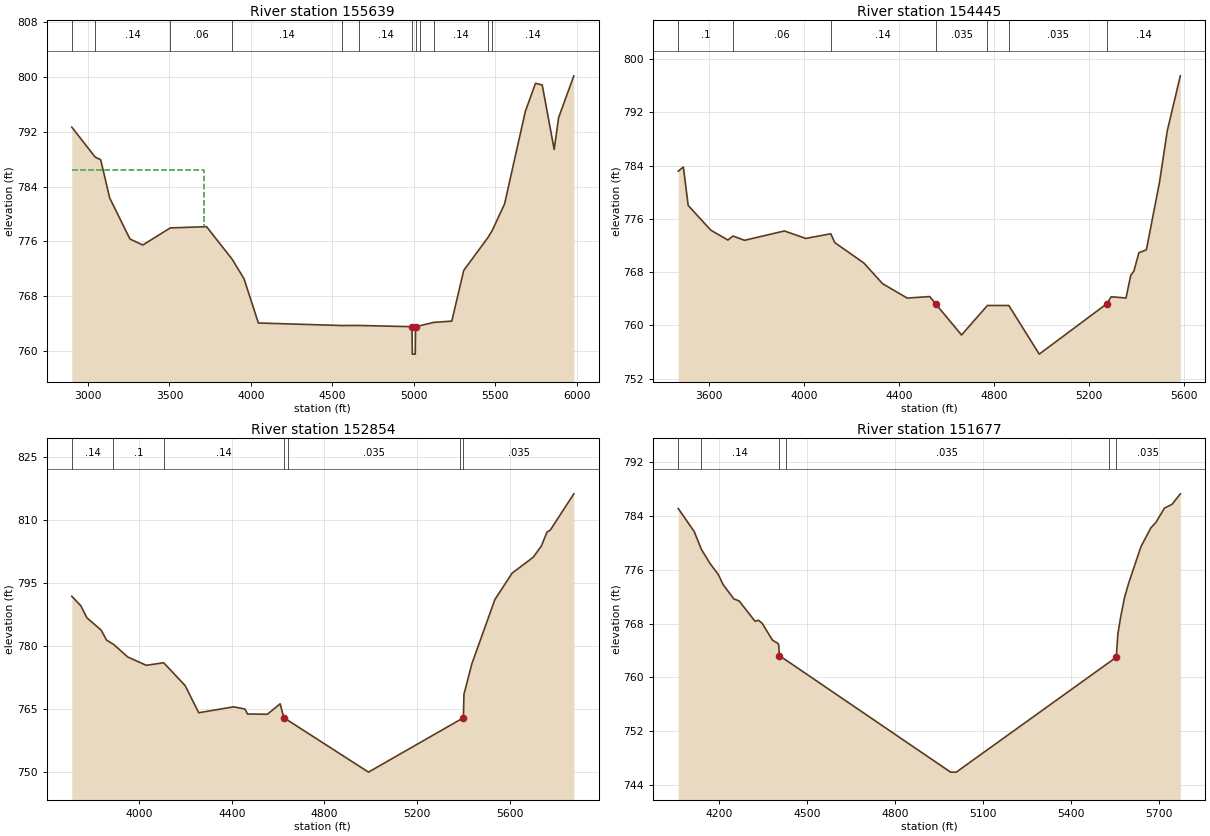
Type RM Length L Ch R = 1,155639,1194,1194,1194
BEGIN DESCRIPTION:
Dutchman Creek 178.0
END DESCRIPTION:
XS GIS Cut Line= 5
      1507923.04       830797.82      1507370.95       829936.10
      1506777.23       829443.68      1506605.71       828869.11
      1506440.51       828201.42
#Sta/Elev= 30
  2900.4  792.66  3044.0  788.30  3078.0  787.90  3133.3  782.33  3257.6  776.35
  3336.5  775.48  3505.2  777.97  3727.9  778.15  3885.4  773.39  3958.1  770.55
  4045.9  764.11  4558.3  763.74  4662.5  763.75  4989.0  763.57  4991.0  759.57
  5009.0  759.57  5011.0  763.57  5036.9  763.71  5122.7  764.20  5233.4  764.38
  5306.6  771.77  5456.0  776.59  5482.4  777.63  5557.1  781.45  5685.1  794.98
  5747.3  799.05  5788.5  798.81  5861.8  789.42  5889.3  794.06  5982.6  800.14
#Mann=12,-1,0
  2900.4     0.1       0  3044.0    0.14       0  3505.2    0.06       0
  3885.4    0.14       0  4558.3   0.035       0  4662.5    0.14       0
  4989.0   0.045       0  5011.0    0.14       0  5036.9     0.1       0
  5122.7    0.14       0  5456.0     0.1       0  5482.4    0.14       0
#XS Ineff=2,0
    0.00 3713.50  786.34               0
Permanent Ineff=
       F       F
Bank Sta=4989,5011
XS Rating Curve= 0
Exp/Cntr=0.3,0.1

Type RM Length L Ch R = 1,154445,1591,1591,1591
BEGIN DESCRIPTION:
Dutchman Creek 177.0
END DESCRIPTION:
XS GIS Cut Line= 4
      1508556.72       830242.25      1508070.63       829495.76
      1507593.20       828610.35      1507425.02       828475.02
#Sta/Elev= 30
  3472.0  783.16  3493.6  783.78  3513.9  778.01  3609.0  774.30  3681.0  772.82
  3702.6  773.42  3750.9  772.78  3918.7  774.18  4008.7  773.06  4113.9  773.76
  4130.8  772.43  4252.8  769.38  4331.8  766.27  4435.5  764.11  4530.3  764.34
  4555.0  763.25  4664.0  758.57  4773.0  763.00  4863.0  763.00  4991.0  755.70
  5275.0  763.25  5293.8  764.31  5356.1  764.12  5375.9  767.50  5389.4  768.17
  5410.3  770.91  5441.8  771.35  5497.3  781.54  5529.7  789.20  5584.6  797.46
#Mann=7,-1,0
  3472.0     0.1       0  3702.6    0.06       0  4113.9    0.14       0
  4555.0   0.035       0  4773.0    0.06       0  4863.0   0.035       0
  5275.0    0.14       0
Bank Sta=4555,5275
XS Rating Curve= 0
Exp/Cntr=0.3,0.1

Type RM Length L Ch R = 1,152854,1177,1177,1177
BEGIN DESCRIPTION:
Dutchman Creek 176.0
END DESCRIPTION:
XS GIS Cut Line= 4
      1508964.73       830337.80      1509016.81       829721.46
      1509407.44       828757.92      1509675.01       828324.98
#Sta/Elev= 30
  3709.5  791.83  3748.5  789.58  3775.2  786.69  3836.5  783.79  3859.4  781.44
  3889.6  780.42  3951.2  777.42  4031.0  775.44  4106.2  776.05  4198.8  770.63
  4257.5  764.18  4408.2  765.58  4457.1  765.05  4468.2  763.88  4554.0  763.82
  4608.9  766.30  4625.0  763.00  4642.5  762.38  4990.3  750.08  5386.6  762.56
  5400.0  763.00  5402.3  768.54  5436.3  775.76  5535.8  791.05  5610.0  797.30
  5701.6  801.11  5736.4  803.76  5760.9  807.08  5774.8  807.53  5876.7  816.15
#Mann=7,-1,0
  3709.5    0.14       0  3889.6     0.1       0  4106.2    0.14       0
  4625.0   0.045       0  4642.5   0.035       0  5386.6    0.14       0
  5400.0   0.035       0
Bank Sta=4625,5400
XS Rating Curve= 0
Exp/Cntr=0.3,0.1

Type RM Length L Ch R = 1,151677,781,781,781
BEGIN DESCRIPTION:
Dutchman Creek 175.0
END DESCRIPTION:
XS GIS Cut Line= 5
      1509789.41       830268.32      1510067.16       830129.44
      1510388.34       829487.08      1510648.76       829096.46
      1510775.00       828925.00
#Sta/Elev= 30
  4062.1  785.09  4116.5  781.67  4140.9  779.03  4170.5  776.92  4198.6  775.29
  4215.2  773.78  4251.4  771.67  4269.8  771.35  4323.9  768.34  4335.6  768.49
  4348.5  768.02  4383.2  765.54  4402.2  765.04  4404.9  764.72  4406.6  763.19
  4428.1  762.61  4990.3  745.93  5009.7  745.93  5529.5  762.20  5555.0  763.00
  5560.3  766.42  5570.0  768.99  5583.5  771.94  5597.3  774.01  5639.0  779.41
  5672.9  782.22  5690.2  783.03  5719.3  785.16  5745.0  785.71  5773.2  787.27
#Mann=6,-1,0
  4062.1    0.06       0  4140.9    0.14       0  4406.6   0.045       0
  4428.1   0.035       0  5529.5    0.14       0  5555.0   0.035       0
Bank Sta=4406.6,5555
XS Rating Curve= 0
Exp/Cntr=0.5,0.3