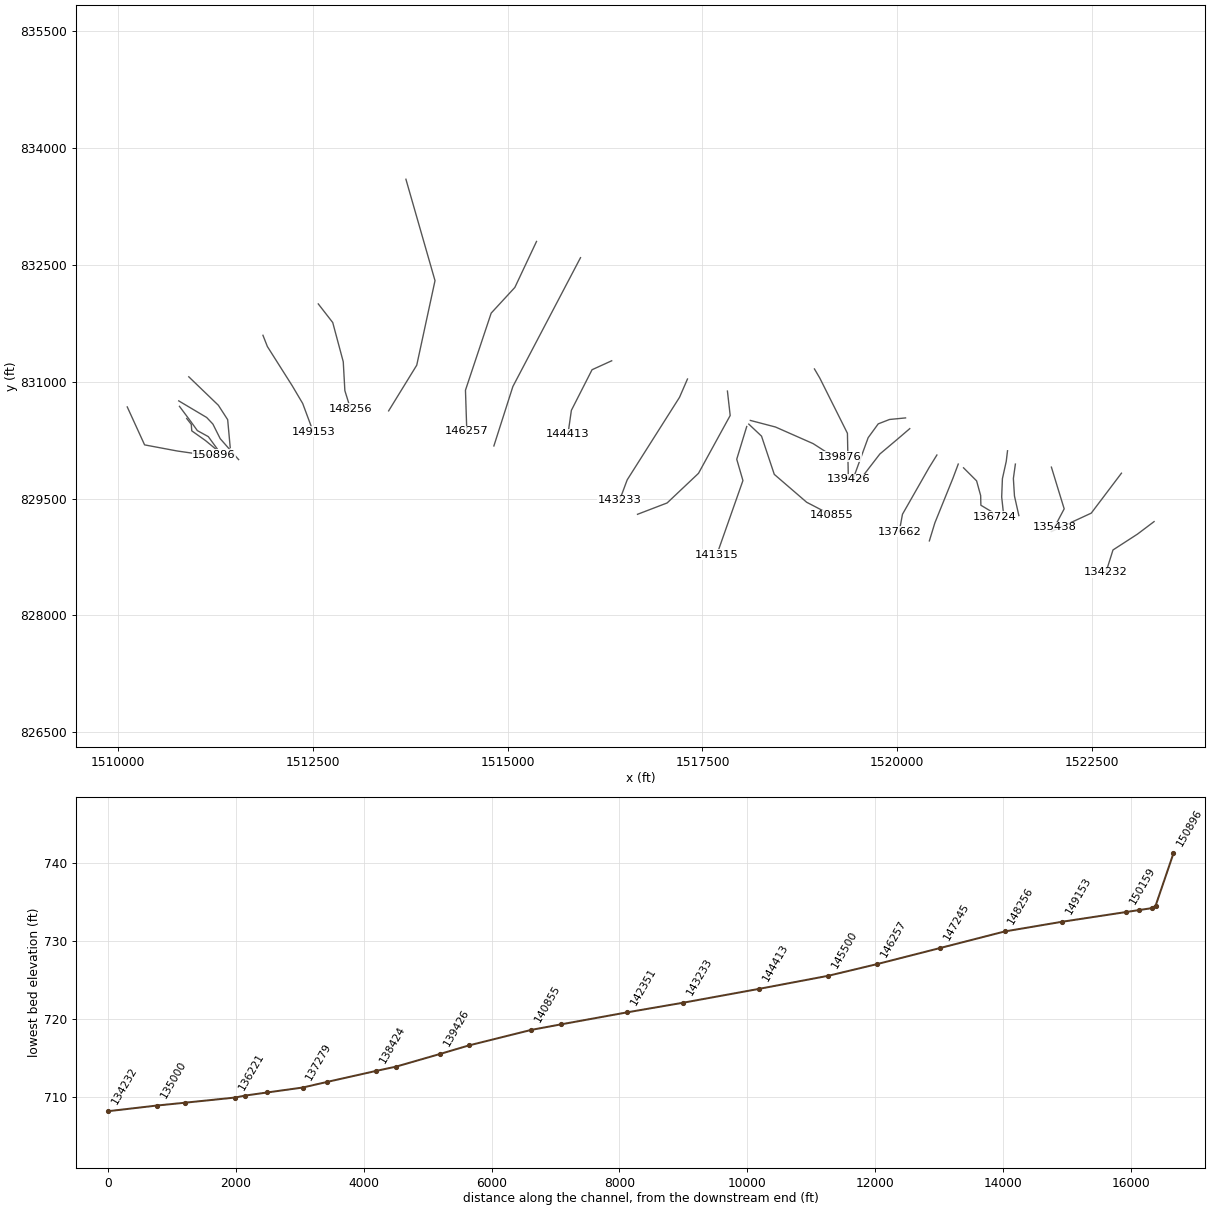
HEC-RAS study Dutchman Creek.prj: Dutchman Creek Limited Detail Study

--- Dutchman Creek.g01 (geometry) --- (continued)

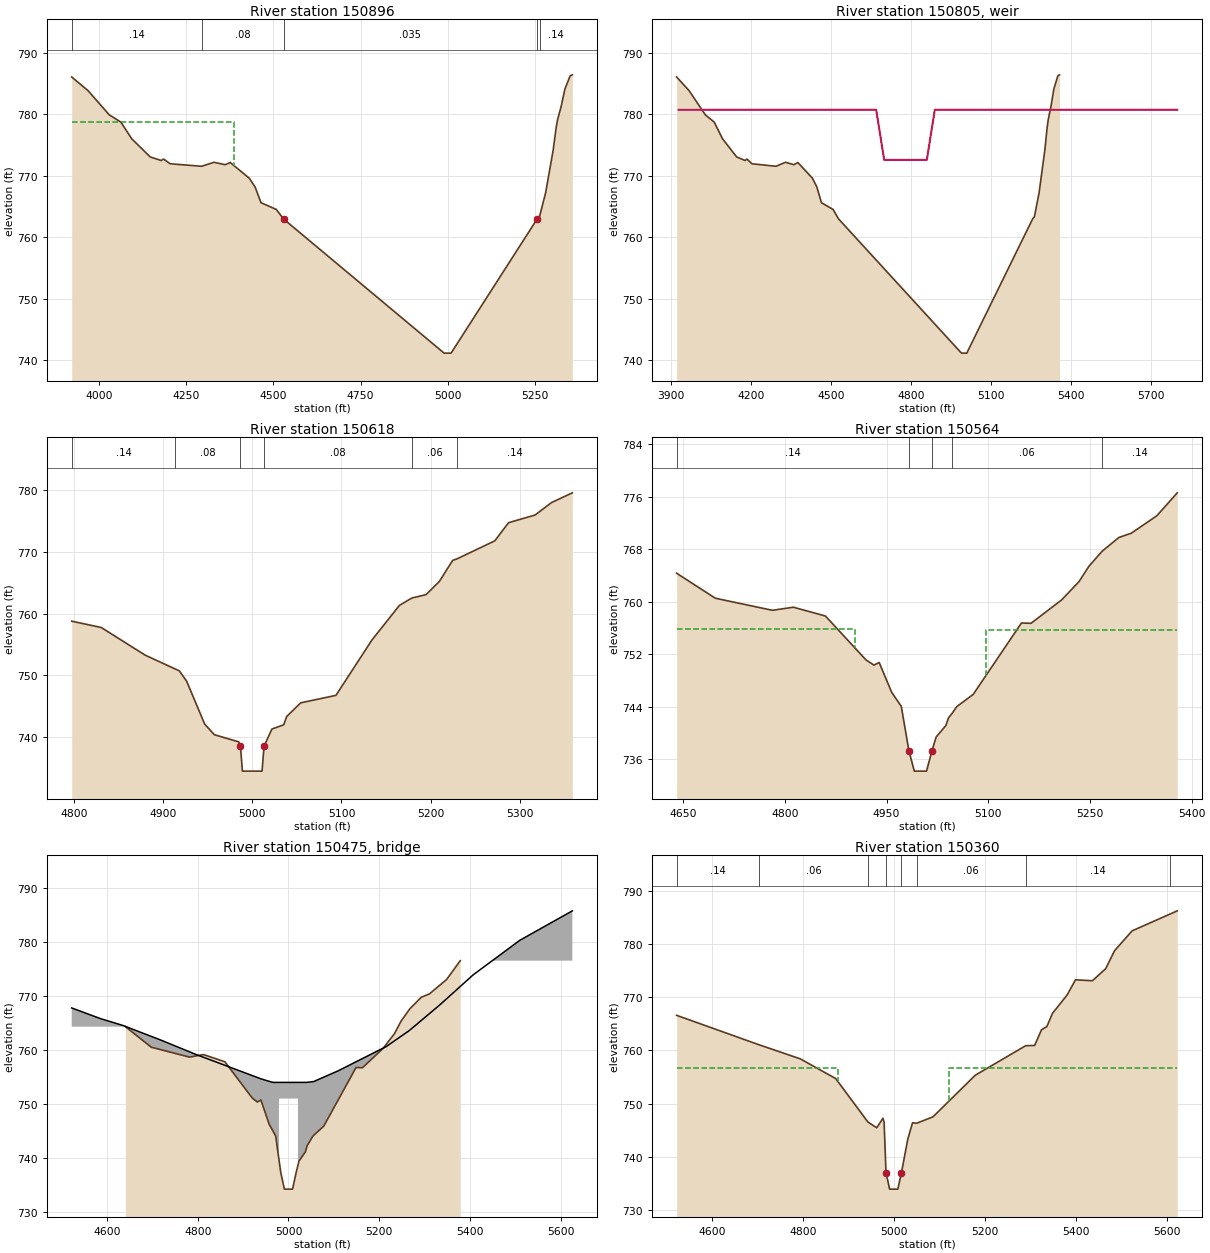
Type RM Length L Ch R = 1,150896,278,278,278
BEGIN DESCRIPTION:
Dam (DC) us
END DESCRIPTION:
XS GIS Cut Line= 5
      1510122.20       830675.55      1510344.67       830188.46
      1510762.67       830110.05      1511127.96       830057.15
      1511235.01       830064.70
#Sta/Elev= 30
  3920.9  786.09  3967.6  783.88  4028.8  779.93  4062.0  778.76  4093.1  776.05
  4146.3  773.09  4177.8  772.51  4184.9  772.74  4203.6  771.98  4293.8  771.57
  4329.3  772.22  4361.2  771.83  4376.0  772.18  4430.7  769.63  4447.3  768.21
  4464.4  765.65  4508.3  764.55  4529.0  763.00  4990.0  741.19  5010.0  741.19
  5257.0  763.00  5263.8  763.37  5281.3  767.24  5303.0  774.19  5311.6  777.85
  5315.5  779.11  5326.1  781.34  5336.8  784.15  5352.0  786.30  5358.1  786.44
#Mann=5,-1,0
  3920.9    0.14       0  4293.8    0.08       0  4529.0   0.035       0
  5257.0    0.14       0  5263.8    0.14       0
#XS Ineff=2,0
    0.00 4387.30  778.75               0
Permanent Ineff=
       F       F
Bank Sta=4529,5257
XS Rating Curve= 0
Exp/Cntr=0.5,0.3

Type RM Length L Ch R =5,150805,,,
BEGIN DESCRIPTION:
Dam (DC) tor
Structure ID: LDS_DC_14
Approximate Survey Structure
END DESCRIPTION:
#Inline Weir SE= 6
  3928.4  780.75  4670.0  780.75  4700.0  772.60  4860.0  772.60  4890.0  780.75
  5800.0  780.75
IW Dist,WD,Coef,Skew,MaxSub,Min_El,Is_Ogee,SpillHt,DesHd
178,10,3,,0.95,,0,,,1,1

Type RM Length L Ch R = 1,150618,54,54,54
BEGIN DESCRIPTION:
Dutchman Creek 174.0
END DESCRIPTION:
XS GIS Cut Line= 5
      1510884.76       830526.99      1510943.35       830452.20
      1510949.59       830368.64      1511124.19       830245.17
      1511253.93       830137.89
#Sta/Elev= 30
  4797.7  758.77  4830.8  757.75  4880.0  753.28  4913.9  751.03  4918.3  750.74
  4926.4  749.10  4946.7  742.14  4957.5  740.42  4984.9  739.26  4986.8  738.53
  4989.0  734.53  5011.0  734.53  5013.2  738.53  5022.0  741.33  5035.3  742.02
  5038.6  743.36  5054.3  745.57  5093.8  746.78  5134.2  755.74  5165.0  761.33
  5178.8  762.51  5194.7  763.06  5209.6  765.18  5224.6  768.60  5229.4  768.84
  5271.8  771.76  5287.2  774.69  5316.9  775.93  5335.3  777.94  5358.7  779.52
#Mann=6,-1,0
  4797.7    0.14       0  4913.9    0.08       0  4986.8   0.045       0
  5013.2    0.08       0  5178.8    0.06       0  5229.4    0.14       0
Bank Sta=4986.8,5013.2
XS Rating Curve= 0
Exp/Cntr=0.5,0.3

Type RM Length L Ch R = 1,150564,204,204,204
BEGIN DESCRIPTION:
Liberty Church Rd (DC) us
END DESCRIPTION:
XS GIS Cut Line= 5
      1510791.94       830683.08      1510937.15       830488.69
      1511021.46       830371.59      1511161.97       830294.31
      1511274.37       830139.76
#Sta/Elev= 30
  4640.4  764.34  4697.5  760.53  4781.7  758.69  4812.7  759.16  4859.9  757.82
  4919.8  751.13  4931.5  750.35  4939.2  750.74  4957.5  746.22  4971.8  744.06
  4983.0  737.30  4991.0  734.20  5009.0  734.20  5017.0  737.30  5023.2  739.40
  5037.5  741.14  5041.3  742.28  5046.9  743.03  5053.6  744.02  5077.8  745.88
  5149.0  756.76  5163.1  756.71  5208.1  760.26  5233.7  763.03  5248.5  765.39
  5267.9  767.68  5292.7  769.78  5311.0  770.43  5348.7  773.09  5378.8  776.58
#Mann=5,-1,0
  4640.4    0.14       0  4983.0   0.045       0  5017.0    0.14       0
  5046.9    0.06       0  5267.9    0.14       0
#XS Ineff=2,0
    0.00 4903.50  755.88 5096.50    0.00  755.63
Permanent Ineff=
       F       F
Bank Sta=4983,5017
XS Rating Curve= 0
Exp/Cntr=0.5,0.3

Type RM Length L Ch R =3,150475,,,
BEGIN DESCRIPTION:
LIberty Church Rd (DC) tor
Structure ID: LDS_DC_13
Approximate Survey Structure
END DESCRIPTION:
Bridge Culvert--1,0,-1,-1,0
Deck Dist Width WeirC Skew NumUp NumDn MinLoCord MaxHiCord MaxSubmerge Is_Ogee
75.5,27,3,,20,20,,,0.95,0,1,1,,,
  4522.0  4585.9  4634.7  4719.2  4796.7  4940.1  4965.5  4979.0  4979.0  5021.0
  5021.0  5039.1  5055.4  5109.4  5215.6  5266.1  5332.8  5407.1  5509.9  5626.0
  767.81  765.82  764.57  761.83  759.16  754.64  754.00  754.00  754.00  754.00
  754.00  754.00  754.15  756.14  760.65  763.60  768.31  773.94  780.35  785.83
  714.20  714.20  714.20  714.20  714.20  714.20  714.20  714.20  751.00  751.00
  714.20  714.20  714.20  714.20  714.20  714.20  714.20  714.20  714.20  714.20
  4522.0  4585.9  4634.7  4719.2  4796.7  4940.1  4965.5  4979.0  4979.0  5021.0
  5021.0  5039.1  5055.4  5109.4  5215.6  5266.1  5332.8  5407.1  5509.9  5626.0
  767.81  765.82  764.57  761.83  759.16  754.64  754.00  754.00  754.00  754.00
  754.00  754.00  754.15  756.14  760.65  763.60  768.31  773.94  780.35  785.83
  714.20  714.20  714.20  714.20  714.20  714.20  714.20  714.20  751.00  751.00
  714.20  714.20  714.20  714.20  714.20  714.20  714.20  714.20  714.20  714.20
Abutment Skew #Up #Dn=,2,2
  4979.0  4980.0
  751.00  739.11
  4979.0  4980.0
  751.00  743.81
Abutment Skew #Up #Dn=,2,2
  5020.0  5021.0
  738.32  751.00
  5020.0  5021.0
  738.41  751.00
BR Coef=1,1,0,1.25,0,,,0.8,0,2,0,
WSPro=,,,, 1 ,,,, 0 ,,,, 0 ,,,,-1 ,-1 ,-1 , 0 , 0 , 0 , 0 , 0
BC Design=,,0,,0,,,,,,

Type RM Length L Ch R = 1,150360,201,201,201
BEGIN DESCRIPTION:
Liberty Church Rd (DC) ds
END DESCRIPTION:
XS GIS Cut Line= 5
      1510782.55       830753.34      1511140.89       830540.21
      1511220.51       830455.90      1511314.19       830268.55
      1511550.72       829999.23
#Sta/Elev= 30
  4522.6  766.60  4703.4  761.08  4794.9  758.41  4872.4  754.72  4943.2  746.56
  4962.6  745.48  4976.3  747.26  4978.8  746.52  4983.0  737.05  4991.0  733.95
  5009.0  733.95  5017.0  737.05  5030.9  743.33  5041.3  746.41  5050.6  746.33
  5086.3  747.53  5179.3  755.35  5290.1  760.89  5309.8  760.94  5324.8  763.87
  5336.7  764.49  5349.0  766.96  5381.2  770.42  5399.6  773.27  5436.9  773.10
  5466.1  775.37  5485.4  778.72  5524.1  782.47  5608.5  785.66  5623.4  786.23
#Mann=8,-1,0
  4522.6    0.14       0  4703.4    0.06       0  4943.2    0.14       0
  4983.0   0.045       0  5017.0    0.14       0  5050.6    0.06       0
  5290.1    0.14       0  5608.5    0.14       0
#XS Ineff=2,0
    0.00 4878.00  756.65 5122.40    0.00  756.65
Permanent Ineff=
       F       F
Bank Sta=4983,5017
XS Rating Curve= 0
Exp/Cntr=0.5,0.3

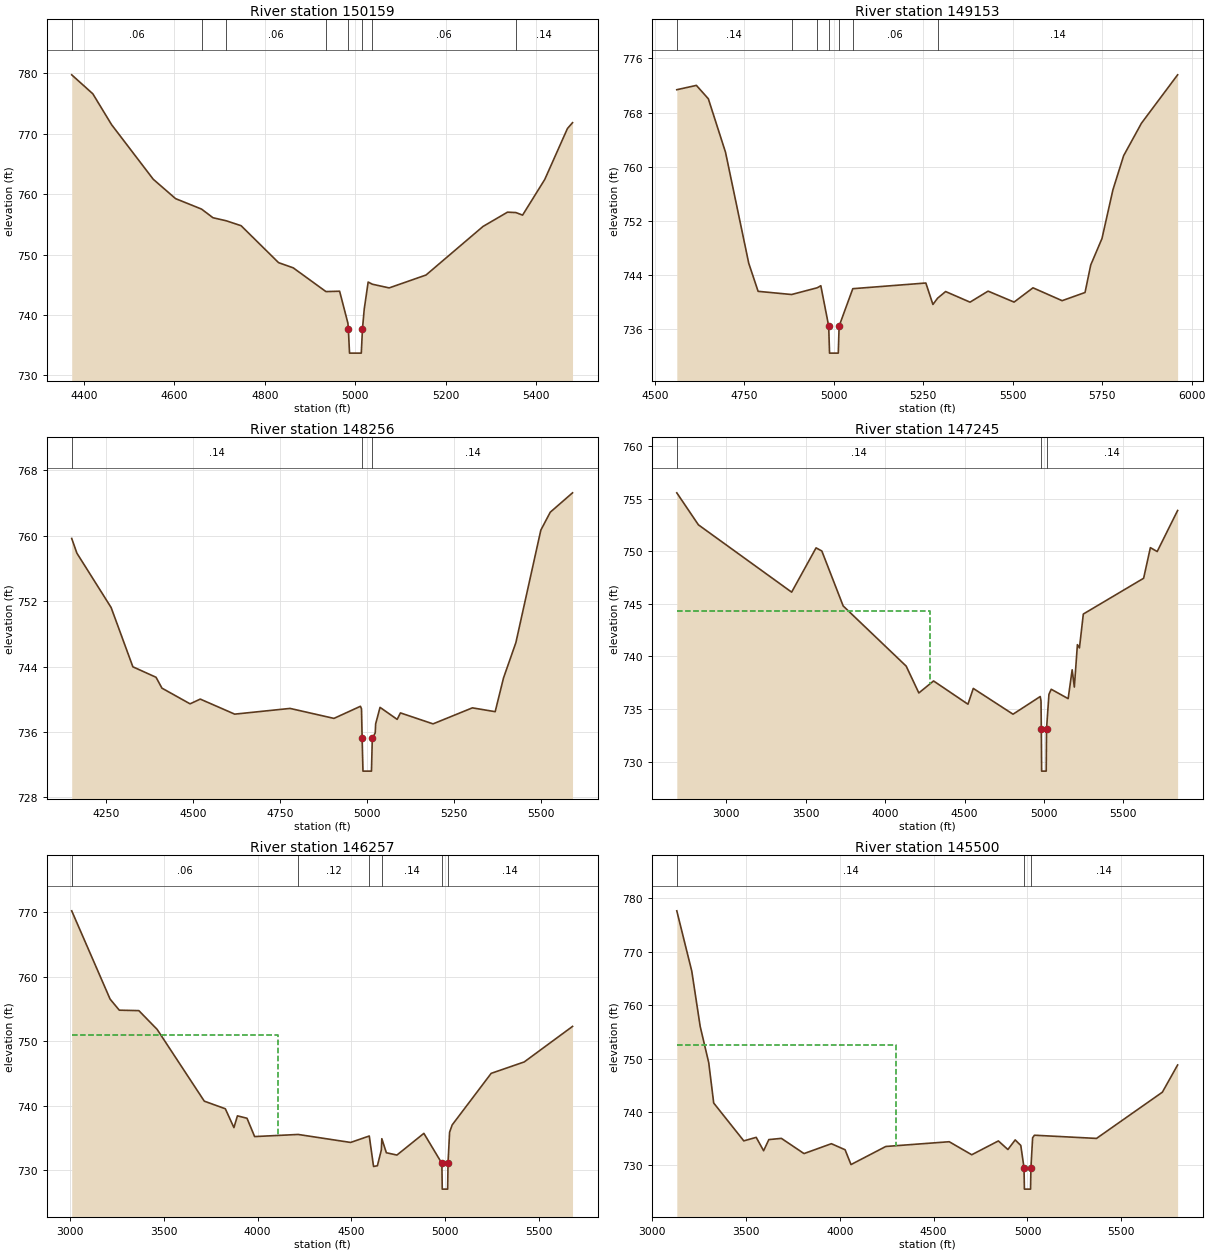
Type RM Length L Ch R = 1,150159,1006,1006,1006
BEGIN DESCRIPTION:
Dutchman Creek 173.0
END DESCRIPTION:
XS GIS Cut Line= 4
      1510911.37       831062.46      1511290.77       830697.11
      1511410.20       830512.10      1511442.99       830153.32
#Sta/Elev= 30
  4372.8  779.74  4419.5  776.60  4461.1  771.48  4553.0  762.47  4602.4  759.26
  4659.8  757.53  4685.1  756.10  4714.6  755.59  4747.3  754.78  4830.1  748.67
  4862.5  747.81  4934.9  743.88  4965.1  743.94  4983.4  738.66  4984.4  737.70
  4987.0  733.70  5013.0  733.70  5015.6  737.70  5019.5  740.98  5028.2  745.46
  5037.5  745.10  5074.6  744.49  5156.1  746.62  5282.0  754.65  5336.2  757.02
  5354.9  756.95  5369.6  756.53  5418.6  762.43  5468.8  770.86  5480.0  771.82
#Mann=8,-1,0
  4372.8    0.06       0  4659.8    0.14       0  4714.6    0.06       0
  4934.9    0.14       0  4984.4   0.045       0  5015.6    0.14       0
  5037.5    0.06       0  5354.9    0.14       0
Bank Sta=4984.4,5015.6
XS Rating Curve= 0
Exp/Cntr=0.3,0.1

Type RM Length L Ch R = 1,149153,897,897,897
BEGIN DESCRIPTION:
Dutchman Creek 172.0
END DESCRIPTION:
XS GIS Cut Line= 5
      1511862.85       831595.35      1511919.52       831451.11
      1512238.82       830946.40      1512372.73       830719.79
      1512506.63       830359.28
#Sta/Elev= 30
  4560.8  771.37  4615.6  772.01  4649.0  770.03  4697.0  762.13  4761.9  745.74
  4788.1  741.58  4881.7  741.11  4953.6  742.11  4963.4  742.41  4985.4  736.45
  4987.8  732.45  5012.2  732.45  5014.6  736.45  5052.8  741.97  5257.0  742.81
  5276.8  739.64  5289.9  740.57  5312.3  741.55  5380.5  739.98  5431.0  741.61
  5503.6  739.99  5556.5  742.10  5638.0  740.20  5702.0  741.41  5717.9  745.47
  5749.4  749.39  5780.0  756.59  5809.9  761.62  5859.7  766.42  5960.8  773.57
#Mann=7,-1,0
  4560.8    0.14       0  4881.7    0.06       0  4953.6    0.14       0
  4985.4   0.045       0  5014.6    0.14       0  5052.8    0.06       0
  5289.9    0.14       0
Bank Sta=4985.4,5014.6
XS Rating Curve= 0
Exp/Cntr=0.3,0.1

Type RM Length L Ch R = 1,148256,1011,1011,1011
BEGIN DESCRIPTION:
Dutchman Creek 171.0
END DESCRIPTION:
XS GIS Cut Line= 5
      1512572.53       831998.08      1512757.96       831759.09
      1512892.89       831255.40      1512913.49       830884.59
      1512985.59       830652.87
#Sta/Elev= 30
  4151.5  759.67  4166.4  757.87  4264.7  751.22  4327.1  743.97  4393.6  742.69
  4410.6  741.36  4491.4  739.44  4520.6  740.02  4619.5  738.18  4778.4  738.88
  4904.5  737.66  4980.5  739.14  4983.6  738.83  4985.4  735.21  4987.8  731.21
  5012.2  731.21  5014.6  735.21  5023.0  735.89  5024.2  736.98  5036.8  739.01
  5086.0  737.54  5095.4  738.33  5189.0  736.99  5302.0  738.95  5367.4  738.48
  5391.3  742.60  5426.8  746.92  5498.5  760.69  5525.6  762.88  5589.5  765.25
#Mann=3,-1,0
  4151.5    0.14       0  4985.4   0.045       0  5014.6    0.14       0
Bank Sta=4985.4,5014.6
XS Rating Curve= 0
Exp/Cntr=0.3,0.1

Type RM Length L Ch R = 1,147245,988,988,988
BEGIN DESCRIPTION:
Dutchman Creek 170.0
END DESCRIPTION:
XS GIS Cut Line= 4
      1513696.60       833598.71      1514069.86       832296.65
      1513835.48       831211.59      1513474.99       830624.99
#Sta/Elev= 30
  2688.6  755.54  2824.6  752.50  3411.7  746.10  3565.5  750.31  3601.8  750.01
  3736.1  744.79  4132.8  739.07  4212.5  736.52  4305.1  737.66  4521.7  735.45
  4555.3  736.95  4805.4  734.50  4976.8  736.18  4981.7  735.75  4983.6  733.09
  4985.6  729.09  5014.4  729.09  5016.4  733.09  5031.6  736.39  5046.0  736.87
  5152.6  735.98  5177.8  738.72  5191.5  737.08  5210.8  741.11  5223.7  740.80
  5248.0  744.02  5627.7  747.42  5670.2  750.33  5713.1  749.96  5841.7  753.86
#Mann=3,-1,0
  2688.6    0.14       0  4983.6   0.045       0  5016.4    0.14       0
#XS Ineff=2,0
    0.00 4281.10  744.30               0
Permanent Ineff=
       F       F
Bank Sta=4983.6,5016.4
XS Rating Curve= 0
Exp/Cntr=0.3,0.1

Type RM Length L Ch R = 1,146257,757,757,757
BEGIN DESCRIPTION:
Dutchman Creek 169.0
END DESCRIPTION:
XS GIS Cut Line= 5
      1515371.92       832800.08      1515094.16       832209.85
      1514790.34       831879.99      1514460.48       830890.40
      1514477.84       830360.88
#Sta/Elev= 30
  3007.4  770.25  3212.4  756.54  3261.4  754.82  3365.9  754.75  3463.7  751.83
  3715.3  740.69  3827.6  739.51  3873.4  736.58  3892.1  738.41  3943.2  738.04
  3984.0  735.19  4216.2  735.52  4496.3  734.28  4596.0  735.28  4618.8  730.55
  4639.3  730.66  4660.4  733.11  4663.0  734.86  4687.2  732.68  4743.6  732.32
  4887.5  735.69  4983.6  731.03  4985.6  727.03  5014.4  727.03  5016.4  731.03
  5024.8  735.87  5038.6  737.00  5246.8  745.01  5423.1  746.78  5681.1  752.30
#Mann=6,-1,0
  3007.4    0.06       0  4216.2    0.12       0  4596.0    0.05       0
  4663.0    0.14       0  4983.6   0.045       0  5016.4    0.14       0
#XS Ineff=2,0
    0.00 4108.70  751.00               0
Permanent Ineff=
       F       F
Bank Sta=4983.6,5016.4
XS Rating Curve= 0
Exp/Cntr=0.3,0.1

Type RM Length L Ch R = 1,145500,1087,1087,1087
BEGIN DESCRIPTION:
Dutchman Creek 168.0
END DESCRIPTION:
XS GIS Cut Line= 3
      1515936.17       832591.79      1515068.36       830937.04
      1514824.99       830174.96
#Sta/Elev= 30
  3131.5  777.69  3211.3  766.39  3256.2  756.02  3301.7  749.24  3328.2  741.68
  3488.5  734.59  3554.6  735.25  3594.1  732.74  3621.9  734.83  3688.9  735.06
  3809.4  732.21  3955.1  734.06  4028.2  732.93  4059.7  730.15  4245.1  733.54
  4583.0  734.43  4703.1  731.99  4845.0  734.58  4895.6  732.97  4934.6  734.77
  4964.4  733.73  4981.6  729.55  4983.6  725.55  5016.4  725.55  5018.4  729.55
  5027.5  735.18  5037.1  735.65  5367.8  735.05  5718.7  743.71  5800.0  748.81
#Mann=3,-1,0
  3131.5    0.14       0  4981.6   0.045       0  5018.4    0.14       0
#XS Ineff=2,0
    0.00 4299.20  752.62               0
Permanent Ineff=
       F       F
Bank Sta=4981.6,5018.4
XS Rating Curve= 0
Exp/Cntr=0.3,0.1

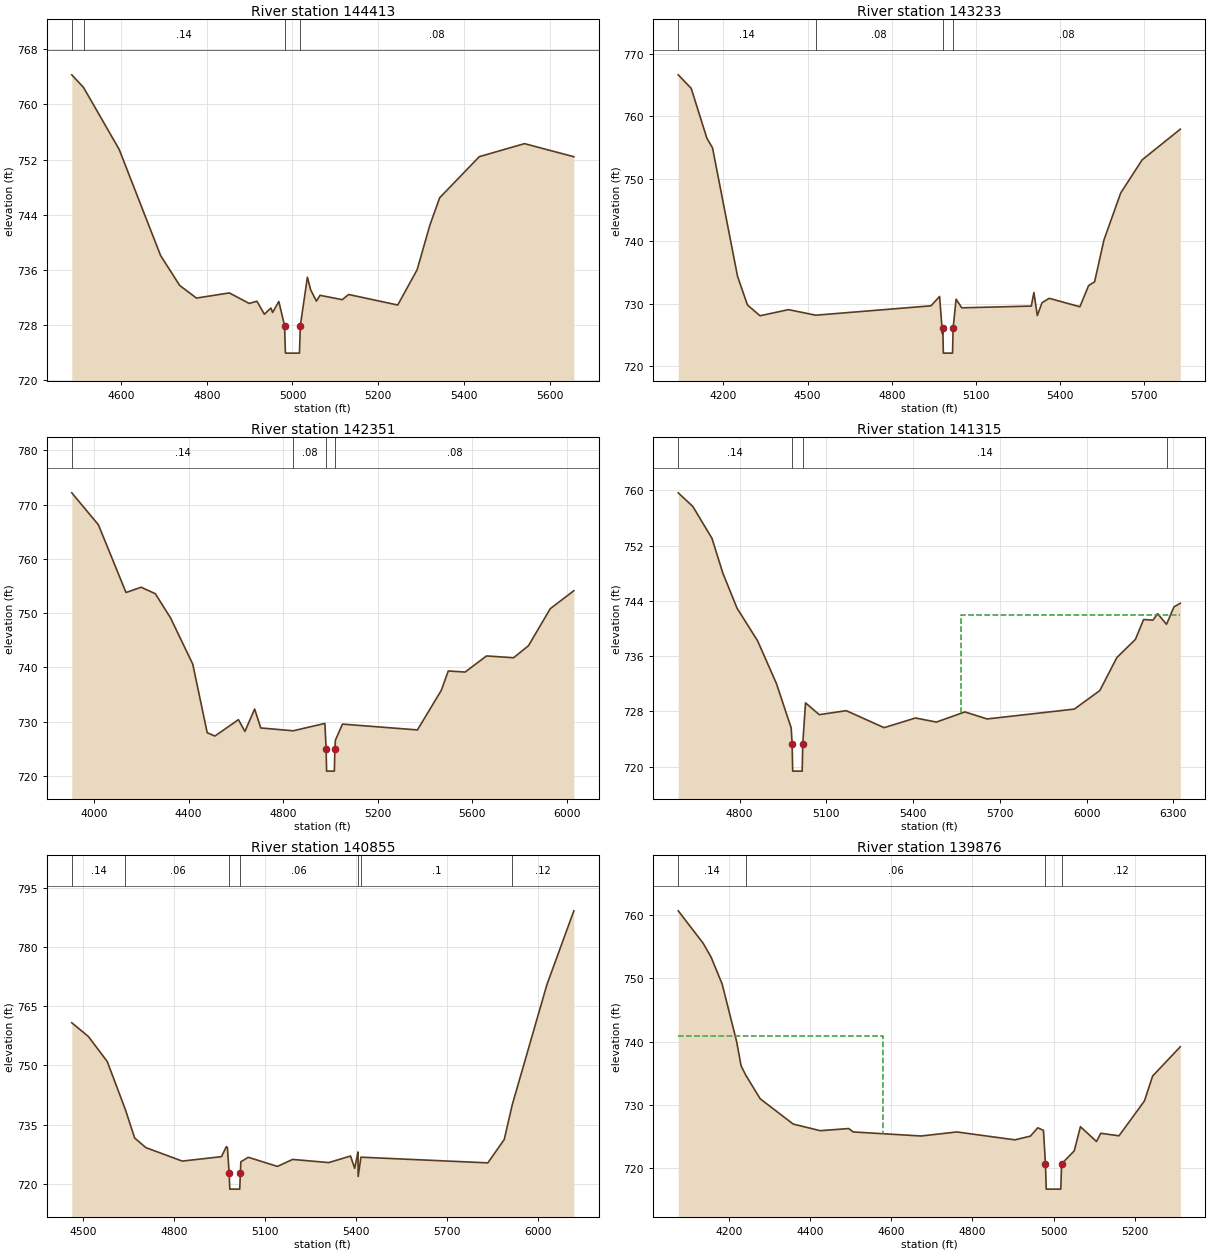
Type RM Length L Ch R = 1,144413,1180,1180,1180
BEGIN DESCRIPTION:
Dutchman Creek 167.0
END DESCRIPTION:
XS GIS Cut Line= 4
      1516336.03       831268.09      1516084.15       831153.20
      1515819.02       830631.76      1515775.00       830325.02
#Sta/Elev= 30
  4485.0  764.31  4512.5  762.47  4595.6  753.48  4692.4  738.04  4736.8  733.71
  4776.0  731.87  4852.7  732.62  4899.1  731.09  4917.1  731.41  4934.5  729.52
  4949.8  730.42  4953.7  729.78  4968.2  731.37  4981.6  727.87  4983.6  723.87
  5016.4  723.87  5018.4  727.87  5034.9  734.90  5042.5  733.07  5055.9  731.43
  5064.4  732.27  5116.3  731.64  5131.1  732.39  5245.7  730.86  5290.9  735.98
  5320.8  742.48  5343.6  746.45  5436.1  752.42  5541.5  754.31  5656.7  752.41
#Mann=4,-1,0
  4485.0    0.06       0  4512.5    0.14       0  4981.6   0.045       0
  5018.4    0.08       0
Bank Sta=4981.6,5018.4
XS Rating Curve= 0
Exp/Cntr=0.3,0.1

Type RM Length L Ch R = 1,143233,882,882,882
BEGIN DESCRIPTION:
Dutchman Creek 166.0
END DESCRIPTION:
XS GIS Cut Line= 4
      1517308.21       831033.93      1517206.56       830799.68
      1516534.88       829739.15      1516437.68       829478.47
#Sta/Elev= 30
  4039.0  766.64  4085.3  764.47  4141.0  756.51  4161.2  754.95  4250.3  734.40
  4285.7  729.81  4330.4  728.09  4431.9  729.07  4528.9  728.18  4939.6  729.68
  4970.2  731.18  4980.5  725.23  4981.6  726.11  4983.6  722.11  5016.4  722.11
  5018.4  726.11  5029.1  730.74  5049.2  729.36  5297.0  729.64  5306.2  731.81
  5318.5  728.12  5335.1  730.17  5360.9  730.88  5470.1  729.53  5501.2  732.92
  5522.5  733.52  5555.9  740.23  5615.6  747.74  5692.0  753.04  5827.9  757.94
#Mann=4,-1,0
  4039.0    0.14       0  4528.9    0.08       0  4981.6   0.045       0
  5018.4    0.08       0
Bank Sta=4981.6,5018.4
XS Rating Curve= 0
Exp/Cntr=0.3,0.1

Type RM Length L Ch R = 1,142351,1036,1036,1036
BEGIN DESCRIPTION:
Dutchman Creek 165.0
END DESCRIPTION:
XS GIS Cut Line= 6
      1517820.78       830879.27      1517856.14       830565.48
      1517732.41       830340.12      1517449.60       829823.11
      1517047.48       829443.08      1516667.45       829297.26
#Sta/Elev= 30
  3906.3  772.19  4018.9  766.30  4135.6  753.81  4199.6  754.78  4259.5  753.59
  4324.4  749.08  4417.8  740.60  4478.9  727.95  4511.5  727.34  4610.8  730.36
  4638.3  728.19  4679.4  732.32  4705.3  728.83  4842.3  728.31  4976.4  729.67
  4981.6  724.87  4983.6  720.87  5016.4  720.87  5018.4  724.87  5020.9  726.59
  5050.7  729.54  5367.6  728.47  5468.4  735.76  5498.0  739.34  5569.2  739.14
  5659.7  742.11  5774.0  741.78  5837.1  744.00  5929.0  750.82  6028.8  754.14
#Mann=4,-1,0
  3906.3    0.14       0  4842.3    0.08       0  4981.6   0.045       0
  5018.4    0.08       0
Bank Sta=4981.6,5018.4
XS Rating Curve= 0
Exp/Cntr=0.3,0.1

Type RM Length L Ch R = 1,141315,460,460,460
BEGIN DESCRIPTION:
Dutchman Creek 164.0
END DESCRIPTION:
XS GIS Cut Line= 4
      1518068.26       830424.12      1517940.09       830004.28
      1518019.63       829730.31      1517683.80       828775.82
#Sta/Elev= 30
  4587.8  759.66  4638.4  757.68  4704.5  753.06  4741.9  748.04  4791.0  742.96
  4862.4  738.20  4927.4  732.02  4978.4  725.58  4981.6  723.33  4983.6  719.33
  5016.4  719.33  5018.4  723.33  5028.0  729.22  5075.5  727.51  5168.9  728.09
  5299.6  725.63  5408.2  727.03  5480.6  726.44  5579.0  727.91  5655.9  726.89
  5957.6  728.32  6045.6  731.01  6104.5  735.79  6168.6  738.42  6197.0  741.30
  6229.4  741.21  6245.4  742.15  6276.3  740.61  6302.0  743.13  6323.9  743.66
#Mann=4,-1,0
  4587.8    0.14       0  4981.6   0.045       0  5018.4    0.14       0
  6276.3    0.08       0
#XS Ineff=2,0
    0.00 4434.40  741.99 5565.60    0.00  741.99
Permanent Ineff=
       F       F
Bank Sta=4981.6,5018.4
XS Rating Curve= 0
Exp/Cntr=0.3,0.1

Type RM Length L Ch R = 1,140855,979,979,979
BEGIN DESCRIPTION:
Dutchman Creek 163.0
END DESCRIPTION:
XS GIS Cut Line= 5
      1518094.77       830455.00      1518258.26       830300.35
      1518421.76       829809.85      1518837.13       829451.92
      1519159.75       829283.98
#Sta/Elev= 30
  4463.0  760.81  4517.8  757.33  4579.9  750.98  4639.9  738.74  4670.3  731.58
  4707.2  729.15  4826.9  725.74  4956.2  726.86  4972.4  729.43  4975.8  729.14
  4981.6  722.63  4983.6  718.63  5016.4  718.63  5018.4  722.63  5020.1  725.57
  5044.7  726.70  5140.5  724.39  5190.7  726.16  5309.6  725.36  5381.4  727.02
  5395.0  723.91  5406.0  728.04  5406.1  728.01  5406.5  721.83  5415.6  726.73
  5833.8  725.29  5887.8  731.22  5914.3  740.05  6028.3  770.46  6117.1  789.19
#Mann=7,-1,0
  4463.0    0.14       0  4639.9    0.06       0  4981.6   0.045       0
  5018.4    0.06       0  5406.0    0.05       0  5415.6     0.1       0
  5914.3    0.12       0
Bank Sta=4981.6,5018.4
XS Rating Curve= 0
Exp/Cntr=0.3,0.1

Type RM Length L Ch R = 1,139876,450,450,450
BEGIN DESCRIPTION:
Dutchman Creek 162.0
END DESCRIPTION:
XS GIS Cut Line= 5
      1518114.86       830502.43      1518437.21       830417.81
      1518920.78       830204.24      1519090.02       830095.44
      1519255.21       830035.00
#Sta/Elev= 30
  4073.9  760.69  4135.3  755.57  4155.1  753.34  4182.3  749.10  4218.1  739.98
  4229.0  736.16  4240.5  734.69  4276.3  730.93  4357.6  726.94  4424.3  725.89
  4494.6  726.23  4505.7  725.69  4673.2  725.05  4761.4  725.69  4904.8  724.44
  4943.0  725.03  4961.2  726.35  4975.2  725.94  4980.1  720.64  4982.1  716.64
  5017.9  716.64  5019.9  720.64  5051.2  722.70  5066.4  726.52  5106.1  724.18
  5116.6  725.48  5161.6  725.08  5224.3  730.59  5244.6  734.54  5312.9  739.18
#Mann=4,-1,0
  4073.9    0.14       0  4240.5    0.06       0  4980.1   0.045       0
  5019.9    0.12       0
#XS Ineff=2,0
    0.00 4578.40  740.90               0
Permanent Ineff=
       F       F
Bank Sta=4980.1,5019.9
XS Rating Curve= 0
Exp/Cntr=0.3,0.1

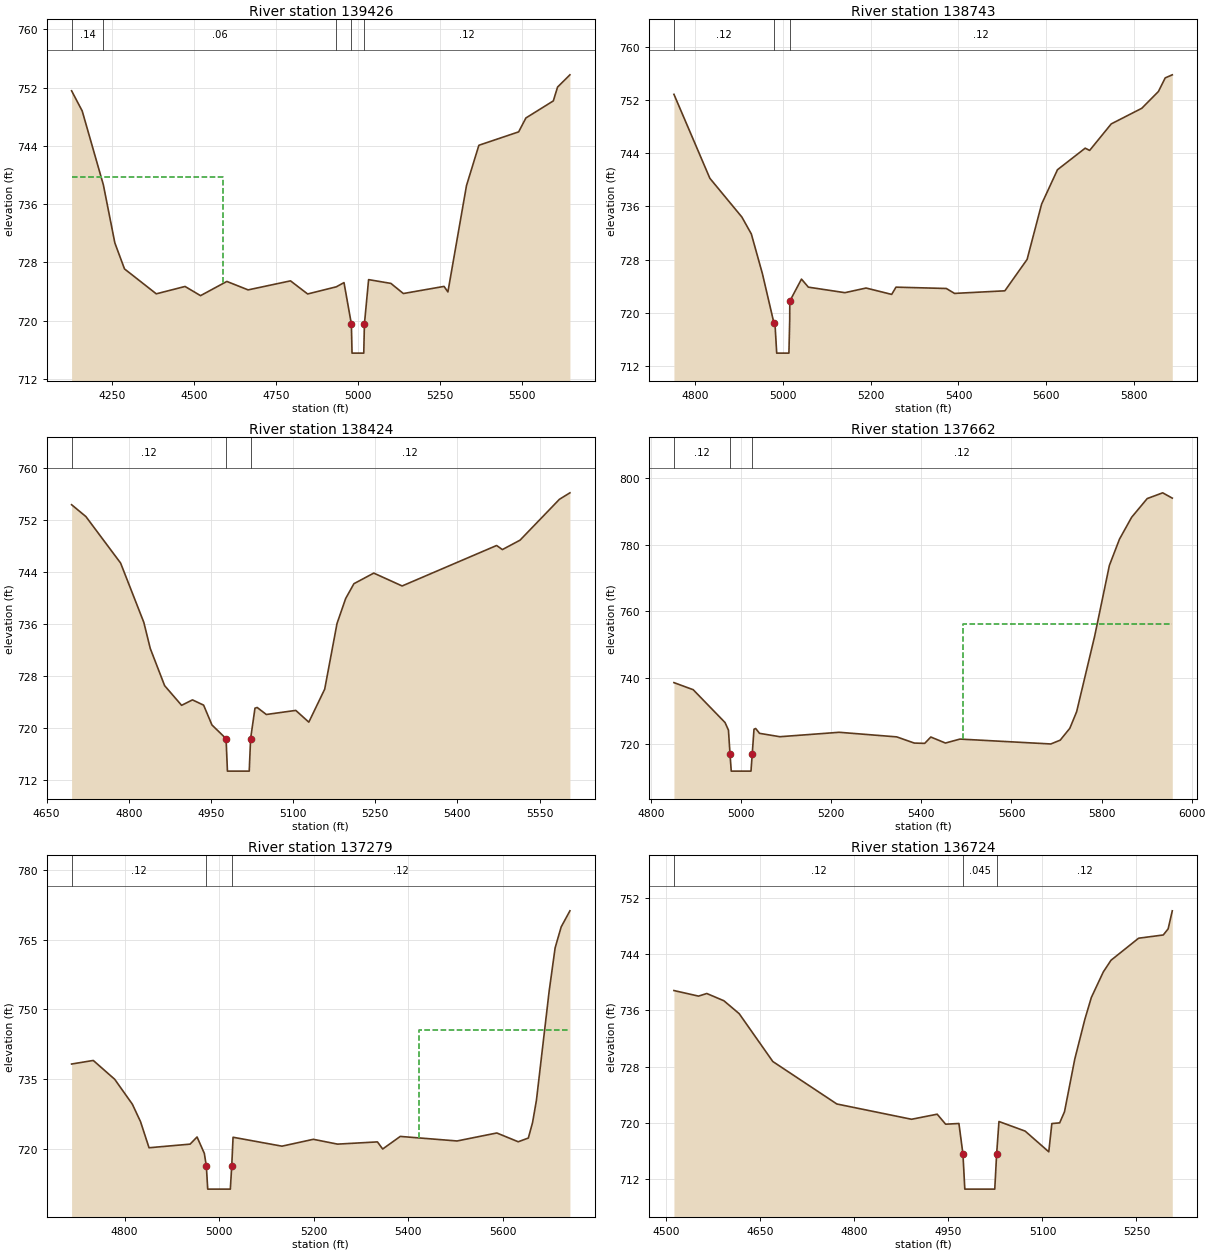
Type RM Length L Ch R = 1,139426,683,683,683
BEGIN DESCRIPTION:
Dutchman Creek 161.0
END DESCRIPTION:
XS GIS Cut Line= 4
      1518936.91       831163.29      1519005.40       831046.45
      1519360.01       830337.22      1519372.10       829744.82
#Sta/Elev= 30
  4126.2  751.56  4158.6  748.79  4223.2  738.65  4258.3  730.67  4287.7  727.11
  4384.7  723.69  4472.5  724.70  4519.8  723.44  4600.0  725.39  4665.0  724.23
  4794.3  725.47  4846.6  723.67  4934.0  724.65  4957.6  725.23  4980.1  719.55
  4982.1  715.55  5017.9  715.55  5019.9  719.55  5032.7  725.64  5100.7  725.12
  5138.8  723.73  5262.9  724.71  5274.7  723.95  5331.4  738.54  5369.2  744.08
  5490.6  745.92  5512.8  747.83  5596.4  750.17  5609.4  752.07  5647.1  753.75
#Mann=5,-1,0
  4126.2    0.14       0  4223.2    0.06       0  4934.0    0.12       0
  4980.1   0.045       0  5019.9    0.12       0
#XS Ineff=2,0
    0.00 4588.90  739.78               0
Permanent Ineff=
       F       F
Bank Sta=4980.1,5019.9
XS Rating Curve= 0
Exp/Cntr=0.3,0.1

Type RM Length L Ch R = 1,138743,319,319,319
BEGIN DESCRIPTION:
Dutchman Creek 160.0
END DESCRIPTION:
XS GIS Cut Line= 5
      1520105.54       830534.68      1519899.99       830514.53
      1519754.92       830458.11      1519625.97       830280.80
      1519436.57       829760.96
#Sta/Elev= 30
  4752.1  752.86  4833.9  740.23  4906.8  734.40  4928.3  731.86  4953.6  725.87
  4979.9  718.43  4982.4  718.08  4986.1  713.94  5013.9  713.94  5015.7  718.94
  5015.9  721.76  5042.5  725.07  5058.2  723.86  5141.4  723.03  5189.6  723.73
  5247.9  722.77  5257.7  723.86  5372.3  723.66  5391.0  722.92  5505.6  723.31
  5556.2  728.03  5589.3  736.36  5625.4  741.52  5688.5  744.76  5698.6  744.42
  5747.8  748.41  5817.4  750.76  5855.2  753.28  5870.7  755.33  5886.8  755.79
#Mann=3,-1,0
  4752.1    0.12       0  4979.9   0.045       0  5015.9    0.12       0
Bank Sta=4979.9,5015.9
XS Rating Curve= 0
Exp/Cntr=0.3,0.1

Type RM Length L Ch R = 1,138424,762,762,762
BEGIN DESCRIPTION:
Dutchman Creek 159.0
END DESCRIPTION:
XS GIS Cut Line= 4
      1520159.48       830396.84      1520001.54       830261.46
      1519775.88       830071.26      1519527.66       829748.90
#Sta/Elev= 30
  4695.5  754.40  4721.6  752.58  4785.0  745.42  4827.4  736.29  4839.2  732.26
  4865.4  726.54  4896.4  723.51  4916.2  724.35  4936.6  723.54  4951.8  720.49
  4977.6  718.38  4980.1  713.38  5019.9  713.38  5022.4  718.38  5030.4  723.07
  5034.4  723.18  5051.1  722.10  5104.9  722.73  5128.7  720.92  5157.7  726.00
  5180.2  736.11  5196.0  739.96  5211.1  742.24  5247.3  743.87  5299.1  741.89
  5471.6  748.12  5482.2  747.49  5514.4  748.94  5586.3  755.23  5605.5  756.23
#Mann=3,-1,0
  4695.5    0.12       0  4977.6   0.045       0  5022.4    0.12       0
Bank Sta=4977.6,5022.4
XS Rating Curve= 0
Exp/Cntr=0.3,0.1

Type RM Length L Ch R = 1,137662,383,383,383
BEGIN DESCRIPTION:
Dutchman Creek 158.0
END DESCRIPTION:
XS GIS Cut Line= 4
      1520507.65       830058.33      1520407.73       829897.18
      1520066.02       829297.56      1520025.00       829074.97
#Sta/Elev= 30
  4850.9  738.57  4893.6  736.45  4964.2  726.60  4971.9  724.30  4975.4  716.98
  4978.1  711.98  5021.9  711.98  5024.6  716.98  5028.6  724.57  5032.3  724.79
  5040.9  723.33  5086.1  722.32  5217.8  723.65  5345.3  722.27  5384.4  720.41
  5407.5  720.32  5421.0  722.23  5453.5  720.42  5485.8  721.61  5687.4  720.14
  5708.2  721.28  5729.6  724.85  5744.7  729.83  5784.7  752.53  5817.4  773.79
  5839.9  781.71  5866.7  788.24  5901.3  793.87  5935.7  795.60  5957.0  794.01
#Mann=3,-1,0
  4850.9    0.12       0  4975.4   0.045       0  5024.6    0.12       0
#XS Ineff=2,0
       0                 5491.40    0.00  756.27
Permanent Ineff=
       F       F
Bank Sta=4975.4,5024.6
XS Rating Curve= 0
Exp/Cntr=0.3,0.1

Type RM Length L Ch R = 1,137279,555,555,555
BEGIN DESCRIPTION:
Dutchman Creek 157.0
END DESCRIPTION:
XS GIS Cut Line= 4
      1520781.68       829942.29      1520713.99       829761.78
      1520481.88       829187.95      1520410.95       828955.83
#Sta/Elev= 30
  4688.0  738.20  4733.9  738.97  4779.3  734.91  4816.6  729.55  4833.9  725.79
  4851.9  720.17  4938.8  720.95  4953.5  722.49  4968.9  718.96  4973.1  716.26
  4976.1  711.26  5023.9  711.26  5026.9  716.26  5029.7  722.43  5133.2  720.51
  5199.6  721.99  5250.8  720.95  5335.2  721.43  5346.3  719.90  5383.5  722.61
  5503.6  721.63  5587.8  723.35  5633.1  721.46  5654.5  722.26  5663.4  725.57
  5671.6  730.37  5698.5  753.86  5711.2  763.22  5724.0  767.73  5742.5  771.19
#Mann=3,-1,0
  4688.0    0.12       0  4973.1   0.045       0  5026.9    0.12       0
#XS Ineff=2,0
       0                 5423.40    0.00  745.52
Permanent Ineff=
       F       F
Bank Sta=4973.1,5026.9
XS Rating Curve= 0
Exp/Cntr=0.3,0.1

Type RM Length L Ch R = 1,136724,347,347,347
BEGIN DESCRIPTION:
Dutchman Creek 156.0
END DESCRIPTION:
XS GIS Cut Line= 6
      1520849.41       829893.93      1521017.02       829726.32
      1521069.05       829537.13      1521071.83       829413.61
      1521216.90       829326.57      1521242.59       829262.19
#Sta/Elev= 30
  4511.9  738.83  4551.1  738.04  4564.3  738.41  4591.6  737.38  4616.0  735.55
  4669.7  728.75  4771.9  722.72  4891.1  720.55  4932.0  721.27  4945.5  719.85
  4966.7  719.95  4973.1  715.63  4976.1  710.63  5023.9  710.63  5026.9  715.63
  5030.6  720.23  5072.4  718.87  5110.1  715.93  5115.0  719.94  5127.5  720.04
  5135.2  721.62  5151.6  729.10  5167.7  734.75  5178.0  737.84  5197.1  741.47
  5209.4  743.13  5253.4  746.26  5292.8  746.72  5300.6  747.59  5307.2  750.15
#Mann=3,-1,0
  4511.9    0.12       0  4973.1   0.045       0  5026.9    0.12       0
Bank Sta=4973.1,5026.9
XS Rating Curve= 0
Exp/Cntr=0.5,0.3

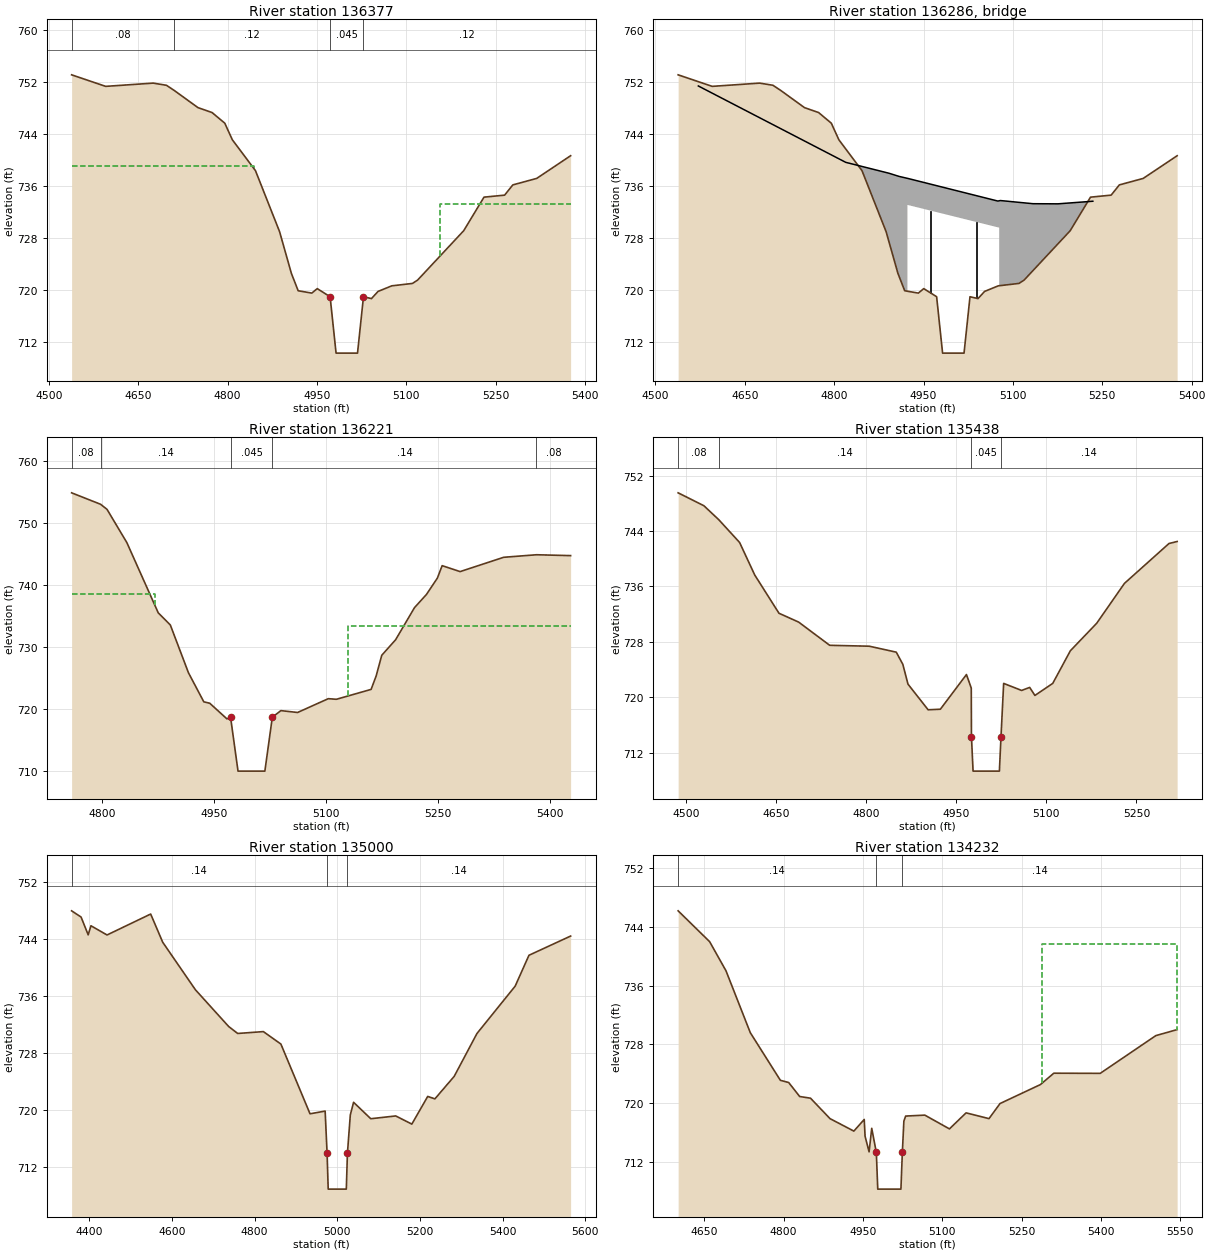
Type RM Length L Ch R = 1,136377,156,156,156
BEGIN DESCRIPTION:
US 601 (DC) us
END DESCRIPTION:
XS GIS Cut Line= 5
      1521413.66       830112.96      1521397.26       829977.02
      1521348.04       829754.37      1521338.67       829520.01
      1521364.45       829283.31
#Sta/Elev= 30
  4538.1  753.16  4595.3  751.38  4675.0  751.88  4697.2  751.55  4710.5  750.74
  4750.2  748.10  4773.9  747.34  4795.2  745.70  4807.9  743.14  4846.7  738.38
  4887.2  728.96  4907.0  722.53  4918.4  719.85  4941.3  719.49  4950.4  720.18
  4972.0  718.93  4982.0  710.23  5018.0  710.23  5028.0  718.93  5041.4  718.64
  5052.5  719.75  5075.5  720.61  5110.2  720.98  5118.9  721.50  5196.2  729.11
  5230.3  734.29  5264.9  734.60  5278.7  736.18  5318.7  737.18  5375.7  740.68
#Mann=4,-1,0
  4538.1    0.08       0  4710.5    0.12       0  4972.0   0.045       0
  5028.0    0.12       0
#XS Ineff=2,0
    0.00 4844.00  739.05 5156.00    0.00  733.30
Permanent Ineff=
       F       F
Bank Sta=4972,5028
XS Rating Curve= 0
Exp/Cntr=0.5,0.3

Type RM Length L Ch R =3,136286,,,
BEGIN DESCRIPTION:
US 601 (DC) tor
Structure ID: LDS_DC_12
Approximate Survey Structure
END DESCRIPTION:
Bridge Culvert--1,0,-1,-1,0
Deck Dist Width WeirC Skew NumUp NumDn MinLoCord MaxHiCord MaxSubmerge Is_Ogee
79,24,3,,14,14,,,0.95,0,1,1,,,
  4572.0  4819.4  4892.0  4909.0  4923.0  4923.0  4923.2  5074.7  5077.0  5077.0
  5078.8  5133.7  5175.6  5234.2
  751.44  739.66  737.98  737.49  737.19  737.19  737.19  733.69  733.73  733.73
  733.77  733.28  733.26  733.66
  690.23  690.23  690.23  690.23  690.23  733.09  733.09  729.64  729.59  690.23
  690.23  690.23  690.23  690.23
  4572.0  4819.4  4892.0  4909.0  4923.0  4923.0  4923.2  5074.7  5077.0  5077.0
  5078.8  5133.7  5175.6  5234.2
  751.44  739.66  737.98  737.49  737.19  737.19  737.19  733.69  733.73  733.73
  733.77  733.28  733.26  733.66
  690.23  690.23  690.23  690.23  690.23  733.09  733.09  729.64  729.59  690.23
  690.23  690.23  690.23  690.23
Pier Skew, UpSta & Num, DnSta & Num=,4961.5,2,4961.5,2,0,0,0,0,0
       2       2
  719.59  734.00
       2       2
  719.00  734.00
Pier Skew, UpSta & Num, DnSta & Num=,5038.5,2,5038.5,2,0,0,0,0,0
       2       2
  718.74  731.53
       2       2
  719.66  731.53
Abutment Skew #Up #Dn=,2,2
  4923.0  4924.0
  733.09  719.91
  4923.0  4924.0
  733.09  723.98
Abutment Skew #Up #Dn=,2,2
  5076.0  5077.0
  720.62  729.59
  5076.0  5077.0
  720.28  729.59
BR Coef=1,1,0,1.25,0,,,0.8,0,2,0,
WSPro=,,,, 1 ,,,, 0 ,,,, 0 ,,,,-1 ,-1 ,-1 , 0 , 0 , 0 , 0 , 0
BC Design=,,0,,0,,,,,,

Type RM Length L Ch R = 1,136221,783,783,783
BEGIN DESCRIPTION:
US 601 (DC) ds
END DESCRIPTION:
XS GIS Cut Line= 4
      1521514.44       829941.85      1521488.66       829756.72
      1521502.72       829531.73      1521558.96       829281.01
#Sta/Elev= 30
  4758.8  754.92  4797.7  753.07  4806.3  752.25  4832.9  746.88  4875.0  735.54
  4891.2  733.58  4915.5  725.87  4936.1  721.17  4944.1  720.94  4967.1  718.42
  4972.0  718.68  4982.0  709.98  5018.0  709.98  5028.0  718.68  5039.5  719.75
  5061.9  719.45  5103.1  721.68  5113.9  721.58  5160.5  723.18  5167.3  725.36
  5174.8  728.69  5193.4  731.20  5218.7  736.38  5234.6  738.49  5249.3  741.13
  5255.8  743.16  5279.9  742.20  5338.3  744.51  5382.3  744.92  5428.1  744.78
#Mann=5,-1,0
  4758.8    0.08       0  4797.7    0.14       0  4972.0   0.045       0
  5028.0    0.14       0  5382.3    0.08       0
#XS Ineff=2,0
    0.00 4870.00  738.52 5130.00    0.00  733.36
Permanent Ineff=
       F       F
Bank Sta=4972,5028
XS Rating Curve= 0
Exp/Cntr=0.5,0.3

Type RM Length L Ch R = 1,135438,438,438,438
BEGIN DESCRIPTION:
Dutchman Creek 155.0
END DESCRIPTION:
XS GIS Cut Line= 4
      1521976.43       829902.79      1522077.20       829572.83
      1522140.42       829367.35      1522013.99       829128.31
#Sta/Elev= 30
  4487.3  749.51  4530.1  747.65  4554.8  745.64  4589.6  742.34  4614.8  737.64
  4655.1  732.12  4687.9  730.84  4739.5  727.49  4805.4  727.36  4850.3  726.50
  4861.2  724.75  4869.8  721.88  4903.3  718.18  4923.7  718.26  4967.1  723.27
  4975.1  721.31  4975.4  714.32  4978.1  709.32  5021.9  709.32  5024.6  714.32
  5029.0  721.99  5058.9  720.97  5072.3  721.41  5081.0  720.25  5110.7  721.99
  5140.0  726.70  5183.8  730.67  5230.0  736.43  5304.1  742.19  5317.7  742.48
#Mann=4,-1,0
  4487.3    0.08       0  4554.8    0.14       0  4975.4   0.045       0
  5024.6    0.14       0
Bank Sta=4975.4,5024.6
XS Rating Curve= 0
Exp/Cntr=0.3,0.1

Type RM Length L Ch R = 1,135000,768,768,768
BEGIN DESCRIPTION:
Dutchman Creek 154.0
END DESCRIPTION:
XS GIS Cut Line= 3
      1522874.98       829824.97      1522487.46       829312.11
      1521974.96       829074.98
#Sta/Elev= 30
  4357.2  747.90  4380.1  747.03  4397.3  744.54  4404.0  745.81  4442.9  744.52
  4548.5  747.45  4577.7  743.50  4656.7  736.86  4737.3  731.71  4759.1  730.74
  4821.2  731.00  4863.6  729.26  4934.1  719.50  4970.7  719.88  4975.4  713.96
  4978.1  708.96  5021.9  708.96  5024.6  713.96  5031.6  719.34  5039.5  721.11
  5081.1  718.81  5141.5  719.20  5180.5  718.06  5218.9  721.93  5236.3  721.59
  5283.0  724.74  5338.0  730.73  5430.5  737.36  5463.9  741.68  5564.7  744.37
#Mann=3,-1,0
  4357.2    0.14       0  4975.4   0.045       0  5024.6    0.14       0
Bank Sta=4975.4,5024.6
XS Rating Curve= 0
Exp/Cntr=0.3,0.1

Type RM Length L Ch R = 1,134232,849,849,849
BEGIN DESCRIPTION:
Dutchman Creek 153.0
END DESCRIPTION:
XS GIS Cut Line= 4
      1523293.48       829203.59      1523079.44       829042.16
      1522766.40       828839.42      1522675.70       828550.47
#Sta/Elev= 30
  4600.5  746.21  4660.1  742.00  4691.0  738.03  4737.0  729.58  4793.9  723.08
  4809.6  722.78  4830.4  720.87  4850.9  720.64  4887.8  717.85  4932.9  716.15
  4952.5  717.74  4954.1  715.45  4961.7  713.32  4966.7  716.53  4975.4  713.23
  4978.1  708.23  5021.9  708.23  5024.6  713.23  5027.5  717.52  5030.9  718.20
  5067.1  718.33  5113.7  716.45  5145.2  718.64  5188.5  717.85  5209.4  719.91
  5285.8  722.50  5311.1  724.05  5398.9  724.03  5504.1  729.18  5544.4  730.00
#Mann=3,-1,0
  4600.5    0.14       0  4975.4   0.045       0  5024.6    0.14       0
#XS Ineff=2,0
       0                 5289.70    0.00  741.63
Permanent Ineff=
       F       F
Bank Sta=4975.4,5024.6
XS Rating Curve= 0
Exp/Cntr=0.3,0.1