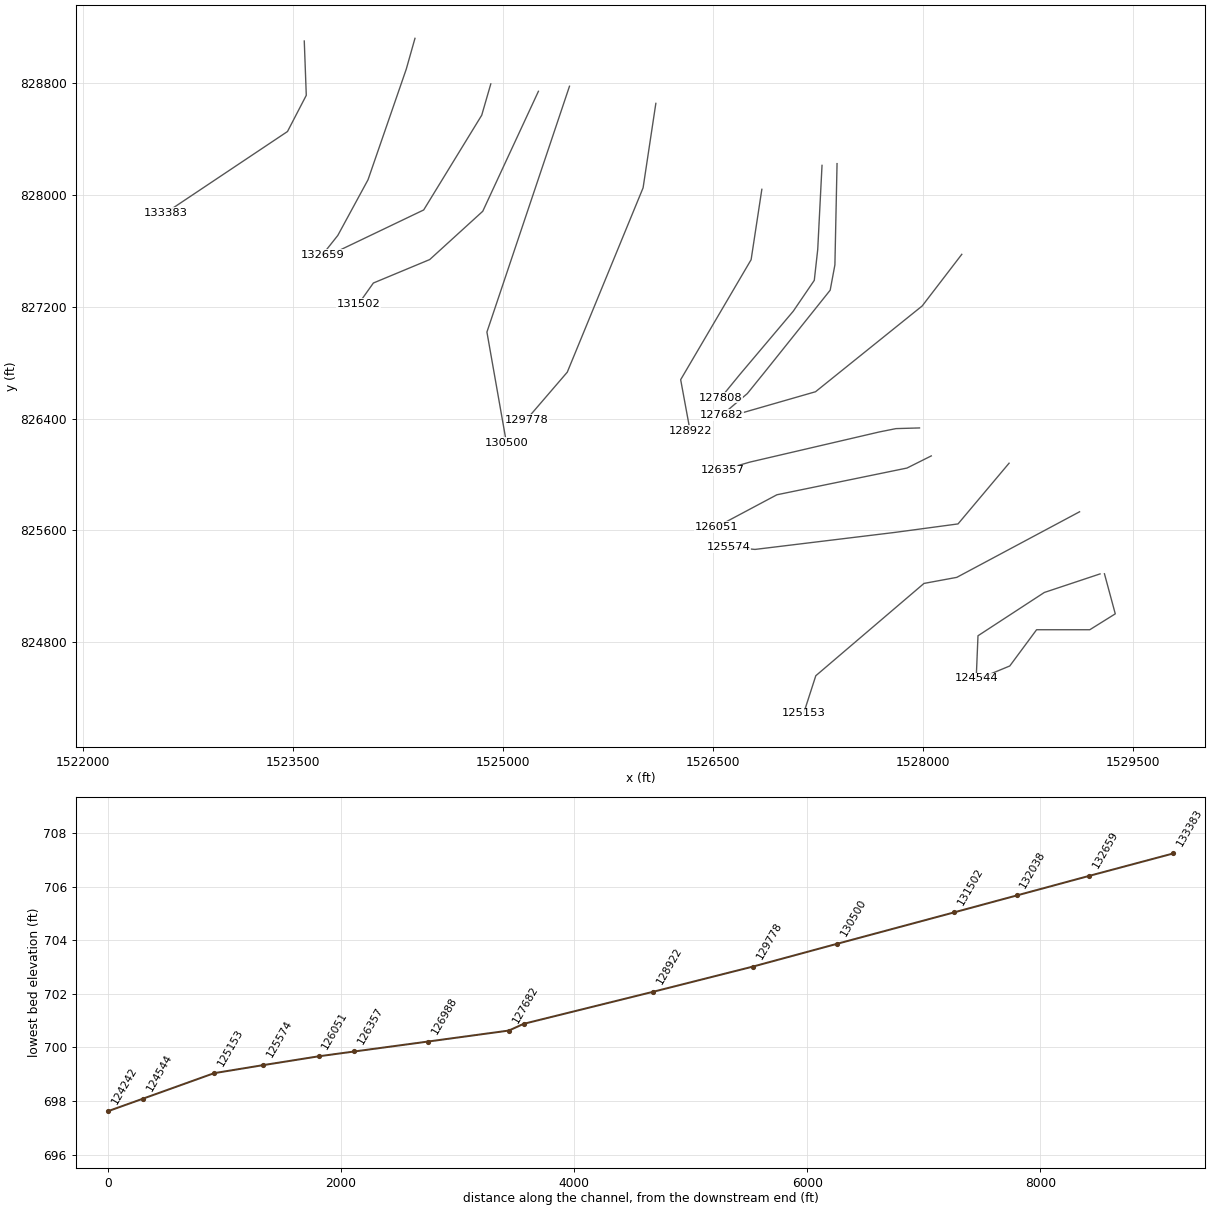
HEC-RAS study Dutchman Creek.prj: Dutchman Creek Limited Detail Study

--- Dutchman Creek.g01 (geometry) --- (continued)

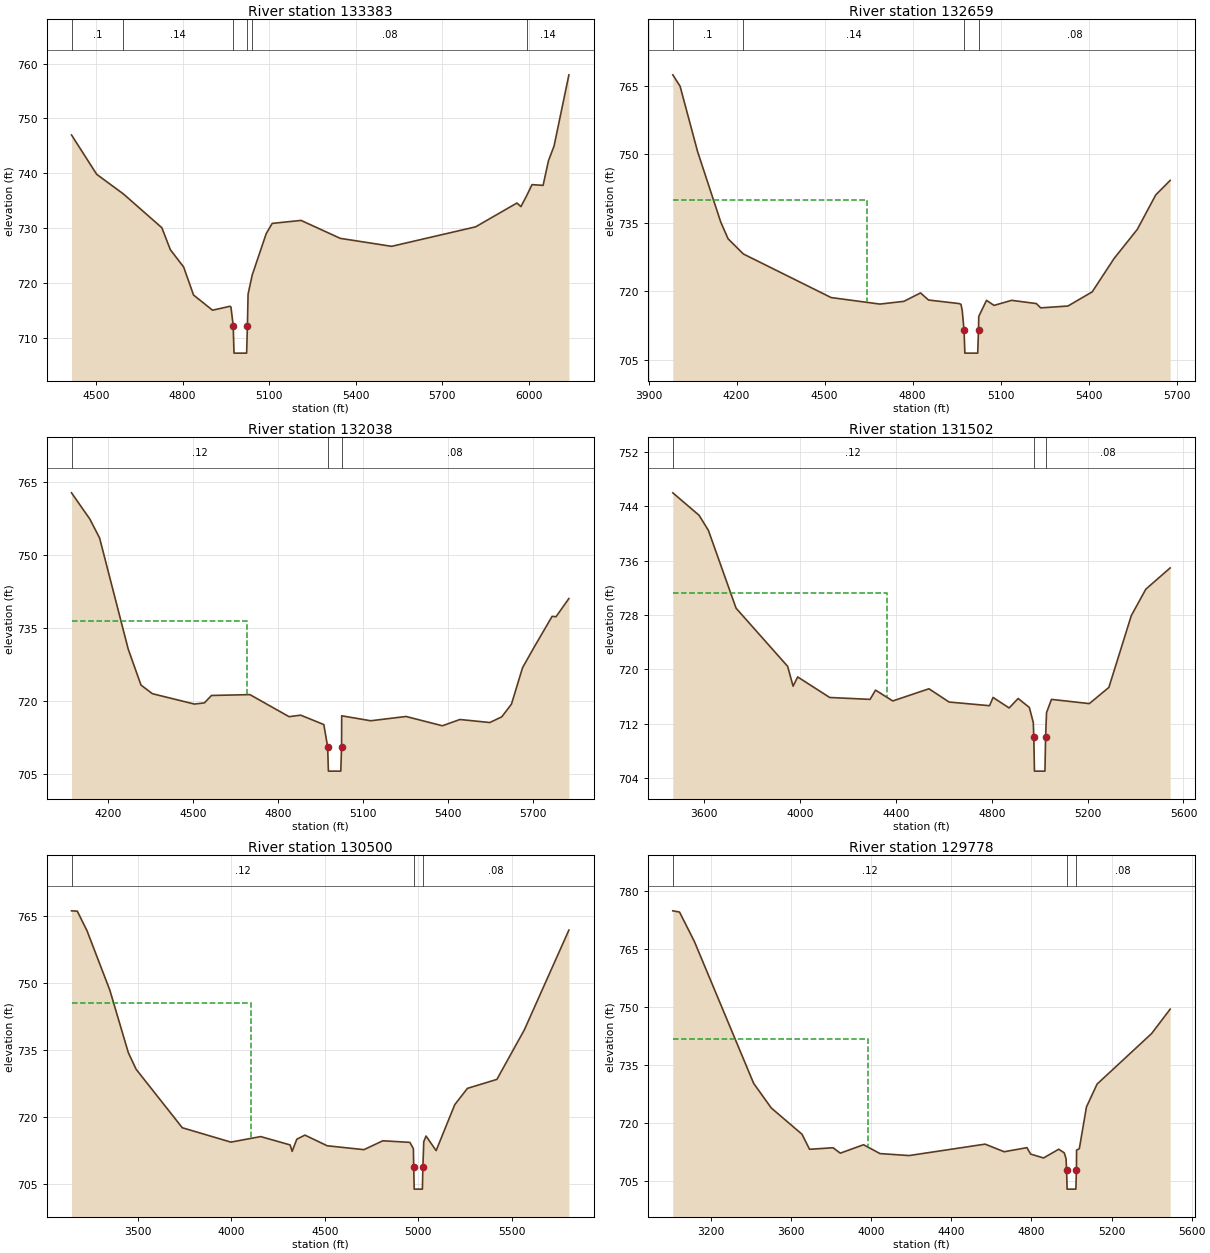
Type RM Length L Ch R = 1,133383,724,724,724
BEGIN DESCRIPTION:
Dutchman Creek 152.0
END DESCRIPTION:
XS GIS Cut Line= 4
      1523580.94       829098.15      1523595.31       828710.06
      1523461.15       828451.32      1522593.90       827871.56
#Sta/Elev= 30
  4415.3  746.99  4502.3  739.83  4594.9  736.25  4728.2  730.09  4757.6  726.09
  4803.7  722.93  4838.1  717.82  4903.7  715.06  4964.6  715.78  4967.6  715.63
  4975.4  712.24  4978.1  707.24  5021.9  707.24  5024.6  712.24  5026.9  717.98
  5041.0  721.43  5089.6  729.00  5110.5  730.88  5210.5  731.42  5346.5  728.15
  5524.2  726.70  5815.1  730.25  5958.3  734.59  5972.2  733.94  5991.8  735.91
  6010.5  737.94  6048.9  737.81  6067.7  742.32  6086.9  744.97  6138.3  757.95
#Mann=6,-1,0
  4415.3     0.1       0  4594.9    0.14       0  4975.4   0.045       0
  5024.6    0.14       0  5041.0    0.08       0  5991.8    0.14       0
Bank Sta=4975.4,5024.6
XS Rating Curve= 0
Exp/Cntr=0.3,0.1

Type RM Length L Ch R = 1,132659,621,621,621
BEGIN DESCRIPTION:
Dutchman Creek 151.0
END DESCRIPTION:
XS GIS Cut Line= 5
      1524371.52       829117.32      1524309.23       828896.92
      1524036.12       828106.34      1523820.51       827708.65
      1523710.30       827569.68
#Sta/Elev= 30
  3982.7  767.45  4007.5  764.95  4067.3  750.58  4146.0  735.17  4171.1  731.48
  4223.2  728.15  4522.3  718.59  4688.7  717.16  4770.3  717.76  4827.0  719.61
  4854.2  718.05  4958.4  717.27  4964.9  717.11  4969.2  715.69  4975.4  711.40
  4978.1  706.40  5021.9  706.40  5024.6  711.40  5025.5  714.45  5051.9  717.98
  5077.4  716.87  5137.7  717.98  5221.8  717.27  5236.6  716.33  5329.2  716.73
  5412.2  719.84  5486.8  727.17  5565.6  733.52  5628.7  741.10  5677.9  744.29
#Mann=4,-1,0
  3982.7     0.1       0  4223.2    0.14       0  4975.4   0.045       0
  5024.6    0.08       0
#XS Ineff=2,0
    0.00 4644.40  740.02               0
Permanent Ineff=
       F       F
Bank Sta=4975.4,5024.6
XS Rating Curve= 0
Exp/Cntr=0.3,0.1

Type RM Length L Ch R = 1,132038,536,536,536
BEGIN DESCRIPTION:
Dutchman Creek 150.0
END DESCRIPTION:
XS GIS Cut Line= 4
      1524912.95       828791.52      1524848.20       828567.82
      1524433.81       827890.73      1523774.98       827574.99
#Sta/Elev= 30
  4070.5  762.86  4135.3  757.46  4169.7  753.57  4270.8  730.74  4315.9  723.36
  4356.3  721.58  4504.8  719.45  4539.9  719.69  4565.0  721.22  4700.8  721.39
  4839.2  716.86  4880.1  717.17  4962.0  715.24  4975.4  710.67  4978.1  705.67
  5021.9  705.67  5024.6  710.67  5025.0  717.04  5127.6  716.02  5252.4  716.90
  5380.7  714.99  5442.8  716.28  5548.5  715.66  5590.7  716.83  5624.9  719.44
  5664.1  726.93  5703.9  731.03  5768.5  737.48  5782.3  737.40  5827.8  741.14
#Mann=3,-1,0
  4070.5    0.12       0  4975.4   0.045       0  5024.6    0.08       0
#XS Ineff=2,0
    0.00 4689.90  736.56               0
Permanent Ineff=
       F       F
Bank Sta=4975.4,5024.6
XS Rating Curve= 0
Exp/Cntr=0.3,0.1

Type RM Length L Ch R = 1,131502,1002,1002,1002
BEGIN DESCRIPTION:
Dutchman Creek 149.0
END DESCRIPTION:
XS GIS Cut Line= 5
      1525253.14       828738.79      1524855.45       827881.14
      1524476.93       827536.16      1524074.46       827368.46
      1523969.02       827219.90
#Sta/Elev= 30
  3468.8  745.96  3578.4  742.66  3617.3  740.44  3732.8  729.00  3948.0  720.45
  3970.8  717.53  3989.9  718.89  4123.6  715.87  4292.0  715.59  4314.8  716.95
  4386.8  715.36  4537.8  717.15  4621.8  715.20  4790.6  714.66  4805.4  715.87
  4872.4  714.33  4910.1  715.72  4956.8  714.40  4973.2  712.19  4975.4  710.04
  4978.1  705.04  5021.9  705.04  5024.6  710.04  5028.5  713.64  5049.1  715.59
  5207.2  714.97  5288.7  717.35  5382.3  727.91  5443.0  731.80  5544.5  734.92
#Mann=3,-1,0
  3468.8    0.12       0  4975.4   0.045       0  5024.6    0.08       0
#XS Ineff=2,0
    0.00 4363.10  731.29               0
Permanent Ineff=
       F       F
Bank Sta=4975.4,5024.6
XS Rating Curve= 0
Exp/Cntr=0.3,0.1

Type RM Length L Ch R = 1,130500,722,722,722
BEGIN DESCRIPTION:
Dutchman Creek 148.0
END DESCRIPTION:
XS GIS Cut Line= 3
      1525475.00       828775.00      1524885.32       827017.80
      1525025.00       826225.01
#Sta/Elev= 30
  3146.5  766.26  3177.4  766.18  3229.2  761.80  3351.4  748.46  3450.1  734.46
  3492.0  730.73  3738.6  717.63  3998.4  714.41  4157.6  715.65  4315.0  713.78
  4325.7  712.34  4350.7  715.06  4394.0  715.98  4513.0  713.59  4709.5  712.72
  4810.7  714.71  4955.1  714.35  4973.8  712.94  4975.4  708.87  4978.1  703.87
  5021.9  703.87  5024.6  708.87  5029.3  714.51  5041.4  715.77  5095.4  712.51
  5194.9  722.80  5262.6  726.46  5420.1  728.47  5566.8  739.57  5805.0  761.94
#Mann=3,-1,0
  3146.5    0.12       0  4975.4   0.045       0  5024.6    0.08       0
#XS Ineff=2,0
    0.00 4103.50  745.62               0
Permanent Ineff=
       F       F
Bank Sta=4975.4,5024.6
XS Rating Curve= 0
Exp/Cntr=0.3,0.1

Type RM Length L Ch R = 1,129778,856,856,856
BEGIN DESCRIPTION:
Dutchman Creek 147.0
END DESCRIPTION:
XS GIS Cut Line= 4
      1526091.63       828652.52      1526000.60       828048.84
      1525459.17       826731.20      1525166.93       826391.05
#Sta/Elev= 30
  3009.2  774.91  3042.8  774.59  3117.1  766.97  3412.9  730.34  3500.9  723.98
  3654.3  717.20  3692.0  713.31  3809.4  713.71  3845.5  712.31  3961.6  714.49
  4043.8  712.20  4188.9  711.69  4568.5  714.64  4663.7  712.68  4777.7  713.73
  4795.9  712.07  4860.6  711.07  4936.2  713.33  4963.7  712.40  4972.7  710.90
  4975.4  708.02  4978.1  703.02  5021.9  703.02  5024.6  708.02  5025.3  713.10
  5039.0  713.45  5074.6  724.24  5127.7  730.15  5400.2  743.22  5492.7  749.52
#Mann=3,-1,0
  3009.2    0.12       0  4975.4   0.045       0  5024.6    0.08       0
#XS Ineff=2,0
    0.00 3983.70  741.84               0
Permanent Ineff=
       F       F
Bank Sta=4975.4,5024.6
XS Rating Curve= 0
Exp/Cntr=0.3,0.1

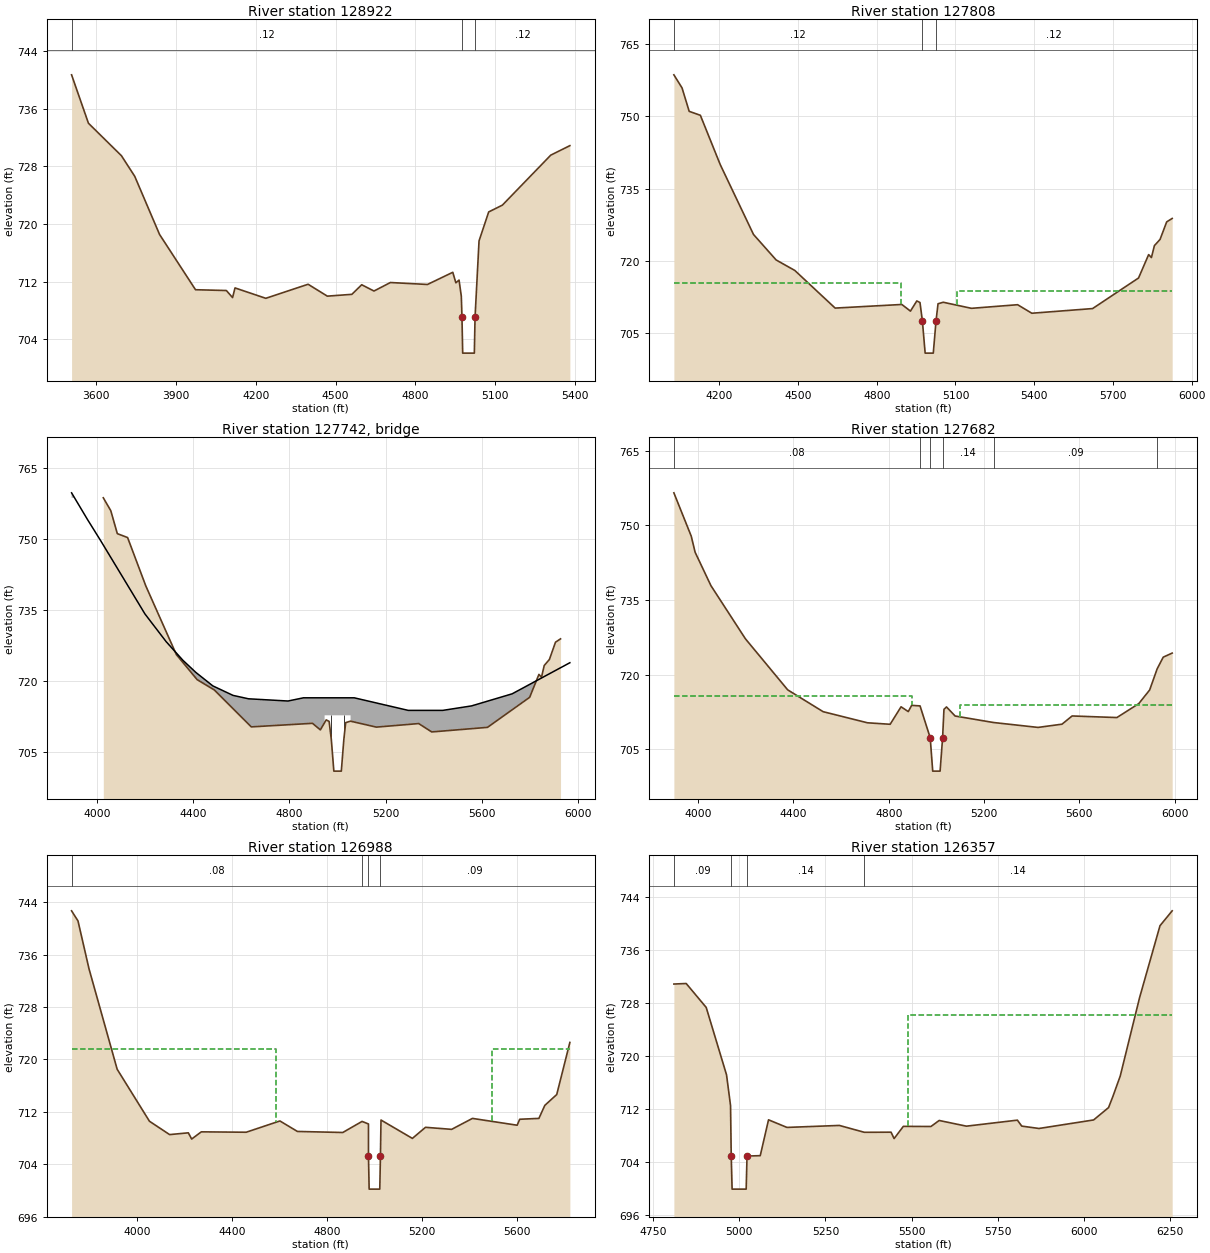
Type RM Length L Ch R = 1,128922,1114,1114,1114
BEGIN DESCRIPTION:
Dutchman Creek 146.0
END DESCRIPTION:
XS GIS Cut Line= 4
      1526848.67       828038.26      1526772.02       827535.20
      1526268.92       826677.54      1526336.00       826313.37
#Sta/Elev= 30
  3507.6  740.71  3571.0  733.99  3695.1  729.48  3745.1  726.62  3838.4  718.55
  3973.6  710.88  4089.5  710.77  4112.9  709.79  4122.1  711.13  4237.8  709.69
  4396.9  711.64  4469.1  709.99  4561.4  710.24  4598.4  711.57  4644.6  710.70
  4706.3  711.88  4845.7  711.61  4940.9  713.30  4952.4  711.84  4964.4  712.22
  4972.9  709.99  4975.4  707.08  4978.1  702.08  5021.9  702.08  5024.6  707.08
  5039.6  717.66  5075.9  721.68  5127.3  722.62  5309.2  729.56  5381.1  730.88
#Mann=3,-1,0
  3507.6    0.12       0  4975.4   0.045       0  5024.6    0.12       0
Bank Sta=4975.4,5024.6
XS Rating Curve= 0
Exp/Cntr=0.5,0.3

Type RM Length L Ch R = 1,127808,126,126,126
BEGIN DESCRIPTION:
Howell Rd (DC) us
END DESCRIPTION:
XS GIS Cut Line= 6
      1527278.37       828209.42      1527247.71       827608.42
      1527223.18       827387.63      1527072.92       827166.84
      1526692.67       826716.06      1526554.65       826547.37
#Sta/Elev= 30
  4027.1  758.65  4058.2  755.93  4085.4  751.07  4128.0  750.25  4203.6  740.03
  4330.5  725.51  4416.7  720.22  4487.9  718.04  4641.6  710.23  4895.7  710.98
  4928.5  709.60  4952.7  711.71  4964.8  711.39  4974.0  707.58  4984.5  700.88
  5015.5  700.88  5026.0  707.58  5033.6  711.13  5053.4  711.44  5161.0  710.18
  5336.8  710.93  5391.0  709.16  5622.6  710.13  5797.7  716.48  5836.1  721.33
  5846.7  720.72  5858.1  723.20  5879.6  724.48  5904.8  728.12  5925.8  728.84
#Mann=3,-1,0
  4027.1    0.12       0  4974.0   0.045       0  5026.0    0.12       0
#XS Ineff=2,0
    0.00 4893.00  715.53 5107.00    0.00  713.68
Permanent Ineff=
       F       F
Bank Sta=4974,5026
XS Rating Curve= 0
Exp/Cntr=0.5,0.3

Type RM Length L Ch R =3,127742,,,
BEGIN DESCRIPTION:
Howell Rd (DC) tor
Structure ID: LDS_DC_11
Approximate Survey Structure
END DESCRIPTION:
Bridge Culvert--1,0,-1,-1,0
Deck Dist Width WeirC Skew NumUp NumDn MinLoCord MaxHiCord MaxSubmerge Is_Ogee
53,26,3,,22,22,,,0.95,0,1,1,,,
  3895.4  3960.7  4015.2  4200.2  4288.0  4358.2  4411.5  4481.8  4565.8  4630.0
  4794.2  4858.6  4946.0  4946.0  5054.0  5054.0  5069.0  5293.6  5436.5  5556.5
  5724.9  5964.6
  759.70  754.12  749.67  734.09  728.25  724.28  721.74  718.90  716.89  716.17
  715.70  716.38  716.38  716.38  716.38  716.38  716.38  713.72  713.72  714.67
  717.22  723.79
  680.88  680.88  680.88  680.88  680.88  680.88  680.88  680.88  680.88  680.88
  680.88  680.88  680.88  712.68  712.68  680.88  680.88  680.88  680.88  680.88
  680.88  680.88
  3895.4  3960.7  4015.2  4200.2  4288.0  4358.2  4411.5  4481.8  4565.8  4630.0
  4794.2  4858.6  4946.0  4946.0  5054.0  5054.0  5069.0  5293.6  5436.5  5556.5
  5724.9  5964.6
  759.70  754.12  749.67  734.09  728.25  724.28  721.74  718.90  716.89  716.17
  715.70  716.38  716.38  716.38  716.38  716.38  716.38  713.72  713.72  714.67
  717.22  723.79
  680.88  680.88  680.88  680.88  680.88  680.88  680.88  680.88  680.88  680.88
  680.88  680.88  680.88  712.68  712.68  680.88  680.88  680.88  680.88  680.88
  680.88  680.88
Pier Skew, UpSta & Num, DnSta & Num=,4973,2,4973,2,0,0,0,0,0
       1       1
  708.05  712.68
       1       1
  707.14  712.68
Pier Skew, UpSta & Num, DnSta & Num=,5027,2,5027,2,0,0,0,0,0
       1       1
  708.05  712.68
       1       1
  708.33  712.68
Abutment Skew #Up #Dn=,2,2
  4946.0  4947.0
  712.68  710.91
  4946.0  4947.0
  712.68  711.55
Abutment Skew #Up #Dn=,2,2
  5053.0  5054.0
  711.44  712.68
  5053.0  5054.0
  712.98  712.68
BR Coef=1,1,0,1.25,0,,,0.8,0,2,0,
WSPro=,,,, 1 ,,,, 0 ,,,, 0 ,,,,-1 ,-1 ,-1 , 0 , 0 , 0 , 0 , 0
BC Design=,,0,,0,,,,,,

Type RM Length L Ch R = 1,127682,694,694,694
BEGIN DESCRIPTION:
Howell Rd (DC) ds
END DESCRIPTION:
XS GIS Cut Line= 6
      1527385.70       828221.75      1527370.37       827498.02
      1527336.64       827317.10      1526873.60       826737.53
      1526744.80       826578.07      1526563.87       826424.74
#Sta/Elev= 30
  3897.9  756.53  3970.8  747.82  3987.0  744.60  4053.5  737.88  4198.2  727.21
  4375.8  716.95  4524.5  712.57  4710.5  710.34  4805.8  710.04  4851.6  713.55
  4881.9  712.59  4896.2  713.84  4931.3  713.73  4974.0  707.33  4984.5  700.63
  5015.5  700.63  5026.0  707.33  5031.7  713.04  5042.4  713.52  5078.6  711.70
  5240.2  710.39  5426.6  709.41  5527.3  710.06  5569.7  711.71  5757.7  711.39
  5849.6  714.19  5895.3  716.93  5926.6  721.16  5952.2  723.52  5989.8  724.34
#Mann=6,-1,0
  3897.9    0.08       0  4931.3    0.14       0  4974.0   0.045       0
  5026.0    0.14       0  5240.2    0.09       0  5926.6    0.12       0
#XS Ineff=2,0
    0.00 4899.00  715.80 5101.00    0.00  713.94
Permanent Ineff=
       F       F
Bank Sta=4974,5026
XS Rating Curve= 0
Exp/Cntr=0.5,0.3

Type RM Length L Ch R = 1,126988,631,631,631
BEGIN DESCRIPTION:
Dutchman Creek 145.0
END DESCRIPTION:
XS GIS Cut Line= 4
      1528276.50       827573.51      1527993.83       827204.60
      1527231.99       826591.30      1526599.56       826409.23
#Sta/Elev= 30
  3723.0  742.68  3750.0  741.14  3796.6  733.82  3915.2  718.51  4051.3  710.58
  4136.3  708.54  4215.3  708.81  4229.3  707.86  4270.0  708.96  4459.1  708.90
  4601.4  710.62  4675.1  709.02  4866.4  708.86  4947.7  710.55  4974.7  710.16
  4974.8  705.22  4977.6  700.22  5022.4  700.22  5025.2  705.22  5027.6  710.76
  5159.9  707.96  5215.2  709.65  5325.5  709.34  5413.1  711.01  5601.6  709.97
  5612.4  710.88  5693.3  711.01  5718.3  713.00  5768.5  714.65  5823.9  722.60
#Mann=4,-1,0
  3723.0    0.08       0  4947.7    0.14       0  4974.8   0.045       0
  5025.2    0.09       0
#XS Ineff=2,0
    0.00 4585.60  721.67 5496.50    0.00  721.67
Permanent Ineff=
       F       F
Bank Sta=4974.8,5025.2
XS Rating Curve= 0
Exp/Cntr=0.3,0.1

Type RM Length L Ch R = 1,126357,306,306,306
BEGIN DESCRIPTION:
Dutchman Creek 144.0
END DESCRIPTION:
XS GIS Cut Line= 5
      1527974.65       826332.56      1527806.96       826327.77
      1527687.18       826303.81      1526762.43       826088.20
      1526565.94       826030.69
#Sta/Elev= 30
  4810.9  730.86  4846.6  730.94  4904.6  727.32  4963.5  717.13  4975.1  712.48
  4977.1  704.85  4979.6  699.85  5020.4  699.85  5022.9  704.85  5061.2  704.91
  5085.2  710.33  5138.6  709.18  5290.5  709.48  5363.0  708.44  5440.3  708.46
  5449.2  707.49  5475.9  709.34  5555.9  709.32  5579.8  710.23  5658.7  709.37
  5806.5  710.28  5819.1  709.38  5869.0  709.02  6027.4  710.31  6070.7  712.18
  6083.3  713.87  6104.6  716.96  6160.7  728.82  6219.8  739.68  6255.1  741.93
#Mann=4,-1,0
  4810.9    0.09       0  4977.1   0.045       0  5022.9    0.14       0
  5363.0    0.14       0
#XS Ineff=2,0
       0                 5490.30    0.00  726.22
Permanent Ineff=
       F       F
Bank Sta=4977.1,5022.9
XS Rating Curve= 0
Exp/Cntr=0.3,0.1

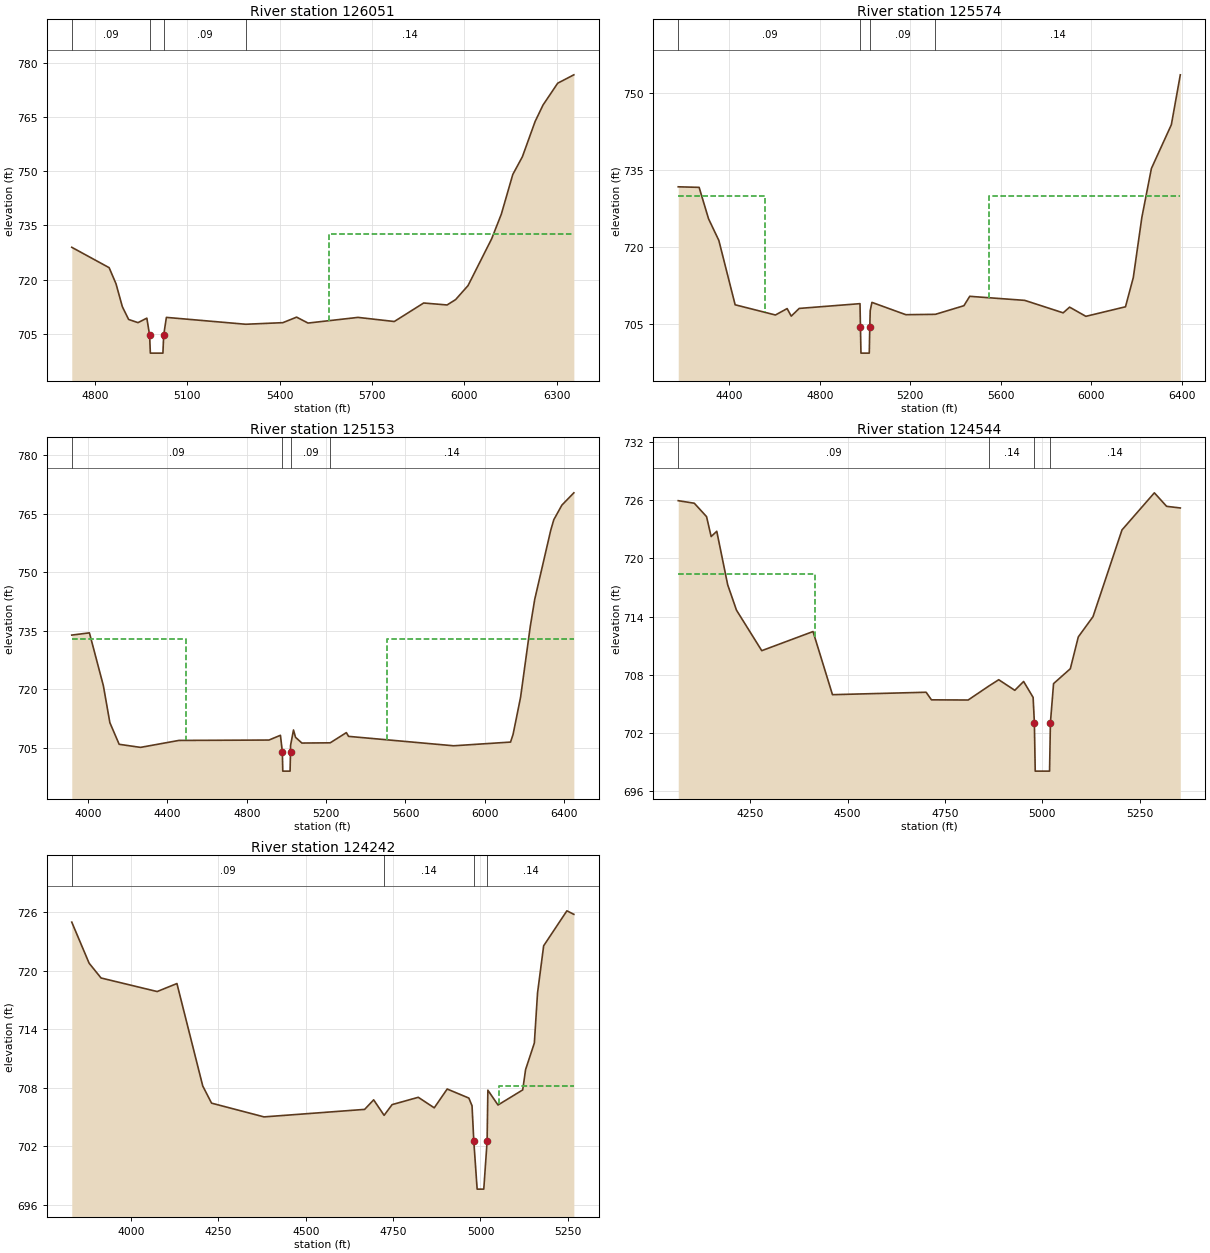
Type RM Length L Ch R = 1,126051,477,477,477
BEGIN DESCRIPTION:
Dutchman Creek 143.0
END DESCRIPTION:
XS GIS Cut Line= 4
      1528058.60       826132.61      1527885.02       826045.82
      1526956.20       825854.85      1526524.96       825624.98
#Sta/Elev= 30
  4724.3  728.96  4845.7  723.32  4868.0  718.87  4888.6  712.52  4909.0  708.99
  4939.4  708.11  4968.2  709.35  4977.1  704.67  4979.6  699.67  5020.4  699.67
  5022.9  704.67  5031.7  709.56  5289.3  707.66  5409.9  708.10  5454.7  709.63
  5491.8  707.99  5654.1  709.56  5772.0  708.42  5867.4  713.54  5943.5  713.00
  5971.2  714.48  6011.6  718.36  6088.4  731.33  6119.7  738.12  6156.9  749.10
  6188.2  754.03  6229.4  763.76  6255.1  768.32  6302.8  774.37  6355.3  776.69
#Mann=4,-1,0
  4724.3    0.09       0  4977.1   0.045       0  5022.9    0.09       0
  5289.3    0.14       0
#XS Ineff=2,0
       0                 5559.10    0.00  732.70
Permanent Ineff=
       F       F
Bank Sta=4977.1,5022.9
XS Rating Curve= 0
Exp/Cntr=0.3,0.1

Type RM Length L Ch R = 1,125574,421,421,421
BEGIN DESCRIPTION:
Dutchman Creek 142.0
END DESCRIPTION:
XS GIS Cut Line= 5
      1528614.19       826080.54      1528249.60       825646.52
      1527798.22       825585.75      1526799.95       825464.22
      1526608.96       825481.59
#Sta/Elev= 30
  4173.8  731.75  4266.2  731.64  4307.9  725.51  4353.4  721.29  4425.4  708.76
  4603.6  706.77  4655.2  708.02  4673.4  706.55  4708.6  708.05  4977.4  708.98
  4979.4  704.34  4981.6  699.34  5018.4  699.34  5020.6  704.34  5022.6  707.62
  5030.1  709.23  5180.0  706.83  5310.8  706.90  5436.8  708.58  5462.5  710.41
  5705.8  709.62  5875.6  707.19  5904.1  708.30  5976.0  706.51  6151.1  708.37
  6185.6  714.05  6223.5  725.79  6265.7  735.32  6353.9  743.85  6393.5  753.57
#Mann=4,-1,0
  4173.8    0.09       0  4979.4   0.045       0  5020.6    0.09       0
  5310.8    0.14       0
#XS Ineff=2,0
    0.00 4557.10  729.96 5549.50    0.00  729.96
Permanent Ineff=
       F       F
Bank Sta=4979.4,5020.6
XS Rating Curve= 0
Exp/Cntr=0.3,0.1

Type RM Length L Ch R = 1,125153,609,609,609
BEGIN DESCRIPTION:
Dutchman Creek 141.0
END DESCRIPTION:
XS GIS Cut Line= 5
      1529117.63       825733.30      1528240.92       825264.57
      1528006.55       825221.17      1527233.98       824561.45
      1527147.17       824292.33
#Sta/Elev= 30
  3917.8  733.88  4006.8  734.45  4077.1  720.92  4109.9  711.45  4156.8  705.91
  4264.3  705.12  4457.6  706.90  4912.1  707.00  4969.8  708.22  4979.4  704.04
  4981.6  699.04  5018.4  699.04  5020.6  704.04  5020.8  705.60  5035.6  709.58
  5045.8  707.71  5077.8  706.23  5220.8  706.29  5302.1  708.90  5313.3  707.94
  5843.0  705.53  6129.9  706.48  6142.6  708.45  6180.4  717.93  6229.3  736.07
  6251.7  743.01  6332.5  760.72  6347.9  763.42  6388.7  767.16  6449.0  770.31
#Mann=4,-1,0
  3917.8    0.09       0  4979.4   0.045       0  5020.6    0.09       0
  5220.8    0.14       0
#XS Ineff=2,0
    0.00 4492.00  732.82 5508.00    0.00  732.82
Permanent Ineff=
       F       F
Bank Sta=4979.4,5020.6
XS Rating Curve= 0
Exp/Cntr=0.3,0.1

Type RM Length L Ch R = 1,124544,302,302,302
BEGIN DESCRIPTION:
Dutchman Creek 140.0
END DESCRIPTION:
XS GIS Cut Line= 4
      1529263.87       825289.19      1528865.93       825156.55
      1528392.23       824847.07      1528379.60       824543.93
#Sta/Elev= 30
  4065.3  725.93  4106.5  725.67  4138.0  724.29  4149.8  722.24  4164.2  722.78
  4192.2  717.28  4214.8  714.66  4279.7  710.49  4411.3  712.46  4461.2  705.96
  4701.6  706.21  4715.2  705.43  4809.4  705.41  4863.7  706.88  4887.9  707.50
  4929.2  706.41  4951.8  707.32  4976.2  705.68  4979.4  703.09  4981.6  698.09
  5018.4  698.09  5020.6  703.09  5028.7  707.10  5071.7  708.63  5092.2  711.91
  5129.9  713.99  5204.3  722.92  5287.4  726.74  5318.8  725.35  5354.0  725.18
#Mann=4,-1,0
  4065.3    0.09       0  4863.7    0.14       0  4979.4   0.045       0
  5020.6    0.14       0
#XS Ineff=2,0
    0.00 4416.50  718.37               0
Permanent Ineff=
       F       F
Bank Sta=4979.4,5020.6
XS Rating Curve= 0
Exp/Cntr=0.5,0.3

Type RM Length L Ch R = 1,124242,101,101,101
BEGIN DESCRIPTION:
Murchison Rd (DC) us
END DESCRIPTION:
XS GIS Cut Line= 6
      1529295.28       825290.18      1529372.62       825003.79
      1529190.66       824890.18      1528810.67       824890.18
      1528619.26       824631.22      1528422.25       824549.60
#Sta/Elev= 30
  3830.6  725.01  3880.2  720.80  3914.4  719.28  4074.9  717.89  4131.5  718.71
  4205.4  708.20  4230.6  706.44  4380.7  705.03  4668.6  705.80  4694.4  706.78
  4724.3  705.19  4747.2  706.29  4822.1  707.04  4867.8  705.96  4904.8  707.89
  4966.8  706.96  4975.9  706.17  4981.0  702.52  4990.5  697.62  5009.5  697.62
  5019.0  702.52  5021.2  707.77  5050.2  706.25  5120.9  707.80  5129.1  709.88
  5154.2  712.61  5163.3  717.74  5180.8  722.58  5247.3  726.17  5267.2  725.81
#Mann=4,-1,0
  3830.6    0.09       0  4724.3    0.14       0  4981.0   0.045       0
  5019.0    0.14       0
#XS Ineff=2,0
    0.00 4946.50  705.60 5053.50    0.00  708.23
Permanent Ineff=
       F       F
Bank Sta=4981,5019
XS Rating Curve= 0
Exp/Cntr=0.5,0.3