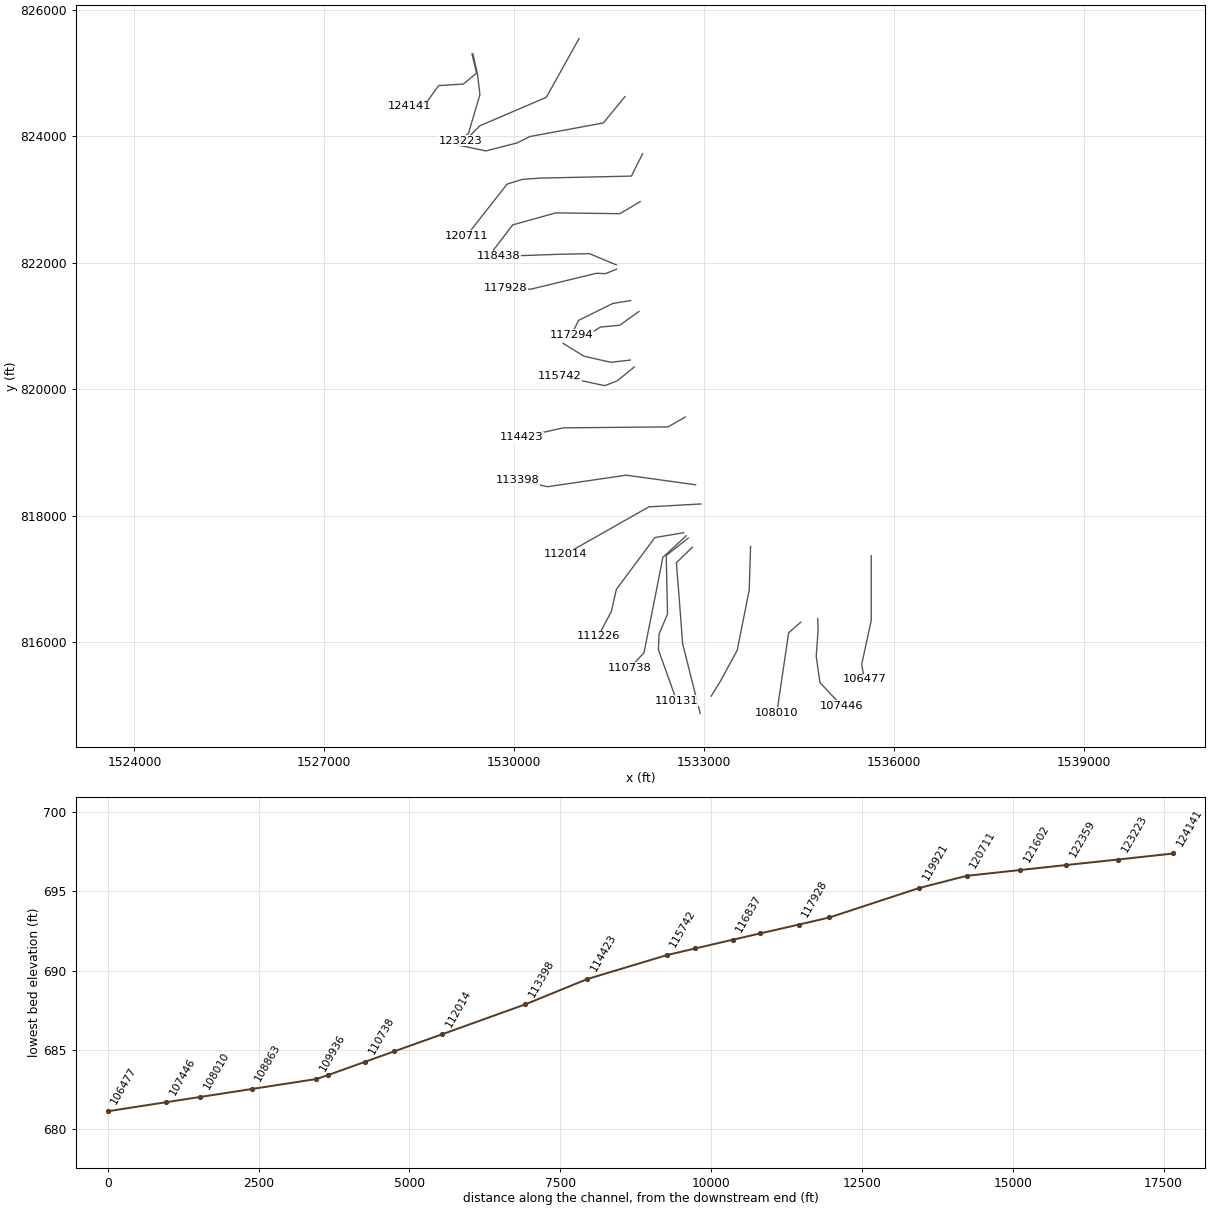
HEC-RAS study Dutchman Creek.prj: Dutchman Creek Limited Detail Study

--- Dutchman Creek.g01 (geometry) --- (continued)

Type RM Length L Ch R =3,124203,,,
BEGIN DESCRIPTION:
Murchison Rd (DC) tor
Structure ID: LDS_DC_10
Approximate Survey Structure
END DESCRIPTION:
Bridge Culvert--1,0,-1,-1,0
Deck Dist Width WeirC Skew NumUp NumDn MinLoCord MaxHiCord MaxSubmerge Is_Ogee
30,18,3,,50,50,,,0.95,0,1,1,,,
  3836.9  3860.1  3871.3  3894.5  3920.6  3937.9  3950.3  3978.8  3993.7  4039.2
  4072.3  4084.8  4110.0  4121.7  4127.4  4131.9  4155.8  4203.5  4220.8  4230.8
  4246.1  4253.3  4263.1  4330.4  4354.1  4396.3  4597.3  4642.9  4680.3  4761.6
  4804.1  4901.7  4932.1  4942.5  4959.1  4976.5  4976.5  5023.5  5023.5  5028.6
  5065.1  5095.5  5112.1  5130.7  5147.4  5176.0  5196.8  5214.0  5224.8  5236.9
  725.04  722.67  721.71  720.41  718.98  718.34  718.36  718.59  718.53  718.15
  717.84  717.71  717.69  718.63  719.06  719.16  718.67  715.38  712.41  710.32
  707.90  707.11  706.62  705.81  705.58  705.52  706.57  706.65  706.60  706.02
  706.29  707.05  708.49  708.89  709.04  708.82  708.82  708.63  708.63  708.61
  708.33  708.75  709.07  709.60  710.74  712.13  713.21  713.84  713.97  714.00
  677.46  677.46  677.46  677.46  677.46  677.46  677.46  677.46  677.46  677.46
  677.46  677.46  677.46  677.46  677.46  677.46  677.46  677.46  677.46  677.46
  677.46  677.46  677.46  677.46  677.46  677.46  677.46  677.46  677.46  677.46
  677.46  677.46  677.46  677.46  677.46  677.46  706.22  706.22  677.46  677.46
  677.46  677.46  677.46  677.46  677.46  677.46  677.46  677.46  677.46  677.46
  3836.9  3860.1  3871.3  3894.5  3920.6  3937.9  3950.3  3978.8  3993.7  4039.2
  4072.3  4084.8  4110.0  4121.7  4127.4  4131.9  4155.8  4203.5  4220.8  4230.8
  4246.1  4253.3  4263.1  4330.4  4354.1  4396.3  4597.3  4642.9  4680.3  4761.6
  4804.1  4901.7  4932.1  4942.5  4959.1  4976.5  4976.5  5023.5  5023.5  5028.6
  5065.1  5095.5  5112.1  5130.7  5147.4  5176.0  5196.8  5214.0  5224.8  5236.9
  725.04  722.67  721.71  720.41  718.98  718.34  718.36  718.59  718.53  718.15
  717.84  717.71  717.69  718.63  719.06  719.16  718.67  715.38  712.41  710.32
  707.90  707.11  706.62  705.81  705.58  705.52  706.57  706.65  706.60  706.02
  706.29  707.05  708.49  708.89  709.04  708.82  708.82  708.63  708.63  708.61
  708.33  708.75  709.07  709.60  710.74  712.13  713.21  713.84  713.97  714.00
  677.46  677.46  677.46  677.46  677.46  677.46  677.46  677.46  677.46  677.46
  677.46  677.46  677.46  677.46  677.46  677.46  677.46  677.46  677.46  677.46
  677.46  677.46  677.46  677.46  677.46  677.46  677.46  677.46  677.46  677.46
  677.46  677.46  677.46  677.46  677.46  677.46  706.22  706.22  677.46  677.46
  677.46  677.46  677.46  677.46  677.46  677.46  677.46  677.46  677.46  677.46
Abutment Skew #Up #Dn=,2,2
  4976.5  4980.0
  706.22  703.24
  4976.5  4980.0
  706.22  702.59
Abutment Skew #Up #Dn=,2,2
  5020.0  5023.5
  704.91  706.22
  5020.0  5023.5
  702.45  706.22
BR Coef=1,1,0,1.25,0,,,0.8,0,2,0,
WSPro=,,,, 1 ,,,, 0 ,,,, 0 ,,,,-1 ,-1 ,-1 , 0 , 0 , 0 , 0 , 0
BC Design=,,0,,0,,,,,,

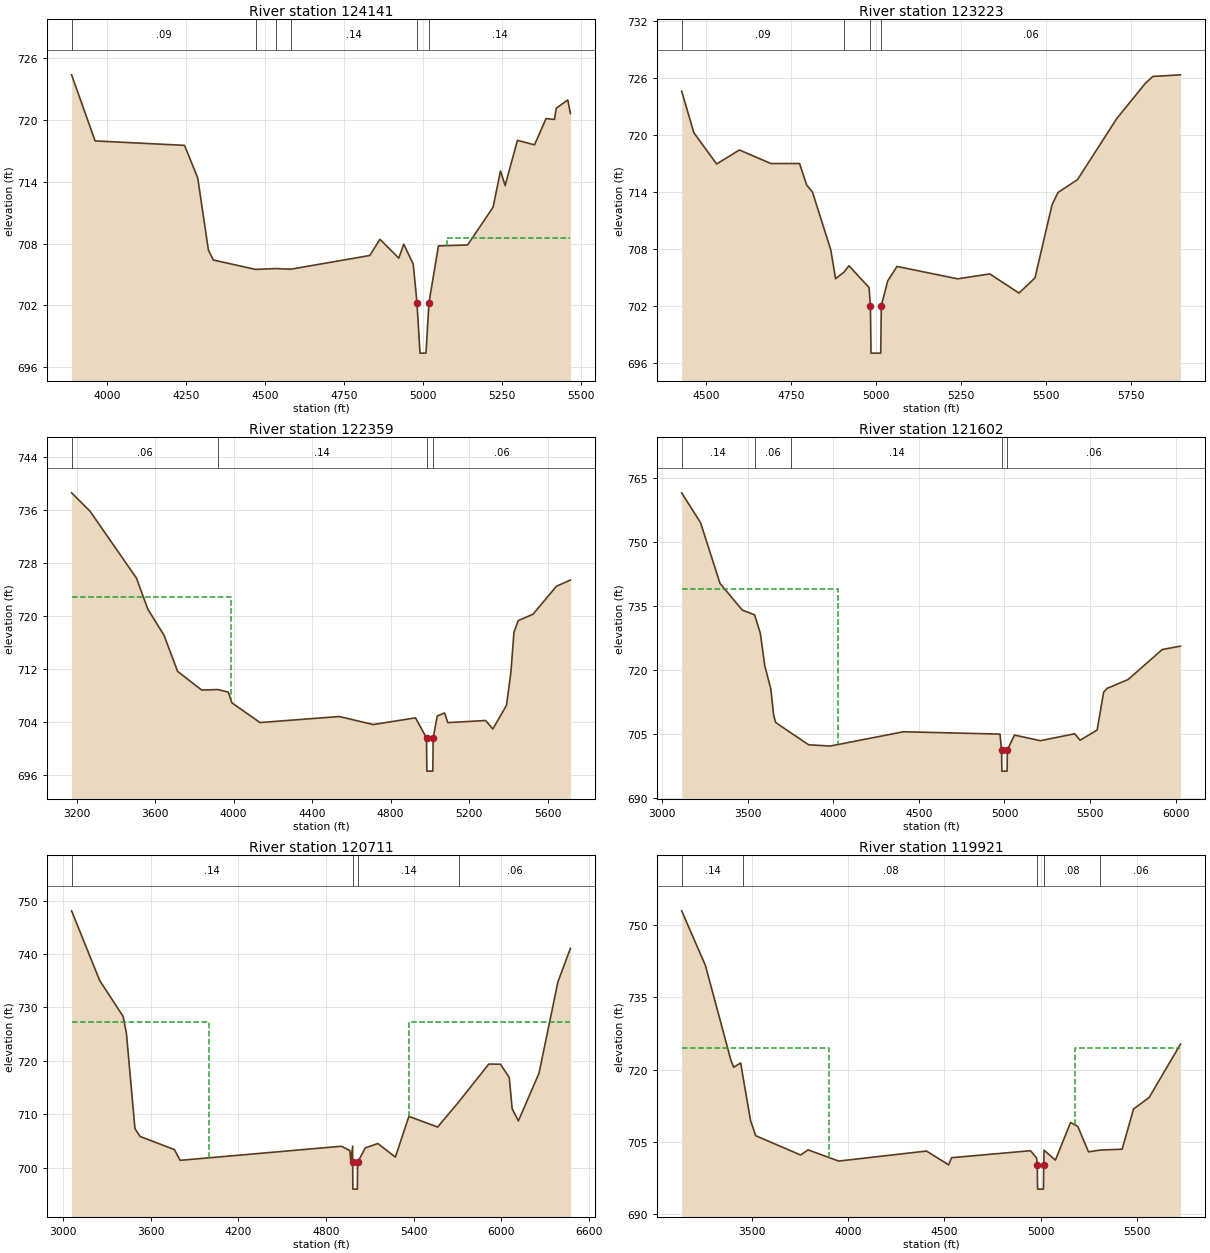
Type RM Length L Ch R = 1,124141,918,918,918
BEGIN DESCRIPTION:
Murchison Rd (DC) ds
END DESCRIPTION:
XS GIS Cut Line= 6
      1529333.96       825298.53      1529407.12       824996.47
      1529196.28       824822.63      1528807.85       824800.11
      1528622.08       824541.15      1528354.71       824470.79
#Sta/Elev= 30
  3888.0  724.36  3962.4  717.95  4245.3  717.52  4287.1  714.37  4320.9  707.37
  4336.4  706.40  4470.2  705.49  4533.6  705.57  4581.6  705.51  4831.7  706.84
  4863.9  708.41  4923.5  706.58  4939.1  707.94  4969.2  706.00  4981.0  702.27
  4990.5  697.37  5009.5  697.37  5019.0  702.27  5048.9  707.77  5141.2  707.86
  5221.8  711.52  5245.4  715.04  5260.0  713.62  5299.0  718.01  5353.0  717.57
  5389.5  720.12  5416.2  720.03  5421.7  721.12  5458.3  721.92  5466.6  720.61
#Mann=6,-1,0
  3888.0    0.09       0  4470.2    0.14       0  4533.6    0.09       0
  4581.6    0.14       0  4981.0   0.045       0  5019.0    0.14       0
#XS Ineff=2,0
    0.00 4923.50  706.15 5076.50    0.00  708.52
Permanent Ineff=
       F       F
Bank Sta=4981,5019
XS Rating Curve= 0
Exp/Cntr=0.5,0.3

Type RM Length L Ch R = 1,123223,864,864,864
BEGIN DESCRIPTION:
Dutchman Creek 139.0
END DESCRIPTION:
XS GIS Cut Line= 5
      1529347.54       825304.84      1529420.71       824981.84
      1529459.63       824657.59      1529280.21       824047.55
      1529150.17       823931.26
#Sta/Elev= 30
  4428.4  724.64  4464.3  720.25  4531.4  716.95  4598.3  718.43  4691.0  717.00
  4775.3  717.00  4796.5  714.72  4813.3  714.00  4867.3  707.89  4881.4  704.85
  4905.9  705.53  4920.8  706.21  4979.8  703.92  4984.0  701.99  4985.7  696.99
  5014.3  696.99  5016.0  701.99  5035.0  704.62  5062.2  706.14  5240.8  704.83
  5335.4  705.35  5421.2  703.33  5468.2  704.92  5518.4  712.63  5536.0  713.94
  5593.2  715.29  5709.1  721.75  5793.5  725.48  5815.3  726.19  5896.5  726.36
#Mann=4,-1,0
  4428.4    0.09       0  4905.9    0.14       0  4984.0   0.045       0
  5016.0    0.06       0
Bank Sta=4984,5016
XS Rating Curve= 0
Exp/Cntr=0.3,0.1

Type RM Length L Ch R = 1,122359,757,757,757
BEGIN DESCRIPTION:
Dutchman Creek 138.0
END DESCRIPTION:
XS GIS Cut Line= 4
      1531026.02       825541.86      1530508.09       824613.37
      1529459.63       824164.94      1529219.64       823924.95
#Sta/Elev= 30
  3173.8  738.64  3267.9  735.86  3504.4  725.77  3562.5  721.08  3645.3  717.12
  3714.1  711.70  3836.9  708.87  3919.6  708.95  3972.7  708.56  3990.9  706.95
  4134.3  703.97  4538.2  704.88  4711.7  703.67  4927.0  704.68  4983.1  701.64
  4984.8  696.64  5015.2  696.64  5016.9  701.64  5037.8  704.96  5075.3  705.42
  5091.7  703.96  5284.4  704.28  5321.2  703.00  5390.9  706.58  5413.5  711.61
  5428.8  717.58  5450.4  719.36  5525.7  720.31  5645.8  724.55  5716.7  725.48
#Mann=4,-1,0
  3173.8    0.06       0  3919.6    0.14       0  4983.1   0.045       0
  5016.9    0.06       0
#XS Ineff=2,0
    0.00 3984.80  722.99               0
Permanent Ineff=
       F       F
Bank Sta=4983.1,5016.9
XS Rating Curve= 0
Exp/Cntr=0.3,0.1

Type RM Length L Ch R = 1,121602,891,891,891
BEGIN DESCRIPTION:
Dutchman Creek 137.0
END DESCRIPTION:
XS GIS Cut Line= 6
      1531752.33       824626.00      1531411.27       824209.15
      1530249.13       823994.41      1530047.02       823893.35
      1529554.37       823767.03      1529105.93       823861.77
#Sta/Elev= 30
  3114.6  761.43  3225.0  754.45  3338.6  740.25  3468.7  734.00  3540.7  732.89
  3574.0  728.57  3600.0  721.00  3635.5  715.51  3651.8  709.42  3663.8  707.70
  3754.9  705.22  3856.7  702.49  3982.0  702.20  4410.4  705.54  4973.7  704.99
  4983.1  701.33  4984.8  696.33  5015.2  696.33  5016.9  701.33  5058.6  704.76
  5209.9  703.45  5410.1  705.07  5441.7  703.57  5532.3  705.72  5541.5  705.98
  5578.9  714.77  5598.2  715.67  5722.1  717.76  5921.3  724.77  6027.9  725.57
#Mann=5,-1,0
  3114.6    0.14       0  3540.7    0.06       0  3754.9    0.14       0
  4983.1   0.045       0  5016.9    0.06       0
#XS Ineff=2,0
    0.00 4030.60  739.00               0
Permanent Ineff=
       F       F
Bank Sta=4983.1,5016.9
XS Rating Curve= 0
Exp/Cntr=0.3,0.1

Type RM Length L Ch R = 1,120711,790,790,790
BEGIN DESCRIPTION:
Dutchman Creek 136.0
END DESCRIPTION:
XS GIS Cut Line= 6
      1532030.22       823722.78      1531853.39       823369.12
      1530419.66       823337.54      1530135.44       823318.60
      1529889.12       823242.80      1529244.89       822421.72
#Sta/Elev= 30
  3058.6  748.07  3250.9  735.02  3411.6  728.29  3434.2  725.07  3492.4  707.29
  3527.7  705.82  3762.2  703.37  3801.9  701.35  4905.8  703.99  4964.0  703.18
  4970.8  701.18  4983.0  704.00  4983.1  700.96  4984.8  695.96  5015.2  695.96
  5016.9  700.96  5069.2  703.67  5155.8  704.50  5275.6  701.96  5368.2  709.58
  5565.1  707.58  5712.5  712.39  5915.4  719.38  5995.5  719.35  6055.4  716.86
  6075.3  711.02  6118.0  708.74  6259.3  717.66  6388.3  734.73  6474.3  741.05
#Mann=4,-1,0
  3058.6    0.14       0  4983.1   0.045       0  5016.9    0.14       0
  5712.5    0.06       0
#XS Ineff=2,0
    0.00 4000.00  727.33 5365.80    0.00  727.33
Permanent Ineff=
       F       F
Bank Sta=4983.1,5016.9
XS Rating Curve= 0
Exp/Cntr=0.3,0.1

Type RM Length L Ch R = 1,119921,1483,1483,1483
BEGIN DESCRIPTION:
Dutchman Creek 135.0
END DESCRIPTION:
XS GIS Cut Line= 5
      1531992.36       822964.91      1531670.23       822775.42
      1530659.67       822788.05      1529977.55       822598.57
      1529674.35       822200.63
#Sta/Elev= 30
  3134.8  752.91  3258.2  741.59  3390.7  721.94  3405.2  720.47  3441.7  721.36
  3456.1  717.90  3493.0  709.39  3519.8  706.27  3752.9  702.27  3791.9  703.33
  3951.1  701.01  4407.4  703.09  4522.3  700.23  4537.8  701.71  4948.2  703.16
  4979.4  701.65  4983.1  700.19  4984.8  695.19  5015.2  695.19  5016.9  700.19
  5018.4  703.27  5077.3  701.21  5156.2  709.01  5193.9  708.19  5249.4  702.92
  5311.6  703.30  5424.1  703.47  5483.6  711.81  5564.9  714.21  5727.4  725.26
#Mann=5,-1,0
  3134.8    0.14       0  3456.1    0.08       0  4983.1   0.045       0
  5016.9    0.08       0  5311.6    0.06       0
#XS Ineff=2,0
    0.00 3901.80  724.47 5179.10    0.00  724.47
Permanent Ineff=
       F       F
Bank Sta=4983.1,5016.9
XS Rating Curve= 0
Exp/Cntr=0.3,0.1

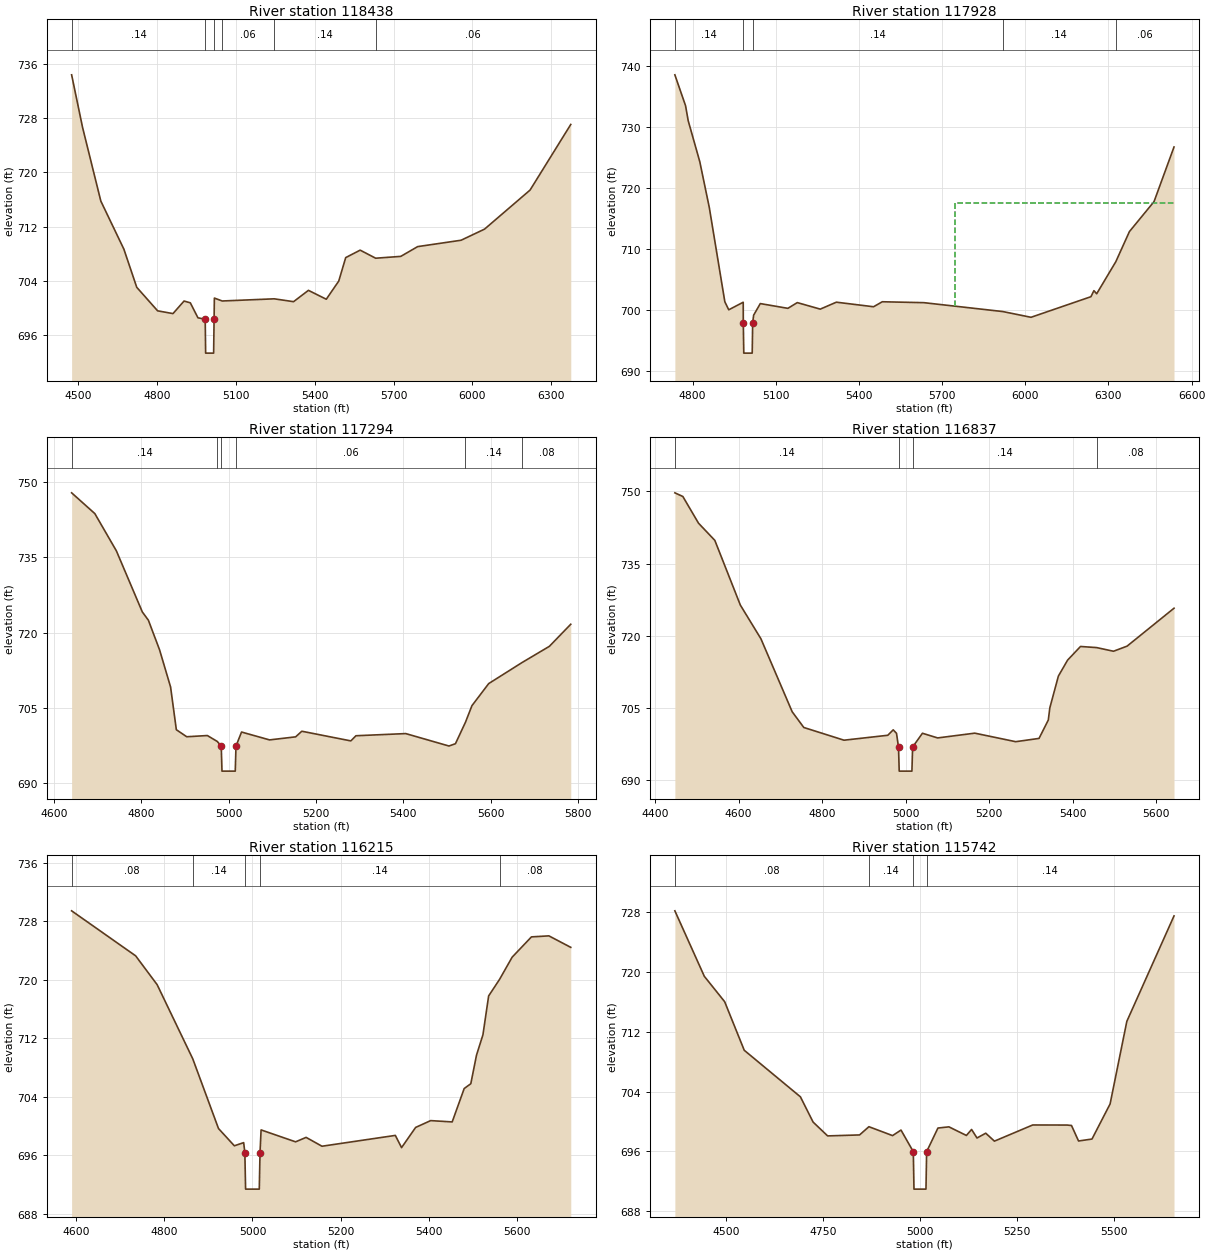
Type RM Length L Ch R = 1,118438,510,510,510
BEGIN DESCRIPTION:
Dutchman Creek 134.0
END DESCRIPTION:
XS GIS Cut Line= 4
      1531613.37       821966.98      1531190.21       822143.82
      1530665.82       822132.41      1529750.15       822099.61
#Sta/Elev= 30
  4474.8  734.39  4516.4  726.64  4585.9  715.77  4673.6  708.68  4722.6  703.05
  4802.0  699.58  4860.5  699.17  4902.5  701.02  4926.5  700.76  4955.5  698.55
  4983.1  698.34  4984.8  693.34  5015.2  693.34  5016.9  698.34  5018.0  701.46
  5047.9  701.03  5245.8  701.35  5319.4  700.93  5375.9  702.60  5443.9  701.29
  5491.3  703.97  5517.8  707.43  5572.8  708.53  5631.8  707.34  5727.3  707.61
  5791.6  709.05  5956.8  709.99  6046.1  711.63  6219.3  717.39  6374.2  727.07
#Mann=6,-1,0
  4474.8    0.14       0  4983.1   0.045       0  5016.9    0.14       0
  5047.9    0.06       0  5245.8    0.14       0  5631.8    0.06       0
Bank Sta=4983.1,5016.9
XS Rating Curve= 0
Exp/Cntr=0.3,0.1

Type RM Length L Ch R = 1,117928,634,634,634
BEGIN DESCRIPTION:
Dutchman Creek 133.0
END DESCRIPTION:
XS GIS Cut Line= 5
      1531619.65       821897.48      1531442.85       821828.02
      1531303.90       821834.34      1530261.76       821581.70
      1529863.84       821606.97
#Sta/Elev= 30
  4736.3  738.56  4774.8  733.50  4784.4  731.03  4826.2  724.30  4860.5  716.78
  4916.5  701.32  4930.6  700.00  4982.8  701.24  4983.1  697.89  4984.8  692.89
  5015.2  692.89  5016.9  697.89  5020.4  699.12  5044.4  701.02  5143.8  700.24
  5177.8  701.18  5260.7  700.11  5318.6  701.25  5452.8  700.50  5484.3  701.32
  5634.5  701.17  5919.2  699.71  6020.7  698.77  6236.8  702.15  6247.5  703.14
  6257.5  702.63  6326.6  707.90  6375.5  712.83  6464.4  717.76  6536.4  726.72
#Mann=5,-1,0
  4736.3    0.14       0  4983.1   0.045       0  5016.9    0.14       0
  5919.2    0.14       0  6326.6    0.06       0
#XS Ineff=2,0
       0                 5747.70    0.00  717.56
Permanent Ineff=
       F       F
Bank Sta=4983.1,5016.9
XS Rating Curve= 0
Exp/Cntr=0.3,0.1

Type RM Length L Ch R = 1,117294,457,457,457
BEGIN DESCRIPTION:
Dutchman Creek 132.0
END DESCRIPTION:
XS GIS Cut Line= 4
      1531842.04       821402.33      1531559.07       821356.85
      1531018.42       821089.05      1530907.27       820861.71
#Sta/Elev= 30
  4640.5  747.87  4693.7  743.72  4743.0  736.29  4802.4  724.10  4816.3  722.45
  4841.9  716.54  4867.1  709.13  4880.3  700.60  4904.1  699.20  4951.3  699.44
  4973.9  698.27  4983.1  697.34  4984.8  692.34  5015.2  692.34  5016.9  697.34
  5029.6  700.14  5093.8  698.57  5153.5  699.18  5167.6  700.30  5279.9  698.37
  5291.6  699.40  5405.6  699.83  5504.6  697.35  5519.4  697.81  5542.3  702.08
  5557.2  705.40  5595.6  709.81  5672.4  714.03  5734.5  717.24  5783.5  721.65
#Mann=6,-1,0
  4640.5    0.14       0  4973.9    0.06       0  4983.1   0.045       0
  5016.9    0.06       0  5542.3    0.14       0  5672.4    0.08       0
Bank Sta=4983.1,5016.9
XS Rating Curve= 0
Exp/Cntr=0.3,0.1

Type RM Length L Ch R = 1,116837,622,622,622
BEGIN DESCRIPTION:
Dutchman Creek 131.0
END DESCRIPTION:
XS GIS Cut Line= 5
      1531973.38       821230.52      1531670.23       821013.26
      1531362.01       820982.94      1531175.06       820866.73
      1530887.06       820816.20
#Sta/Elev= 30
  4447.6  749.70  4466.7  748.94  4504.2  743.40  4543.3  739.83  4604.4  726.40
  4653.6  719.42  4728.5  704.26  4756.3  701.00  4852.6  698.36  4957.5  699.38
  4970.4  700.51  4978.3  699.79  4983.1  696.94  4984.8  691.94  5015.2  691.94
  5016.9  696.94  5040.4  699.80  5076.8  698.83  5165.7  699.82  5263.7  698.05
  5319.6  698.73  5341.8  702.55  5345.4  705.06  5365.9  711.66  5388.0  714.98
  5418.9  717.81  5457.5  717.58  5497.9  716.82  5530.4  717.88  5642.8  725.75
#Mann=4,-1,0
  4447.6    0.14       0  4983.1   0.045       0  5016.9    0.14       0
  5457.5    0.08       0
Bank Sta=4983.1,5016.9
XS Rating Curve= 0
Exp/Cntr=0.3,0.1

Type RM Length L Ch R = 1,116215,473,473,473
BEGIN DESCRIPTION:
Dutchman Creek 130.0
END DESCRIPTION:
XS GIS Cut Line= 4
      1531836.94       820462.50      1531528.75       820427.14
      1531104.32       820523.14      1530775.89       820725.25
#Sta/Elev= 30
  4590.3  729.41  4735.4  723.26  4784.1  719.32  4864.8  709.19  4923.1  699.67
  4959.0  697.31  4980.1  697.74  4982.8  696.39  4984.5  691.39  5015.5  691.39
  5017.2  696.39  5019.6  699.48  5097.8  697.85  5121.6  698.46  5157.6  697.25
  5323.8  698.73  5337.9  697.06  5369.8  699.82  5403.9  700.75  5452.6  700.57
  5479.8  705.13  5494.8  705.79  5507.7  709.69  5522.3  712.48  5535.2  717.78
  5559.9  720.04  5588.5  723.08  5632.2  725.85  5671.7  725.99  5721.3  724.42
#Mann=5,-1,0
  4590.3    0.08       0  4864.8    0.14       0  4982.8   0.045       0
  5017.2    0.14       0  5559.9    0.08       0
Bank Sta=4982.8,5017.2
XS Rating Curve= 0
Exp/Cntr=0.3,0.1

Type RM Length L Ch R = 1,115742,1319,1319,1319
BEGIN DESCRIPTION:
Dutchman Creek 129.0
END DESCRIPTION:
XS GIS Cut Line= 4
      1531897.62       820351.36      1531629.81       820134.08
      1531432.75       820058.28      1530715.29       820209.86
#Sta/Elev= 30
  4366.9  728.15  4443.0  719.40  4495.5  716.01  4546.1  709.52  4691.2  703.30
  4723.9  699.93  4761.5  698.08  4844.0  698.21  4868.1  699.31  4929.2  698.12
  4951.0  698.86  4982.8  695.97  4984.5  690.97  5015.5  690.97  5017.2  695.97
  5046.4  699.13  5074.7  699.29  5119.9  698.14  5133.3  698.94  5147.3  697.80
  5169.9  698.44  5192.3  697.38  5291.2  699.54  5379.9  699.53  5391.4  699.47
  5409.6  697.40  5444.3  697.66  5491.1  702.35  5534.3  713.38  5656.2  727.47
#Mann=4,-1,0
  4366.9    0.08       0  4868.1    0.14       0  4982.8   0.045       0
  5017.2    0.14       0
Bank Sta=4982.8,5017.2
XS Rating Curve= 0
Exp/Cntr=0.3,0.1

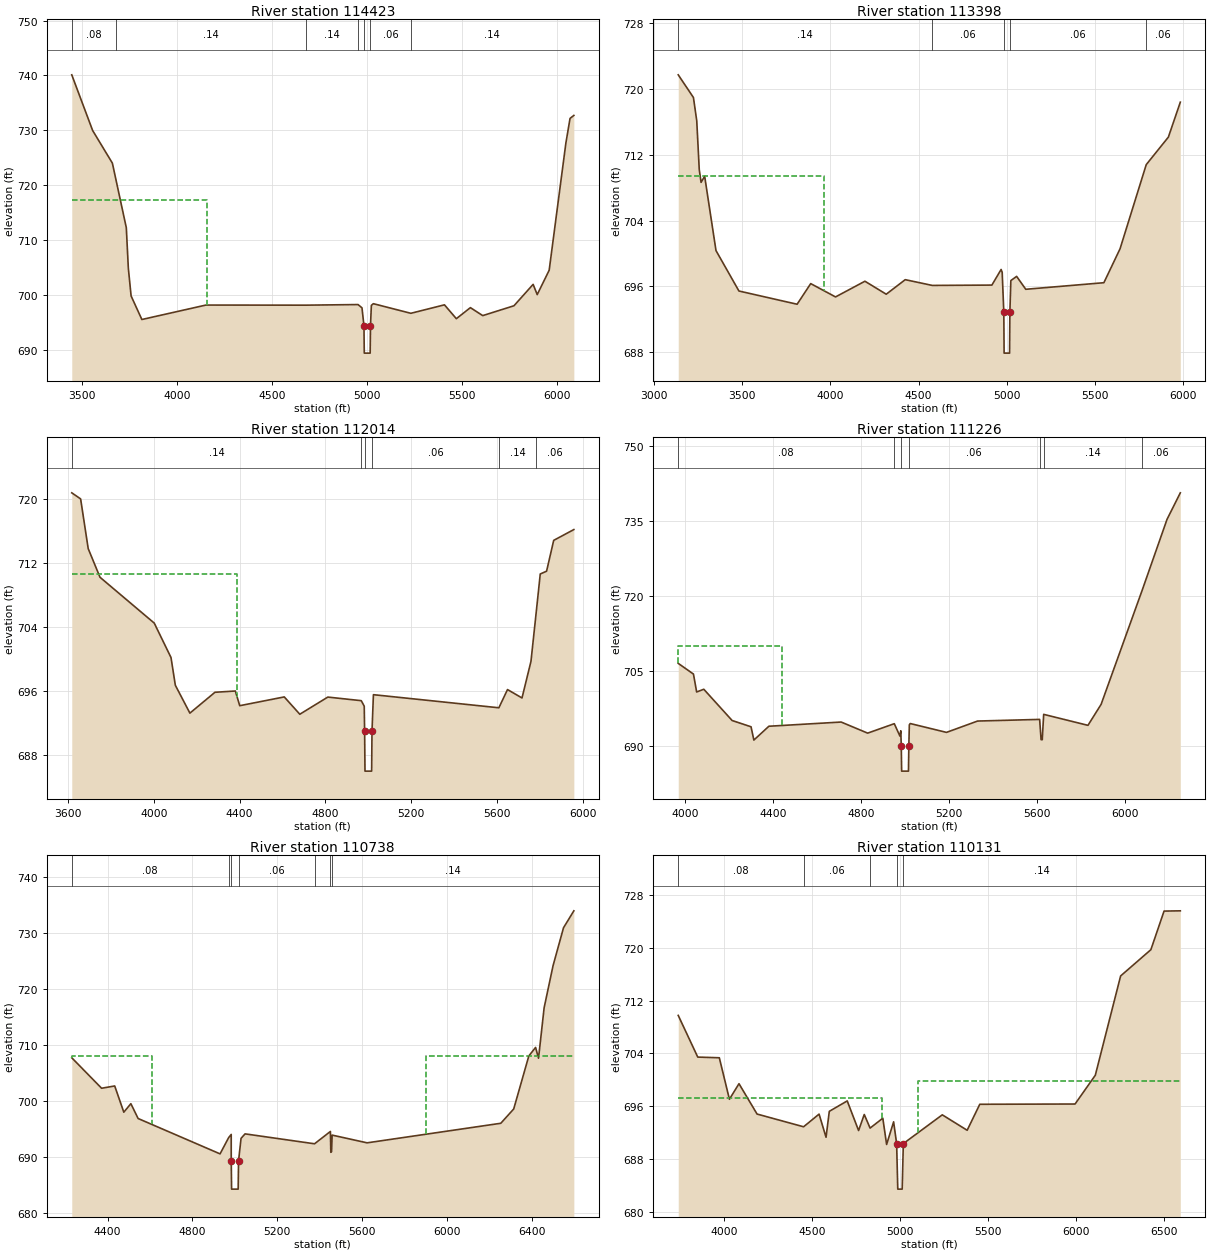
Type RM Length L Ch R = 1,114423,1025,1025,1025
BEGIN DESCRIPTION:
Dutchman Creek 128.0
END DESCRIPTION:
XS GIS Cut Line= 4
      1532706.05       819563.11      1532433.20       819406.47
      1530775.89       819391.32      1530124.05       819244.78
#Sta/Elev= 30
  3446.4  740.12  3556.1  729.99  3660.0  724.04  3680.9  720.68  3733.2  712.30
  3743.9  704.91  3758.4  699.87  3815.0  695.58  4151.9  698.21  4675.5  698.19
  4951.7  698.30  4972.5  697.70  4982.8  694.46  4984.5  689.46  5015.5  689.46
  5017.2  694.46  5021.8  698.15  5032.3  698.46  5229.4  696.71  5406.2  698.25
  5468.7  695.73  5542.5  697.74  5607.4  696.29  5771.6  698.08  5872.4  701.98
  5893.9  700.11  5956.8  704.55  6044.6  727.69  6066.5  732.19  6086.5  732.73
#Mann=7,-1,0
  3446.4    0.08       0  3680.9    0.14       0  4675.5    0.14       0
  4951.7    0.06       0  4982.8   0.045       0  5017.2    0.06       0
  5229.4    0.14       0
#XS Ineff=2,0
    0.00 4157.70  717.36               0
Permanent Ineff=
       F       F
Bank Sta=4982.8,5017.2
XS Rating Curve= 0
Exp/Cntr=0.3,0.1

Type RM Length L Ch R = 1,113398,1384,1384,1384
BEGIN DESCRIPTION:
Dutchman Creek 127.0
END DESCRIPTION:
XS GIS Cut Line= 4
      1532867.70       818491.92      1531771.29       818643.50
      1530528.30       818461.60      1530058.41       818562.65
#Sta/Elev= 30
  3138.8  721.74  3224.9  718.98  3243.7  716.14  3257.9  710.20  3268.2  708.65
  3288.5  709.40  3352.7  700.35  3482.6  695.43  3812.1  693.82  3889.2  696.33
  4029.8  694.71  4196.2  696.62  4316.9  695.04  4424.5  696.81  4577.6  696.11
  4915.3  696.15  4967.5  698.05  4973.6  697.71  4982.8  692.87  4984.5  687.87
  5015.5  687.87  5017.2  692.87  5022.7  696.70  5055.4  697.21  5107.2  695.64
  5549.6  696.44  5641.2  700.57  5789.5  710.81  5914.9  714.16  5982.5  718.41
#Mann=5,-1,0
  3138.8    0.14       0  4577.6    0.06       0  4982.8   0.045       0
  5017.2    0.06       0  5789.5    0.06       0
#XS Ineff=2,0
    0.00 3965.70  709.37               0
Permanent Ineff=
       F       F
Bank Sta=4982.8,5017.2
XS Rating Curve= 0
Exp/Cntr=0.3,0.1

Type RM Length L Ch R = 1,112014,788,788,788
BEGIN DESCRIPTION:
Dutchman Creek 126.0
END DESCRIPTION:
XS GIS Cut Line= 3
      1532953.63       818188.75      1532130.03       818143.28
      1530811.25       817395.46
#Sta/Elev= 30
  3617.4  720.82  3658.7  720.06  3694.0  713.84  3749.0  710.25  4002.0  704.51
  4080.1  700.20  4100.3  696.73  4168.2  693.24  4285.0  695.85  4380.1  696.01
  4400.5  694.17  4608.2  695.27  4680.6  693.10  4811.2  695.25  4967.1  694.80
  4981.0  694.11  4982.8  690.98  4984.5  685.98  5015.5  685.98  5017.2  690.98
  5023.8  695.55  5608.7  693.91  5649.0  696.19  5716.6  695.14  5758.4  699.72
  5782.2  705.70  5801.7  710.66  5831.2  711.01  5864.4  714.87  5958.3  716.22
#Mann=6,-1,0
  3617.4    0.14       0  4967.1    0.06       0  4982.8   0.045       0
  5017.2    0.06       0  5608.7    0.14       0  5782.2    0.06       0
#XS Ineff=2,0
    0.00 4389.00  710.63               0
Permanent Ineff=
       F       F
Bank Sta=4982.8,5017.2
XS Rating Curve= 0
Exp/Cntr=0.3,0.1

Type RM Length L Ch R = 1,111226,488,488,488
BEGIN DESCRIPTION:
Dutchman Creek 125.0
END DESCRIPTION:
XS GIS Cut Line= 5
      1532679.57       817734.60      1532224.57       817657.60
      1531615.55       816838.57      1531536.43       816489.65
      1531328.53       816096.53
#Sta/Elev= 30
  3967.9  706.49  4037.2  704.35  4051.7  700.76  4084.2  701.31  4213.1  695.05
  4299.2  693.79  4312.1  691.13  4380.4  693.90  4709.2  694.74  4829.8  692.52
  4951.0  694.41  4976.7  691.93  4980.6  692.99  4982.8  689.91  4984.5  684.91
  5015.5  684.91  5017.2  689.91  5019.5  694.19  5023.7  694.44  5188.5  692.67
  5330.0  694.94  5612.4  695.27  5619.0  691.21  5624.3  691.20  5630.8  696.28
  5832.3  694.08  5892.1  698.28  6079.0  721.14  6192.0  735.33  6252.5  740.65
#Mann=7,-1,0
  3967.9    0.08       0  4951.0    0.06       0  4982.8   0.045       0
  5017.2    0.06       0  5612.4    0.05       0  5630.8    0.14       0
  6079.0    0.06       0
#XS Ineff=2,0
    0.00 4439.50  709.96               0
Permanent Ineff=
       F       F
Bank Sta=4982.8,5017.2
XS Rating Curve= 0
Exp/Cntr=0.3,0.1

Type RM Length L Ch R = 1,110738,607,607,607
BEGIN DESCRIPTION:
Dutchman Creek 124.0
END DESCRIPTION:
XS GIS Cut Line= 5
      1532718.77       817685.59      1532349.17       817343.99
      1532245.16       816805.90      1532052.36       815837.55
      1531828.34       815596.73
#Sta/Elev= 30
  4230.8  707.69  4371.5  702.25  4433.3  702.66  4476.2  697.98  4509.5  699.50
  4543.7  696.85  4930.1  690.54  4970.6  693.44  4982.7  694.01  4982.8  689.25
  4984.5  684.25  5015.5  684.25  5017.2  689.25  5029.1  693.31  5048.0  694.11
  5375.6  692.34  5450.4  694.54  5452.4  690.82  5455.9  690.94  5458.6  693.89
  5623.5  692.51  6253.9  696.00  6314.8  698.55  6386.2  708.02  6417.9  709.53
  6431.9  707.61  6458.3  716.62  6500.3  724.11  6549.7  730.89  6598.4  733.91
#Mann=7,-1,0
  4230.8    0.08       0  4970.6    0.06       0  4982.8   0.045       0
  5017.2    0.06       0  5375.6    0.14       0  5450.4    0.05       0
  5458.6    0.14       0
#XS Ineff=2,0
    0.00 4607.70  708.00 5900.00    0.00  708.00
Permanent Ineff=
       F       F
Bank Sta=4982.8,5017.2
XS Rating Curve= 0
Exp/Cntr=0.5,0.3

Type RM Length L Ch R = 1,110131,195,195,195
BEGIN DESCRIPTION:
Cana Rd (DC) us
END DESCRIPTION:
XS GIS Cut Line= 6
      1532752.37       817650.86      1532403.68       817373.74
      1532424.49       816450.11      1532291.56       816135.53
      1532279.17       815889.47      1532568.69       815079.33
#Sta/Elev= 30
  3741.9  709.75  3852.7  703.43  3975.0  703.33  4032.3  697.04  4086.6  699.40
  4189.1  694.80  4453.1  692.87  4541.0  694.79  4580.5  691.28  4599.0  695.21
  4700.7  696.79  4765.2  692.30  4797.3  694.73  4830.5  692.67  4902.6  694.17
  4924.2  690.19  4963.9  693.62  4981.0  690.32  4987.5  683.42  5012.5  683.42
  5019.0  690.32  5240.0  694.68  5381.2  692.34  5452.8  696.28  5993.4  696.32
  6108.2  700.68  6251.9  715.73  6423.5  719.71  6498.3  725.56  6590.5  725.60
#Mann=5,-1,0
  3741.9    0.08       0  4453.1    0.06       0  4830.5    0.14       0
  4981.0   0.045       0  5019.0    0.14       0
#XS Ineff=2,0
    0.00 4896.00  697.24 5104.00    0.00  699.82
Permanent Ineff=
       F       F
Bank Sta=4981,5019
XS Rating Curve= 0
Exp/Cntr=0.5,0.3

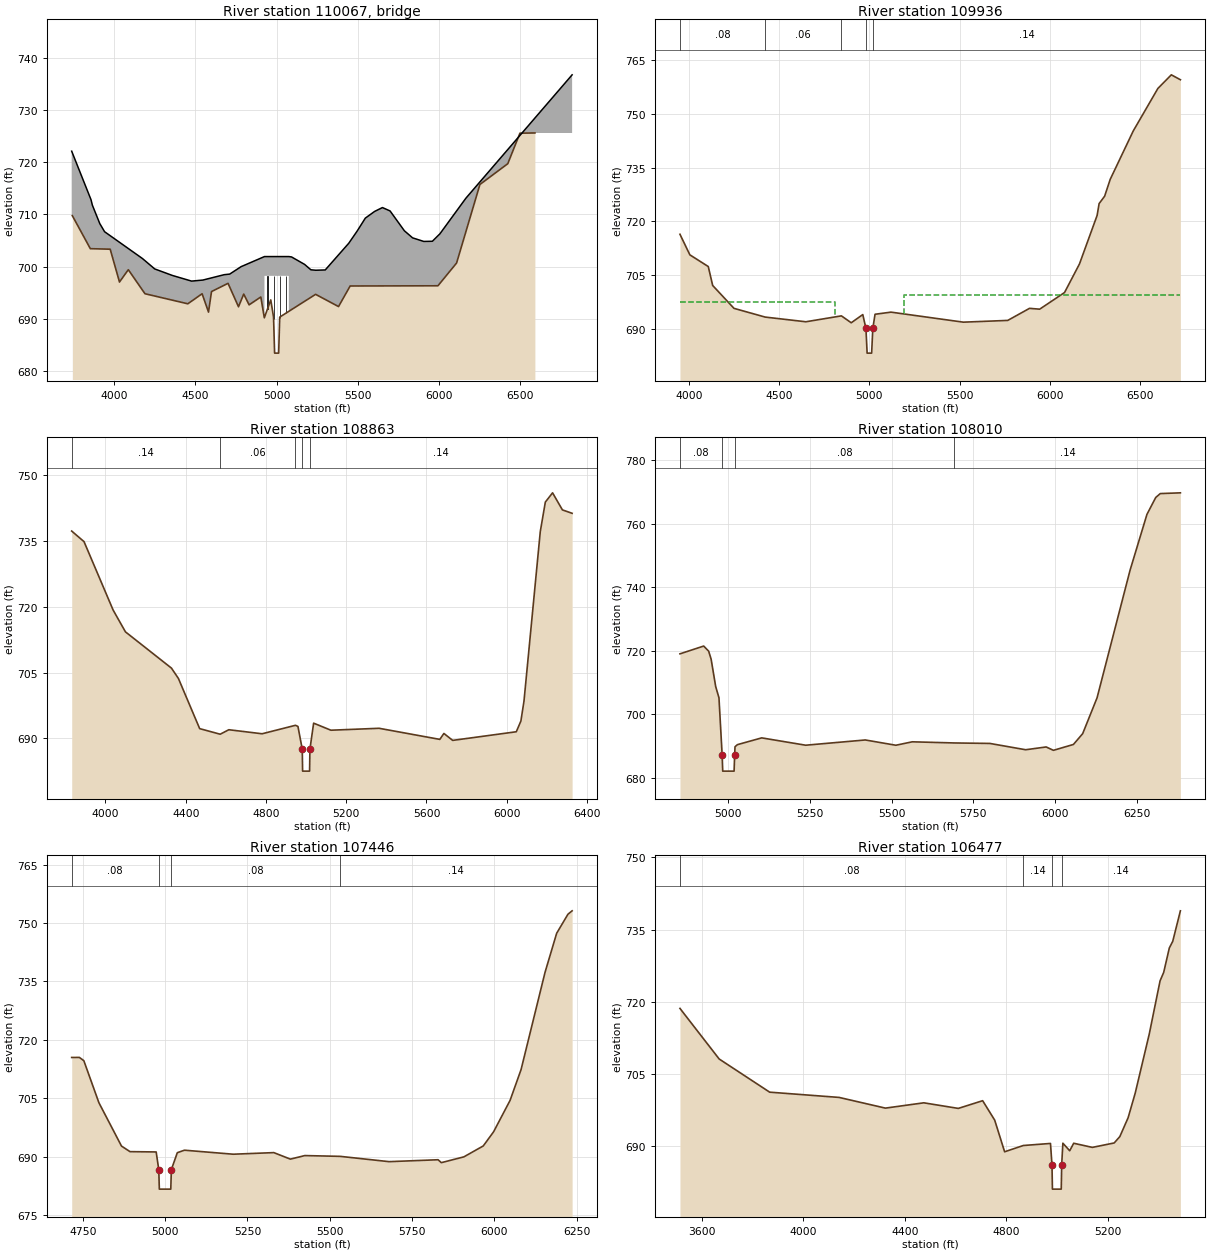
Type RM Length L Ch R =3,110067,,,
BEGIN DESCRIPTION:
Cana Rd (DC) tor
Structure ID: LDS_DC_09-1
Approximate Survey Structure
END DESCRIPTION:
Bridge Culvert--1,0,-1,-1,0
Deck Dist Width WeirC Skew NumUp NumDn MinLoCord MaxHiCord MaxSubmerge Is_Ogee
29,26,3,,35,35,,,0.95,0,1,1,,,
  3737.9  3857.0  3865.5  3911.1  3940.6  4173.4  4249.3  4357.4  4476.2  4545.8
  4677.1  4710.8  4781.3  4925.0  4925.0  5075.0  5075.0  5091.7  5171.7  5210.7
  5241.2  5299.3  5444.6  5496.7  5546.2  5603.3  5651.5  5698.6  5786.7  5837.0
  5906.0  5959.0  6005.6  6165.3  6819.6
  722.11  712.81  711.75  708.23  706.68  701.55  699.55  698.31  697.22  697.42
  698.45  698.56  699.99  701.92  701.92  701.92  701.92  701.85  700.43  699.39
  699.30  699.36  704.49  706.85  709.29  710.57  711.31  710.66  706.86  705.51
  704.82  704.85  706.29  713.10  736.74
  663.42  663.42  663.42  663.42  663.42  663.42  663.42  663.42  663.42  663.42
  663.42  663.42  663.42  663.42  698.22  698.22  663.42  663.42  663.42  663.42
  663.42  663.42  663.42  663.42  663.42  663.42  663.42  663.42  663.42  663.42
  663.42  663.42  663.42  663.42  663.42
  3737.9  3857.0  3865.5  3911.1  3940.6  4173.4  4249.3  4357.4  4476.2  4545.8
  4677.1  4710.8  4781.3  4925.0  4925.0  5075.0  5075.0  5091.7  5171.7  5210.7
  5241.2  5299.3  5444.6  5496.7  5546.2  5603.3  5651.5  5698.6  5786.7  5837.0
  5906.0  5959.0  6005.6  6165.3  6819.6
  722.11  712.81  711.75  708.23  706.68  701.55  699.55  698.31  697.22  697.42
  698.45  698.56  699.99  701.92  701.92  701.92  701.92  701.85  700.43  699.39
  699.30  699.36  704.49  706.85  709.29  710.57  711.31  710.66  706.86  705.51
  704.82  704.85  706.29  713.10  736.74
  663.42  663.42  663.42  663.42  663.42  663.42  663.42  663.42  663.42  663.42
  663.42  663.42  663.42  663.42  698.22  698.22  663.42  663.42  663.42  663.42
  663.42  663.42  663.42  663.42  663.42  663.42  663.42  663.42  663.42  663.42
  663.42  663.42  663.42  663.42  663.42
Pier Skew, UpSta & Num, DnSta & Num=,4943.8,2,4943.8,2,0,0,0,0,0
       1       1
  692.94  698.22
       1       1
  693.39  698.22
Pier Skew, UpSta & Num, DnSta & Num=,4981.3,2,4981.3,2,0,0,0,0,0
       1       1
  690.00  698.22
       1       1
  689.75  698.22
Pier Skew, UpSta & Num, DnSta & Num=,5018.8,2,5018.8,2,0,0,0,0,0
       1       1
  690.11  698.22
       1       1
  689.86  698.22
Pier Skew, UpSta & Num, DnSta & Num=,5056.3,2,5056.3,2,0,0,0,0,0
       1       1
  695.50  698.22
       1       1
  694.38  698.22
Abutment Skew #Up #Dn=,2,2
  4925.0  4926.5
  698.22  690.51
  4925.0  4926.5
  698.22  692.72
Abutment Skew #Up #Dn=,2,2
  5073.5  5075.0
  695.58  698.22
  5073.5  5075.0
  694.20  698.22
BR Coef=1,1,0,1.25,0,,,0.8,0,2,0,
WSPro=,,,, 1 ,,,, 0 ,,,, 0 ,,,,-1 ,-1 ,-1 , 0 , 0 , 0 , 0 , 0
BC Design=,,0,,0,,,,,,

Type RM Length L Ch R = 1,109936,1073,1073,1073
BEGIN DESCRIPTION:
Cana Rd (DC) ds
END DESCRIPTION:
XS GIS Cut Line= 5
      1532815.13       817503.06      1532564.22       817261.11
      1532613.50       816638.37      1532662.78       815979.79
      1532941.34       814878.34
#Sta/Elev= 30
  3951.6  716.38  4006.4  710.63  4108.3  707.36  4132.7  702.07  4250.6  695.68
  4423.4  693.24  4648.5  691.93  4845.2  693.58  4899.5  691.65  4963.5  693.94
  4981.0  690.07  4987.5  683.17  5012.5  683.17  5019.0  690.07  5031.4  694.03
  5119.7  694.62  5520.1  691.82  5765.9  692.31  5886.3  695.68  5942.6  695.45
  6080.2  700.10  6162.9  708.09  6260.5  721.64  6271.5  724.94  6302.2  727.02
  6332.9  731.71  6460.6  745.25  6596.9  757.12  6671.2  760.92  6721.4  759.55
#Mann=5,-1,0
  3951.6    0.08       0  4423.4    0.06       0  4845.2    0.14       0
  4981.0   0.045       0  5019.0    0.14       0
#XS Ineff=2,0
    0.00 4810.00  697.59 5190.00    0.00  699.49
Permanent Ineff=
       F       F
Bank Sta=4981,5019
XS Rating Curve= 0
Exp/Cntr=0.5,0.3

Type RM Length L Ch R = 1,108863,853,853,853
BEGIN DESCRIPTION:
Dutchman Creek 123.0
END DESCRIPTION:
XS GIS Cut Line= 5
      1533736.61       817517.55      1533715.61       816831.57
      1533526.60       815879.55      1533260.60       815389.53
      1533113.60       815151.54
#Sta/Elev= 30
  3831.7  737.29  3893.2  734.88  4038.4  719.26  4099.7  714.30  4329.0  706.03
  4363.7  703.67  4469.6  692.23  4571.9  690.96  4614.9  691.98  4780.8  691.06
  4946.9  692.99  4959.4  692.74  4980.9  687.54  4982.6  682.54  5017.4  682.54
  5019.1  687.54  5037.6  693.48  5123.7  691.87  5363.7  692.31  5666.5  689.78
  5686.8  691.13  5730.6  689.55  6047.7  691.52  6070.6  693.96  6086.1  698.54
  6167.2  737.16  6192.4  743.90  6228.5  746.01  6277.5  742.12  6325.9  741.34
#Mann=5,-1,0
  3831.7    0.14       0  4571.9    0.06       0  4946.9    0.14       0
  4980.9   0.045       0  5019.1    0.14       0
Bank Sta=4980.9,5019.1
XS Rating Curve= 0
Exp/Cntr=0.3,0.1

Type RM Length L Ch R = 1,108010,564,564,564
BEGIN DESCRIPTION:
Dutchman Creek 122.0
END DESCRIPTION:
XS GIS Cut Line= 3
      1534529.86       816321.39      1534337.87       816152.67
      1534151.67       814890.01
#Sta/Elev= 30
  4851.7  718.97  4924.3  721.42  4939.6  719.81  4947.1  717.30  4961.1  708.66
  4971.1  705.14  4980.9  687.04  4982.6  682.04  5017.4  682.04  5019.1  687.04
  5020.2  689.72  5027.7  690.38  5102.0  692.51  5236.5  690.20  5419.0  691.85
  5512.7  690.19  5562.8  691.27  5691.9  690.91  5800.3  690.76  5910.0  688.77
  5972.6  689.65  5995.0  688.59  6056.2  690.44  6084.5  693.84  6128.5  705.12
  6229.7  745.36  6281.2  762.88  6308.1  768.20  6322.0  769.43  6383.6  769.67
#Mann=4,-1,0
  4851.7    0.08       0  4980.9   0.045       0  5019.1    0.08       0
  5691.9    0.14       0
Bank Sta=4980.9,5019.1
XS Rating Curve= 0
Exp/Cntr=0.3,0.1

Type RM Length L Ch R = 1,107446,969,969,969
BEGIN DESCRIPTION:
Dutchman Creek 121.0
END DESCRIPTION:
XS GIS Cut Line= 5
      1534797.56       816379.62      1534803.38       816187.58
      1534774.29       815780.26      1534832.48       815367.12
      1535175.76       815000.57
#Sta/Elev= 30
  4716.4  715.50  4739.8  715.51  4753.3  714.67  4799.1  703.88  4867.7  692.76
  4893.5  691.33  4973.0  691.25  4980.9  686.71  4982.6  681.71  5017.4  681.71
  5019.1  686.71  5037.2  691.06  5058.9  691.70  5207.0  690.67  5330.3  691.08
  5380.6  689.41  5424.5  690.32  5531.7  690.12  5680.3  688.76  5829.3  689.25
  5839.0  688.50  5907.5  689.99  5966.4  692.79  5997.7  696.41  6047.8  704.47
  6081.2  712.37  6154.1  737.36  6189.4  747.38  6223.7  752.26  6236.3  753.13
#Mann=4,-1,0
  4716.4    0.08       0  4980.9   0.045       0  5019.1    0.08       0
  5531.7    0.14       0
Bank Sta=4980.9,5019.1
XS Rating Curve= 0
Exp/Cntr=0.3,0.1

Type RM Length L Ch R = 1,106477,592,592,592
BEGIN DESCRIPTION:
Dutchman Creek 120.0
END DESCRIPTION:
XS GIS Cut Line= 4
      1535643.09       817372.73      1535643.09       816347.19
      1535492.27       815653.45      1535534.50       815418.19
#Sta/Elev= 30
  3513.0  718.64  3667.8  708.14  3867.0  701.26  4140.9  700.17  4323.6  697.95
  4475.1  699.05  4611.2  697.89  4707.3  699.49  4754.9  695.45  4794.0  688.89
  4867.6  690.19  4974.9  690.62  4980.9  686.14  4982.6  681.14  5017.4  681.14
  5019.1  686.14  5023.8  690.67  5050.8  689.10  5066.5  690.66  5140.2  689.80
  5226.3  690.72  5248.5  692.04  5281.2  695.95  5309.1  701.03  5364.7  713.33
  5407.3  724.36  5421.7  726.13  5443.8  731.17  5457.3  732.56  5487.5  738.89
#Mann=4,-1,0
  3513.0    0.08       0  4867.6    0.14       0  4980.9   0.045       0
  5019.1    0.14       0
Bank Sta=4980.9,5019.1
XS Rating Curve= 0
Exp/Cntr=0.3,0.1