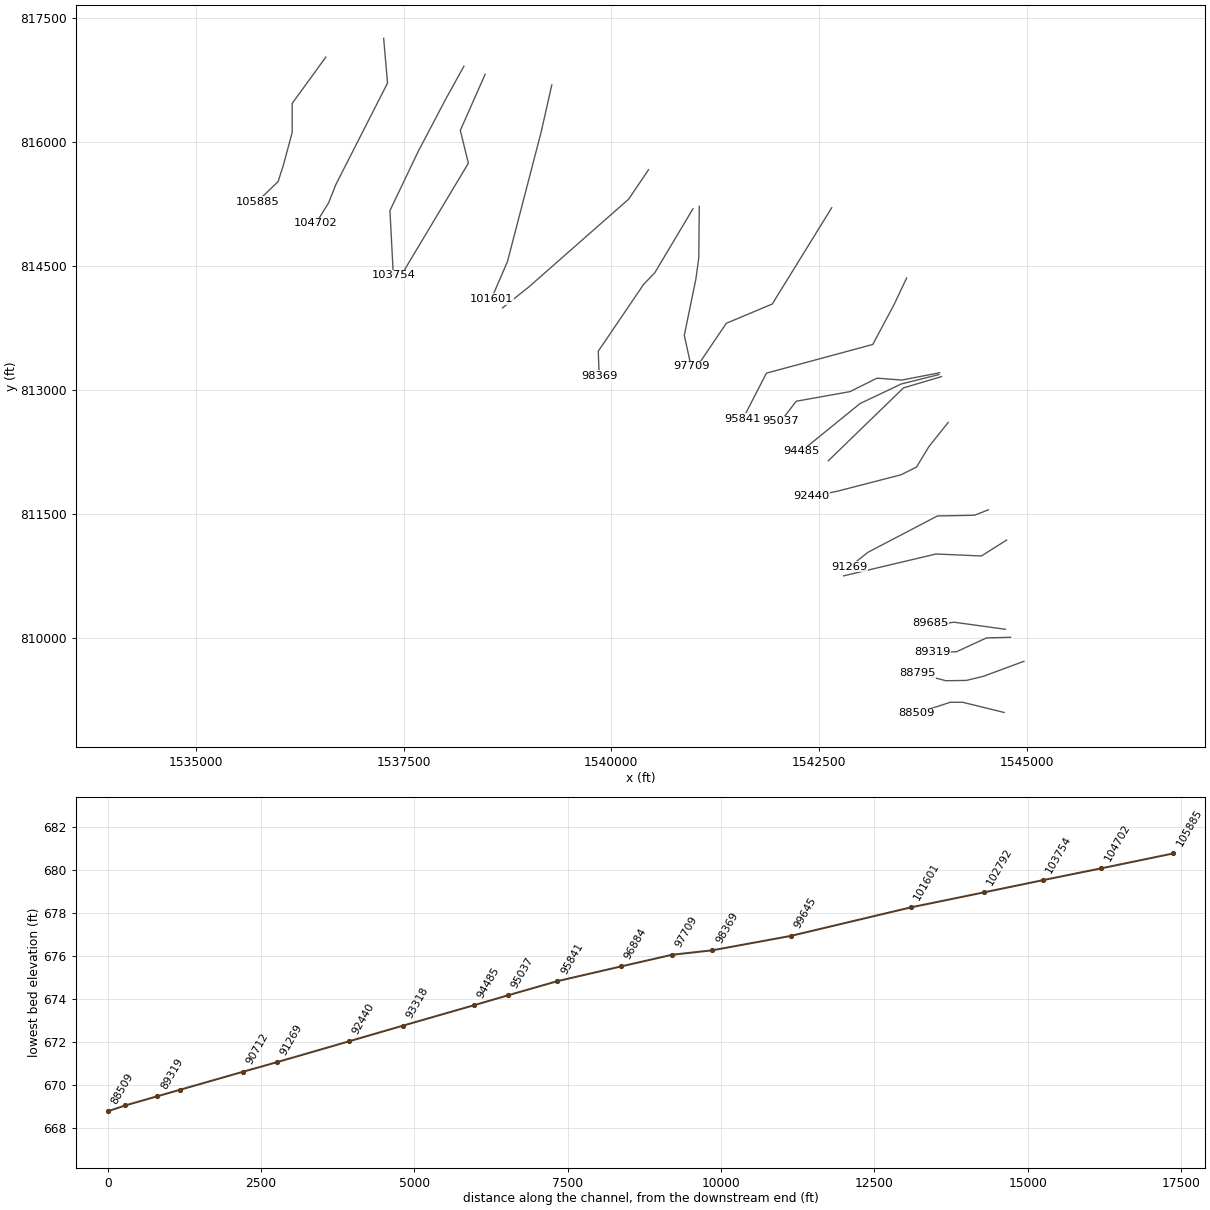
HEC-RAS study Dutchman Creek.prj: Dutchman Creek Limited Detail Study

--- Dutchman Creek.g01 (geometry) --- (continued)

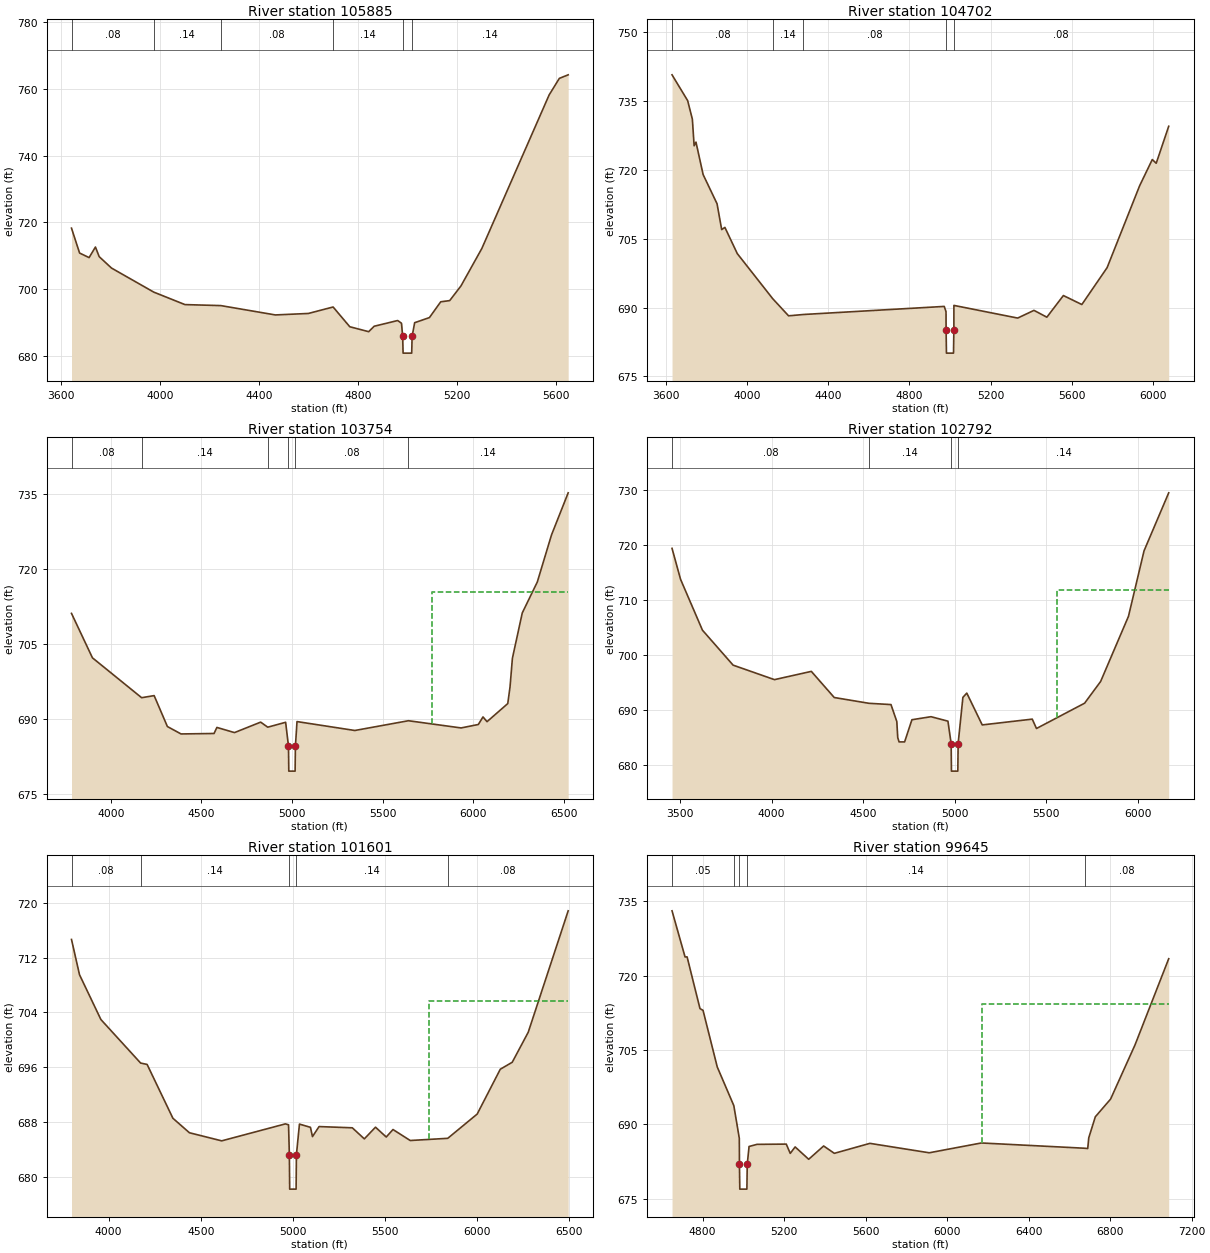
Type RM Length L Ch R = 1,105885,1183,1183,1183
BEGIN DESCRIPTION:
Dutchman Creek 119.0
END DESCRIPTION:
XS GIS Cut Line= 6
      1536562.80       817025.62      1536157.54       816465.79
      1536157.54       816114.46      1536053.30       815724.51
      1535988.60       815521.38      1535737.86       815278.73
#Sta/Elev= 30
  3641.9  718.26  3674.6  710.80  3713.0  709.43  3738.7  712.60  3753.9  709.71
  3803.5  706.30  3974.6  699.08  4100.6  695.34  4245.6  695.04  4466.1  692.24
  4599.5  692.68  4699.6  694.62  4767.1  688.70  4843.5  687.22  4865.7  688.85
  4960.6  690.56  4976.2  689.74  4980.9  685.79  4982.6  680.79  5017.4  680.79
  5019.1  685.79  5029.3  689.91  5089.1  691.45  5134.8  696.18  5171.1  696.54
  5216.6  700.94  5301.2  712.19  5573.1  758.20  5614.4  763.17  5650.1  764.23
#Mann=6,-1,0
  3641.9    0.08       0  3974.6    0.14       0  4245.6    0.08       0
  4699.6    0.14       0  4980.9   0.045       0  5019.1    0.14       0
Bank Sta=4980.9,5019.1
XS Rating Curve= 0
Exp/Cntr=0.3,0.1

Type RM Length L Ch R = 1,104702,948,948,948
BEGIN DESCRIPTION:
Dutchman Creek 118.0
END DESCRIPTION:
XS GIS Cut Line= 5
      1537258.96       817252.42      1537305.51       816711.28
      1536682.89       815483.50      1536595.60       815262.38
      1536444.32       815018.01
#Sta/Elev= 30
  3631.8  740.74  3708.7  735.12  3731.9  731.07  3740.6  725.28  3749.6  726.08
  3784.9  719.00  3853.4  712.64  3876.2  707.01  3892.0  707.49  3953.0  701.78
  4127.3  691.96  4205.4  688.22  4278.9  688.51  4971.7  690.27  4980.4  689.14
  4980.9  685.09  4982.6  680.09  5017.4  680.09  5019.1  685.09  5019.3  690.49
  5333.2  687.73  5413.5  689.41  5476.8  687.92  5558.2  692.64  5649.1  690.68
  5773.5  698.72  5933.5  716.56  5995.8  722.28  6015.2  721.47  6076.7  729.53
#Mann=5,-1,0
  3631.8    0.08       0  4127.3    0.14       0  4278.9    0.08       0
  4980.9   0.045       0  5019.1    0.08       0
Bank Sta=4980.9,5019.1
XS Rating Curve= 0
Exp/Cntr=0.3,0.1

Type RM Length L Ch R = 1,103754,962,962,962
BEGIN DESCRIPTION:
Dutchman Creek 117.0
END DESCRIPTION:
XS GIS Cut Line= 5
      1538224.89       816914.95      1538003.77       816513.44
      1537672.10       815879.18      1537334.60       815169.28
      1537375.34       814389.50
#Sta/Elev= 30
  3783.4  711.06  3899.0  702.18  4170.5  694.21  4239.5  694.63  4312.6  688.45
  4387.8  686.97  4570.0  687.06  4585.9  688.27  4682.9  687.24  4827.3  689.33
  4866.5  688.32  4965.1  689.30  4980.9  684.54  4982.6  679.54  5017.4  679.54
  5019.1  684.54  5027.9  689.44  5347.1  687.66  5642.8  689.61  5933.5  688.17
  6028.6  688.86  6054.3  690.37  6076.6  689.42  6191.0  693.04  6203.4  696.34
  6216.6  702.09  6271.0  711.15  6354.0  717.33  6432.3  726.73  6524.4  735.15
#Mann=6,-1,0
  3783.4    0.08       0  4170.5    0.14       0  4866.5    0.08       0
  4980.9   0.045       0  5019.1    0.08       0  5642.8    0.14       0
#XS Ineff=2,0
       0                 5773.60    0.00  715.24
Permanent Ineff=
       F       F
Bank Sta=4980.9,5019.1
XS Rating Curve= 0
Exp/Cntr=0.3,0.1

Type RM Length L Ch R = 1,102792,1191,1191,1191
BEGIN DESCRIPTION:
Dutchman Creek 116.0
END DESCRIPTION:
XS GIS Cut Line= 4
      1538481.11       816818.59      1538181.88       816139.25
      1538278.93       815742.97      1537478.30       814400.49
#Sta/Elev= 30
  3456.1  719.37  3502.5  713.77  3622.3  704.53  3789.8  698.19  4015.7  695.56
  4217.1  697.06  4342.2  692.32  4531.9  691.27  4652.2  691.04  4684.1  687.96
  4689.2  685.05  4696.5  684.27  4726.7  684.27  4766.6  688.29  4871.1  688.84
  4963.4  688.03  4980.9  683.97  4982.6  678.97  5017.4  678.97  5019.1  683.97
  5045.1  692.35  5066.4  693.12  5150.7  687.35  5424.0  688.40  5447.1  686.70
  5710.0  691.29  5797.6  695.23  5949.7  707.05  6034.7  718.92  6169.5  729.44
#Mann=4,-1,0
  3456.1    0.08       0  4531.9    0.14       0  4980.9   0.045       0
  5019.1    0.14       0
#XS Ineff=2,0
       0                 5559.00    0.00  711.87
Permanent Ineff=
       F       F
Bank Sta=4980.9,5019.1
XS Rating Curve= 0
Exp/Cntr=0.3,0.1

Type RM Length L Ch R = 1,101601,1956,1956,1956
BEGIN DESCRIPTION:
Dutchman Creek 115.0
END DESCRIPTION:
XS GIS Cut Line= 4
      1539283.37       816689.19      1539153.98       816114.99
      1538749.61       814554.14      1538555.52       814101.26
#Sta/Elev= 30
  3799.3  714.63  3842.7  709.50  3958.7  702.97  4174.2  696.63  4209.4  696.43
  4349.3  688.59  4438.9  686.48  4613.9  685.30  4959.2  687.77  4976.4  687.64
  4980.9  683.27  4982.6  678.27  5017.4  678.27  5019.1  683.27  5035.6  687.74
  5095.3  687.27  5106.2  685.92  5142.0  687.38  5322.2  687.20  5387.5  685.59
  5448.0  687.29  5506.2  685.86  5542.9  686.95  5636.3  685.35  5839.9  685.67
  5999.4  689.20  6124.8  695.73  6189.7  696.75  6276.4  701.12  6493.0  718.80
#Mann=5,-1,0
  3799.3    0.08       0  4174.2    0.14       0  4980.9   0.045       0
  5019.1    0.14       0  5839.9    0.08       0
#XS Ineff=2,0
       0                 5737.80    0.00  705.68
Permanent Ineff=
       F       F
Bank Sta=4980.9,5019.1
XS Rating Curve= 0
Exp/Cntr=0.3,0.1

Type RM Length L Ch R = 1,99645,1276,1276,1276
BEGIN DESCRIPTION:
Dutchman Creek 114.0
END DESCRIPTION:
XS GIS Cut Line= 4
      1540447.70       815663.88      1540209.13       815308.93
      1539010.44       814249.89      1538690.42       813993.88
#Sta/Elev= 30
  4650.1  733.07  4714.0  723.77  4724.0  723.78  4787.3  713.35  4802.2  713.00
  4871.9  701.59  4953.3  693.78  4980.2  687.19  4980.9  681.94  4982.6  676.94
  5017.4  676.94  5019.1  681.94  5028.1  685.54  5066.9  685.97  5210.6  686.02
  5230.1  684.15  5254.1  685.45  5320.7  682.96  5394.0  685.64  5446.5  684.16
  5621.0  686.17  5912.1  684.27  6167.7  686.25  6677.7  685.18  6689.7  685.13
  6694.8  687.29  6727.0  691.53  6801.9  695.10  6921.9  706.04  7087.1  723.41
#Mann=5,-1,0
  4650.1    0.05       0  4953.3    0.14       0  4980.9   0.045       0
  5019.1    0.14       0  6677.7    0.08       0
#XS Ineff=2,0
       0                 6173.40    0.00  714.20
Permanent Ineff=
       F       F
Bank Sta=4980.9,5019.1
XS Rating Curve= 0
Exp/Cntr=0.3,0.1

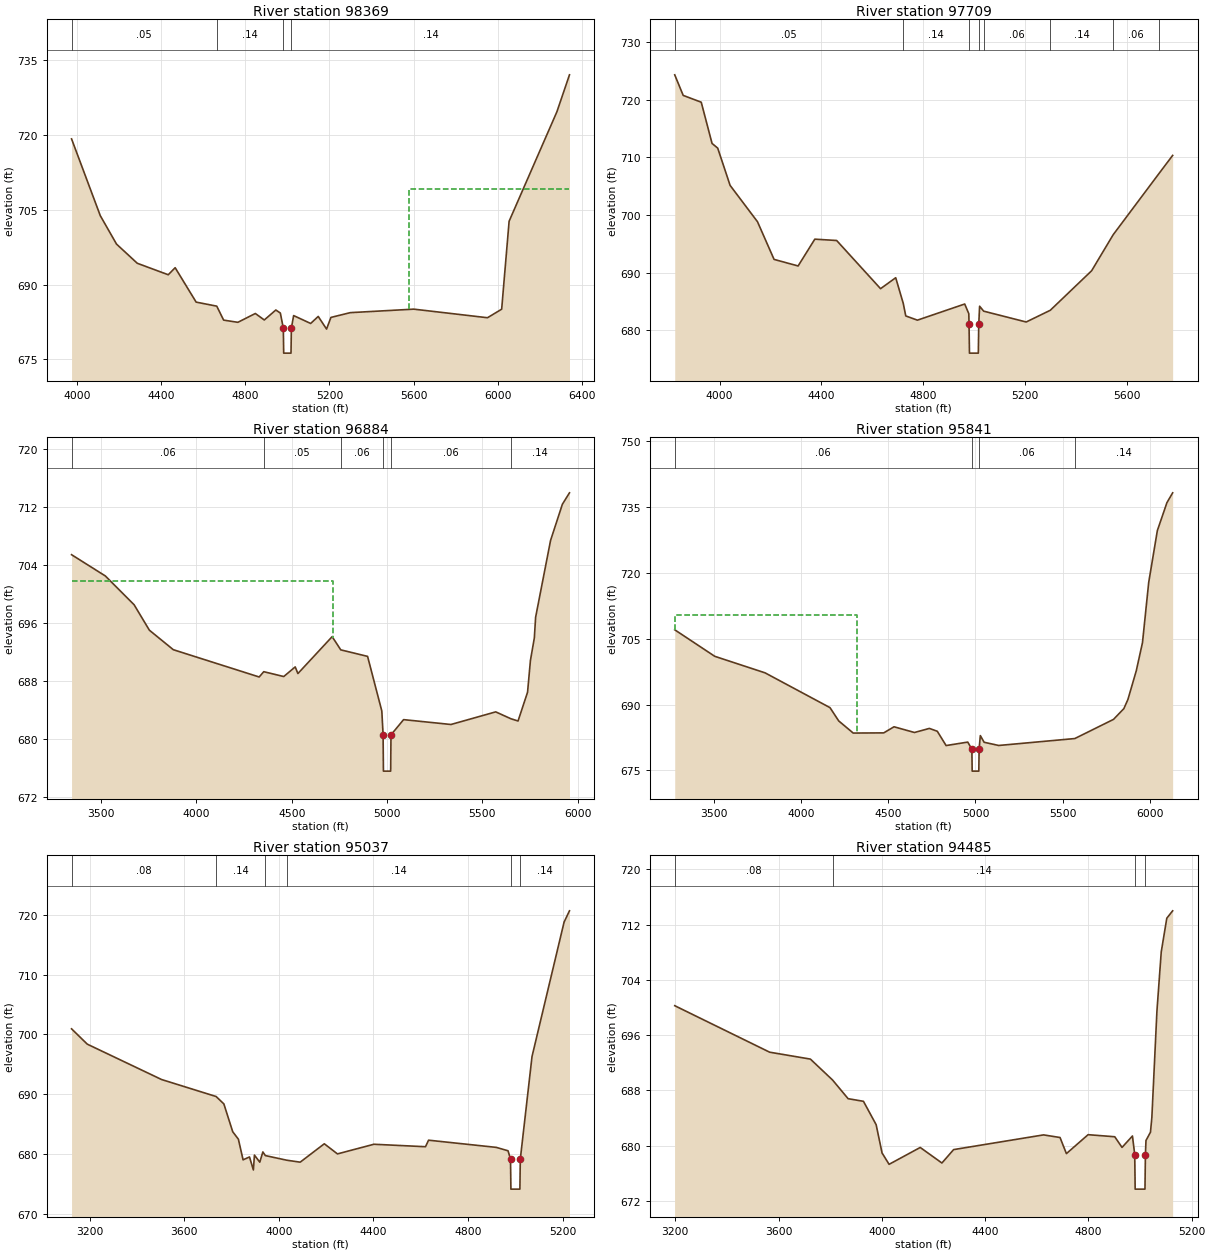
Type RM Length L Ch R = 1,98369,660,660,660
BEGIN DESCRIPTION:
Dutchman Creek 113.0
END DESCRIPTION:
XS GIS Cut Line= 5
      1540983.07       815192.59      1540523.35       814418.64
      1540389.52       814278.99      1539842.54       813470.16
      1539854.18       813173.42
#Sta/Elev= 30
  3974.2  719.24  4110.9  703.83  4187.9  698.14  4286.7  694.29  4433.8  691.99
  4466.7  693.40  4566.5  686.50  4664.5  685.69  4697.1  682.89  4764.7  682.45
  4847.9  684.22  4890.4  682.92  4945.3  684.92  4966.7  684.31  4980.9  681.27
  4982.6  676.27  5017.4  676.27  5019.1  681.27  5029.9  683.80  5110.8  682.22
  5146.8  683.63  5186.4  681.09  5207.1  683.43  5299.0  684.39  5601.0  685.09
  5951.4  683.37  6018.8  685.08  6054.2  702.72  6281.2  724.66  6341.2  732.09
#Mann=4,-1,0
  3974.2    0.05       0  4664.5    0.14       0  4980.9   0.045       0
  5019.1    0.14       0
#XS Ineff=2,0
       0                 5577.00    0.00  709.26
Permanent Ineff=
       F       F
Bank Sta=4980.9,5019.1
XS Rating Curve= 0
Exp/Cntr=0.3,0.1

Type RM Length L Ch R = 1,97709,825,825,825
BEGIN DESCRIPTION:
Dutchman Creek 112.0
END DESCRIPTION:
XS GIS Cut Line= 5
      1541058.69       815221.67      1541052.87       814599.03
      1541017.96       814343.00      1540878.31       813662.19
      1540959.78       813289.75
#Sta/Elev= 30
  3824.0  724.34  3857.3  720.77  3928.2  719.59  3970.7  712.44  3993.0  711.62
  4041.7  705.16  4149.4  698.85  4214.5  692.32  4309.0  691.18  4374.7  695.83
  4460.5  695.60  4633.1  687.24  4692.7  689.14  4722.5  684.66  4732.2  682.51
  4778.0  681.78  4963.9  684.58  4980.0  682.90  4980.9  681.06  4982.6  676.06
  5017.4  676.06  5019.1  681.06  5022.5  684.20  5038.4  683.34  5205.6  681.46
  5300.2  683.49  5462.8  690.35  5547.5  696.60  5726.1  707.13  5781.3  710.36
#Mann=8,-1,0
  3824.0    0.05       0  4722.5    0.14       0  4980.9   0.045       0
  5019.1    0.14       0  5038.4    0.06       0  5300.2    0.14       0
  5547.5    0.06       0  5726.1    0.14       0
Bank Sta=4980.9,5019.1
XS Rating Curve= 0
Exp/Cntr=0.3,0.1

Type RM Length L Ch R = 1,96884,1043,1043,1043
BEGIN DESCRIPTION:
Dutchman Creek 111.0
END DESCRIPTION:
XS GIS Cut Line= 4
      1542653.07       815204.20      1541937.34       814040.41
      1541384.55       813807.66      1541023.78       813272.33
#Sta/Elev= 30
  3345.3  705.36  3522.4  702.43  3673.3  698.46  3753.5  694.95  3879.1  692.26
  4329.3  688.50  4353.4  689.23  4458.2  688.56  4518.4  689.89  4532.4  688.97
  4712.1  694.06  4757.3  692.24  4897.9  691.34  4972.6  683.81  4979.3  680.52
  4981.0  675.52  5019.0  675.52  5020.7  680.52  5086.8  682.62  5335.3  681.95
  5570.0  683.69  5649.9  682.74  5687.1  682.43  5737.0  686.40  5752.1  690.79
  5772.6  693.89  5779.3  696.74  5857.7  707.33  5919.7  712.32  5956.9  713.89
#Mann=6,-1,0
  3345.3    0.06       0  4353.4    0.05       0  4757.3    0.06       0
  4979.3   0.045       0  5020.7    0.06       0  5649.9    0.14       0
#XS Ineff=2,0
    0.00 4717.20  701.69               0
Permanent Ineff=
       F       F
Bank Sta=4979.3,5020.7
XS Rating Curve= 0
Exp/Cntr=0.3,0.1

Type RM Length L Ch R = 1,95841,804,804,804
BEGIN DESCRIPTION:
Dutchman Creek 110.0
END DESCRIPTION:
XS GIS Cut Line= 5
      1543554.98       814354.60      1543403.70       814033.43
      1543147.67       813551.63      1541867.52       813204.82
      1541582.39       812649.69
#Sta/Elev= 30
  3277.9  707.06  3507.1  701.01  3795.2  697.24  4166.9  689.31  4216.8  686.28
  4299.9  683.51  4474.7  683.55  4533.5  684.94  4650.7  683.64  4736.0  684.57
  4781.3  683.92  4831.8  680.66  4955.6  681.45  4979.3  679.83  4981.0  674.83
  5019.0  674.83  5020.7  679.83  5027.7  682.93  5049.5  681.41  5133.0  680.68
  5568.8  682.26  5790.3  686.63  5849.5  689.08  5872.7  691.16  5920.7  697.72
  5956.2  704.14  5991.8  717.86  6041.3  729.68  6096.3  736.06  6128.9  738.29
#Mann=4,-1,0
  3277.9    0.06       0  4979.3   0.045       0  5020.7    0.06       0
  5568.8    0.14       0
#XS Ineff=2,0
    0.00 4319.80  710.49               0
Permanent Ineff=
       F       F
Bank Sta=4979.3,5020.7
XS Rating Curve= 0
Exp/Cntr=0.3,0.1

Type RM Length L Ch R = 1,95037,552,552,552
BEGIN DESCRIPTION:
Dutchman Creek 109.0
END DESCRIPTION:
XS GIS Cut Line= 6
      1543953.00       813209.47      1543496.81       813121.03
      1543198.88       813144.30      1542873.02       812981.37
      1542225.96       812865.00      1542039.74       812622.89
#Sta/Elev= 30
  3124.0  700.93  3190.5  698.37  3504.3  692.47  3735.1  689.63  3767.7  688.40
  3805.2  683.75  3829.1  682.51  3849.0  679.06  3876.1  679.54  3892.5  677.37
  3896.9  679.85  3919.6  678.67  3932.6  680.38  3943.1  679.77  4033.3  679.00
  4090.3  678.67  4192.3  681.74  4247.9  680.05  4401.8  681.66  4620.1  681.25
  4632.9  682.34  4919.2  681.14  4969.0  680.57  4979.3  679.17  4981.0  674.17
  5019.0  674.17  5020.7  679.17  5070.3  696.32  5205.8  718.75  5228.6  720.63
#Mann=6,-1,0
  3124.0    0.08       0  3735.1    0.14       0  3943.1    0.06       0
  4033.3    0.14       0  4979.3   0.045       0  5020.7    0.14       0
Bank Sta=4979.3,5020.7
XS Rating Curve= 0
Exp/Cntr=0.3,0.1

Type RM Length L Ch R = 1,94485,1167,1167,1167
BEGIN DESCRIPTION:
Dutchman Creek 108.0
END DESCRIPTION:
XS GIS Cut Line= 4
      1543942.06       813186.79      1543493.35       813074.62
      1542994.05       812837.07      1542286.48       812259.84
#Sta/Elev= 30
  3197.6  700.26  3565.2  693.53  3723.1  692.53  3809.0  689.50  3869.2  686.80
  3928.6  686.42  3977.7  683.04  4000.7  678.94  4027.9  677.30  4148.5  679.74
  4232.5  677.49  4277.8  679.43  4626.2  681.56  4690.0  681.18  4714.7  678.85
  4798.7  681.59  4902.0  681.29  4930.1  679.75  4970.5  681.40  4979.3  678.71
  4981.0  673.71  5019.0  673.71  5020.7  678.71  5022.9  680.75  5040.3  681.95
  5045.7  684.10  5065.3  699.47  5082.0  708.04  5103.5  712.92  5126.2  713.99
#Mann=4,-1,0
  3197.6    0.08       0  3809.0    0.14       0  4979.3   0.045       0
  5020.7    0.14       0
Bank Sta=4979.3,5020.7
XS Rating Curve= 0
Exp/Cntr=0.3,0.1

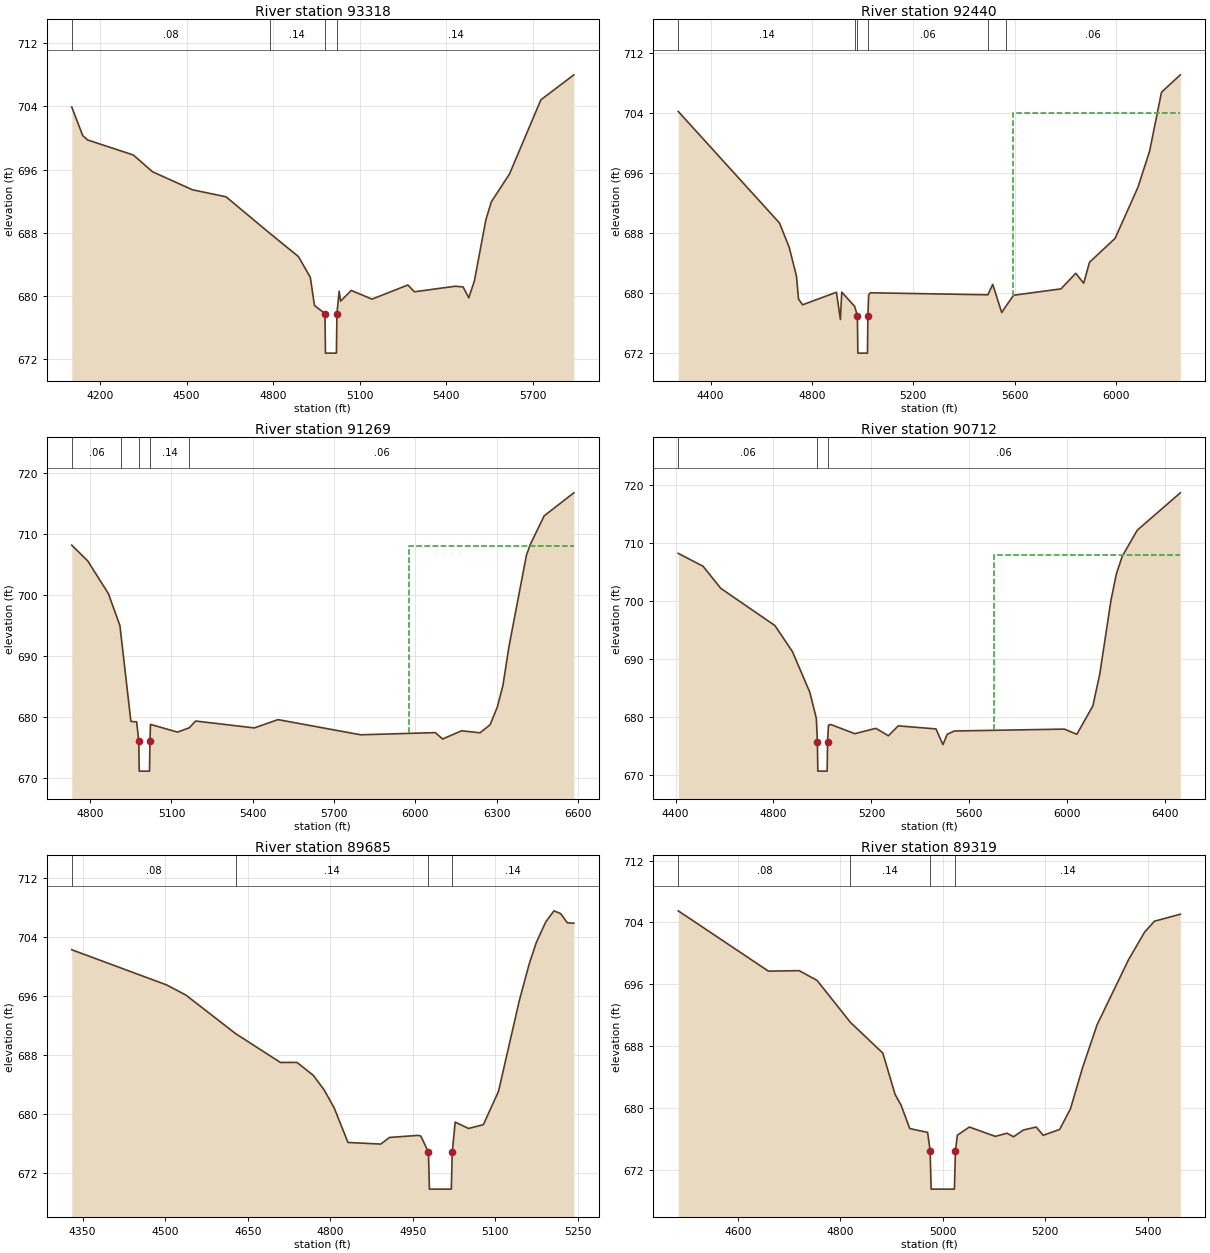
Type RM Length L Ch R = 1,93318,878,878,878
BEGIN DESCRIPTION:
Dutchman Creek 107.0
END DESCRIPTION:
XS GIS Cut Line= 3
      1543974.16       813162.77      1543517.39       813026.54
      1542611.99       812145.17
#Sta/Elev= 30
  4101.7  703.92  4139.6  700.31  4156.6  699.75  4314.9  697.85  4381.6  695.72
  4520.1  693.44  4636.5  692.55  4787.4  687.95  4887.3  684.98  4928.5  682.35
  4942.9  678.79  4979.3  677.75  4981.0  672.75  5019.0  672.75  5020.7  677.75
  5028.4  680.59  5033.5  679.33  5070.4  680.69  5142.4  679.59  5266.6  681.38
  5289.4  680.52  5430.2  681.22  5457.9  681.14  5477.8  679.76  5497.0  681.87
  5537.0  689.64  5556.0  691.92  5618.9  695.44  5727.6  704.83  5841.9  708.00
#Mann=4,-1,0
  4101.7    0.08       0  4787.4    0.14       0  4979.3   0.045       0
  5020.7    0.14       0
Bank Sta=4979.3,5020.7
XS Rating Curve= 0
Exp/Cntr=0.3,0.1

Type RM Length L Ch R = 1,92440,1171,1171,1171
BEGIN DESCRIPTION:
Dutchman Creek 106.0
END DESCRIPTION:
XS GIS Cut Line= 6
      1544055.44       812608.99      1543822.66       812315.69
      1543673.70       812068.97      1543487.50       811975.87
      1542714.75       811775.70      1542407.53       811715.19
#Sta/Elev= 30
  4271.9  704.18  4671.8  689.33  4710.0  686.09  4738.6  682.28  4746.8  679.22
  4762.7  678.45  4896.5  680.12  4912.2  676.50  4917.4  680.14  4968.2  678.25
  4979.3  677.02  4981.0  672.02  5019.0  672.02  5020.7  677.02  5023.7  679.77
  5030.6  680.05  5494.4  679.78  5513.6  681.17  5549.0  677.42  5566.0  678.28
  5595.9  679.72  5783.1  680.57  5841.1  682.64  5872.7  681.33  5895.6  684.11
  5996.6  687.29  6086.6  694.07  6132.7  698.87  6179.9  706.74  6254.1  709.05
#Mann=6,-1,0
  4271.9    0.14       0  4968.2    0.06       0  4979.3   0.045       0
  5020.7    0.06       0  5494.4    0.14       0  5566.0    0.06       0
#XS Ineff=2,0
       0                 5594.10    0.00  704.00
Permanent Ineff=
       F       F
Bank Sta=4979.3,5020.7
XS Rating Curve= 0
Exp/Cntr=0.3,0.1

Type RM Length L Ch R = 1,91269,557,557,557
BEGIN DESCRIPTION:
Dutchman Creek 105.0
END DESCRIPTION:
XS GIS Cut Line= 5
      1544539.59       811552.27      1544371.97       811487.08
      1543925.08       811477.77      1543091.81       811040.19
      1542868.37       810863.30
#Sta/Elev= 30
  4732.1  708.12  4791.2  705.53  4867.3  700.17  4909.9  694.92  4913.4  693.53
  4950.3  679.20  4971.5  679.14  4979.3  676.05  4981.0  671.05  5019.0  671.05
  5020.7  676.05  5022.6  678.72  5122.2  677.45  5165.5  678.15  5189.3  679.27
  5405.7  678.14  5493.2  679.50  5798.3  677.01  6073.8  677.37  6101.0  676.32
  6170.8  677.67  6238.9  677.34  6276.1  678.66  6302.8  681.58  6323.3  685.09
  6345.8  691.52  6410.1  706.47  6424.4  708.24  6475.5  712.93  6585.1  716.71
#Mann=5,-1,0
  4732.1    0.06       0  4913.4    0.14       0  4979.3   0.045       0
  5020.7    0.14       0  5165.5    0.06       0
#XS Ineff=2,0
       0                 5975.00    0.00  708.00
Permanent Ineff=
       F       F
Bank Sta=4979.3,5020.7
XS Rating Curve= 0
Exp/Cntr=0.3,0.1

Type RM Length L Ch R = 1,90712,1027,1027,1027
BEGIN DESCRIPTION:
Dutchman Creek 104.0
END DESCRIPTION:
XS GIS Cut Line= 4
      1544759.31       811186.81      1544454.87       810994.53
      1543910.01       811018.57      1542796.24       810754.15
#Sta/Elev= 30
  4411.0  708.22  4512.3  705.99  4584.8  702.17  4806.0  695.74  4877.2  691.26
  4948.3  684.22  4975.0  679.70  4979.3  675.60  4981.0  670.60  5019.0  670.60
  5020.7  675.60  5024.5  678.54  5034.2  678.65  5131.8  677.07  5217.9  677.99
  5269.2  676.71  5309.3  678.42  5463.5  677.89  5491.9  675.18  5509.3  676.96
  5538.5  677.53  5988.0  677.86  6038.6  676.96  6104.0  681.85  6132.4  687.38
  6178.1  700.12  6199.8  704.62  6224.2  707.73  6285.6  712.22  6461.2  718.67
#Mann=3,-1,0
  4411.0    0.06       0  4979.3   0.045       0  5020.7    0.06       0
#XS Ineff=2,0
       0                 5700.00    0.00  708.00
Permanent Ineff=
       F       F
Bank Sta=4979.3,5020.7
XS Rating Curve= 0
Exp/Cntr=0.3,0.1

Type RM Length L Ch R = 1,89685,366,366,366
BEGIN DESCRIPTION:
Dutchman Creek 103.0
END DESCRIPTION:
XS GIS Cut Line= 4
      1544743.48       810108.23      1544125.25       810193.89
      1544024.70       810179.00      1543838.53       810186.44
#Sta/Elev= 30
  4330.4  702.23  4502.7  697.46  4537.6  696.09  4628.1  690.85  4709.5  686.94
  4739.5  686.95  4769.0  685.21  4788.7  683.24  4807.1  680.78  4832.2  676.09
  4891.7  675.87  4907.6  676.77  4959.6  677.05  4964.6  676.96  4978.4  674.76
  4980.1  669.76  5019.9  669.76  5021.6  674.76  5026.9  678.85  5051.2  677.99
  5078.1  678.50  5105.6  683.01  5143.4  695.32  5161.4  700.30  5174.3  703.21
  5191.6  706.02  5206.4  707.51  5218.5  707.13  5230.8  705.88  5242.5  705.83
#Mann=4,-1,0
  4330.4    0.08       0  4628.1    0.14       0  4978.4   0.045       0
  5021.6    0.14       0
Bank Sta=4978.4,5021.6
XS Rating Curve= 0
Exp/Cntr=0.3,0.1

Type RM Length L Ch R = 1,89319,524,524,524
BEGIN DESCRIPTION:
Dutchman Creek 102.0
END DESCRIPTION:
XS GIS Cut Line= 4
      1544806.72       810011.41      1544516.28       810003.96
      1544155.04       809836.38      1543864.59       809828.93
#Sta/Elev= 30
  4484.0  705.50  4659.9  697.69  4720.0  697.75  4754.8  696.49  4819.8  691.06
  4883.1  687.07  4907.0  681.72  4918.8  680.32  4935.6  677.30  4970.4  676.81
  4975.3  674.46  4977.3  669.46  5022.7  669.46  5024.7  674.46  5028.5  676.45
  5051.8  677.50  5102.5  676.29  5125.2  676.70  5138.0  676.24  5157.0  677.11
  5182.2  677.50  5195.9  676.43  5228.0  677.19  5249.0  679.86  5272.7  685.20
  5301.0  690.75  5362.5  699.19  5393.8  702.76  5413.0  704.16  5463.3  705.06
#Mann=4,-1,0
  4484.0    0.08       0  4819.8    0.14       0  4975.3   0.045       0
  5024.7    0.14       0
Bank Sta=4975.3,5024.7
XS Rating Curve= 0
Exp/Cntr=0.3,0.1

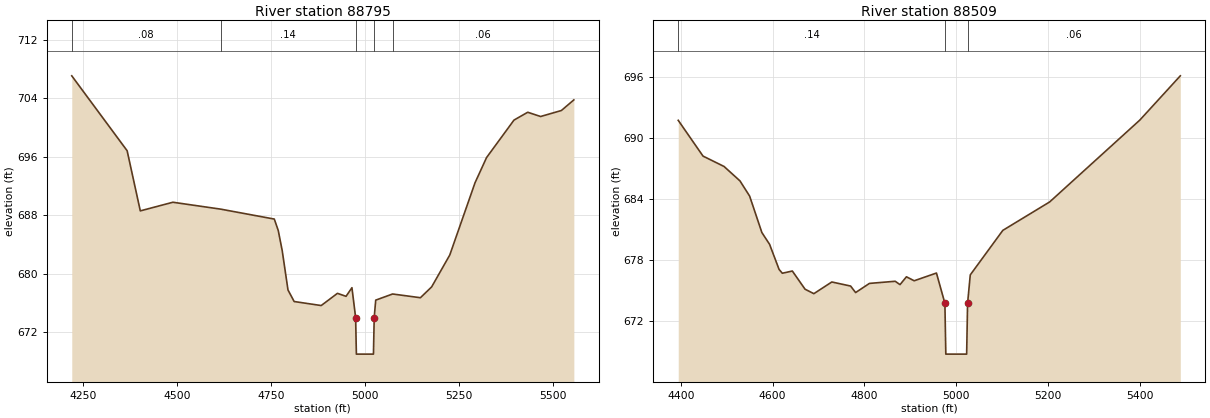
Type RM Length L Ch R = 1,88795,286,286,286
BEGIN DESCRIPTION:
Dutchman Creek 101.0
END DESCRIPTION:
XS GIS Cut Line= 5
      1544966.87       809720.93      1544475.31       809538.45
      1544274.21       809490.04      1544028.42       809486.32
      1543682.07       809575.70
#Sta/Elev= 30
  4220.7  707.07  4367.9  696.83  4402.9  688.61  4489.5  689.79  4616.3  688.85
  4759.1  687.49  4769.6  685.93  4780.1  683.19  4795.5  677.80  4811.9  676.22
  4883.8  675.67  4927.0  677.34  4949.8  676.93  4965.5  678.11  4975.3  674.03
  4977.3  669.03  5022.7  669.03  5024.7  674.03  5028.7  676.41  5073.6  677.25
  5147.5  676.74  5177.4  678.22  5225.6  682.58  5292.7  692.45  5323.4  695.90
  5396.3  701.02  5432.8  702.09  5467.1  701.51  5522.3  702.33  5555.4  703.78
#Mann=5,-1,0
  4220.7    0.08       0  4616.3    0.14       0  4975.3   0.045       0
  5024.7    0.14       0  5073.6    0.06       0
Bank Sta=4975.3,5024.7
XS Rating Curve= 0
Exp/Cntr=0.3,0.1

Type RM Length L Ch R = 1,88509,503,503,503
BEGIN DESCRIPTION:
Dutchman Creek 100.0
END DESCRIPTION:
XS GIS Cut Line= 4
      1544728.53       809102.74      1544229.52       809225.63
      1544080.56       809225.63      1543670.92       809091.57
#Sta/Elev= 30
  4394.3  691.77  4448.3  688.25  4494.1  687.23  4528.8  685.81  4549.9  684.31
  4576.5  680.73  4593.4  679.56  4614.0  677.10  4621.1  676.72  4642.9  676.94
  4670.6  675.15  4689.8  674.71  4728.9  675.86  4769.8  675.46  4780.8  674.82
  4810.9  675.72  4867.0  675.93  4877.5  675.60  4891.5  676.37  4908.4  675.98
  4956.9  676.74  4975.3  673.76  4977.3  668.76  5022.7  668.76  5024.7  673.76
  5030.6  676.56  5101.5  680.94  5203.6  683.74  5399.9  691.79  5488.2  696.15
#Mann=3,-1,0
  4394.3    0.14       0  4975.3   0.045       0  5024.7    0.06       0
Bank Sta=4975.3,5024.7
XS Rating Curve= 0
Exp/Cntr=0.3,0.1