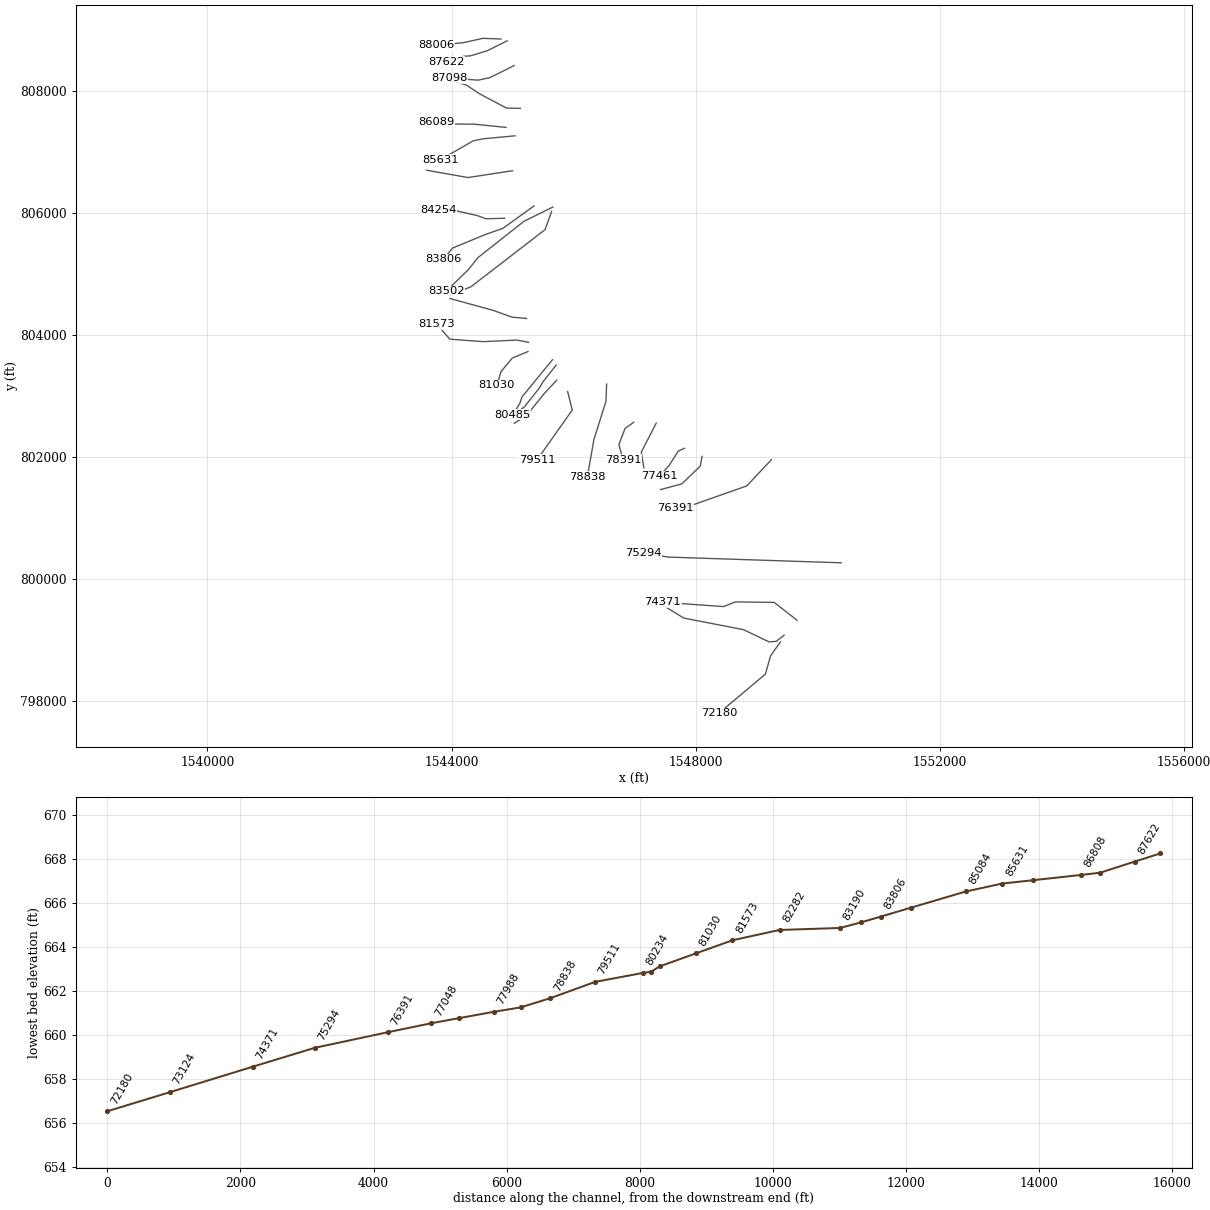
HEC-RAS study Dutchman Creek.prj: Dutchman Creek Limited Detail Study

--- Dutchman Creek.g01 (geometry) --- (continued)

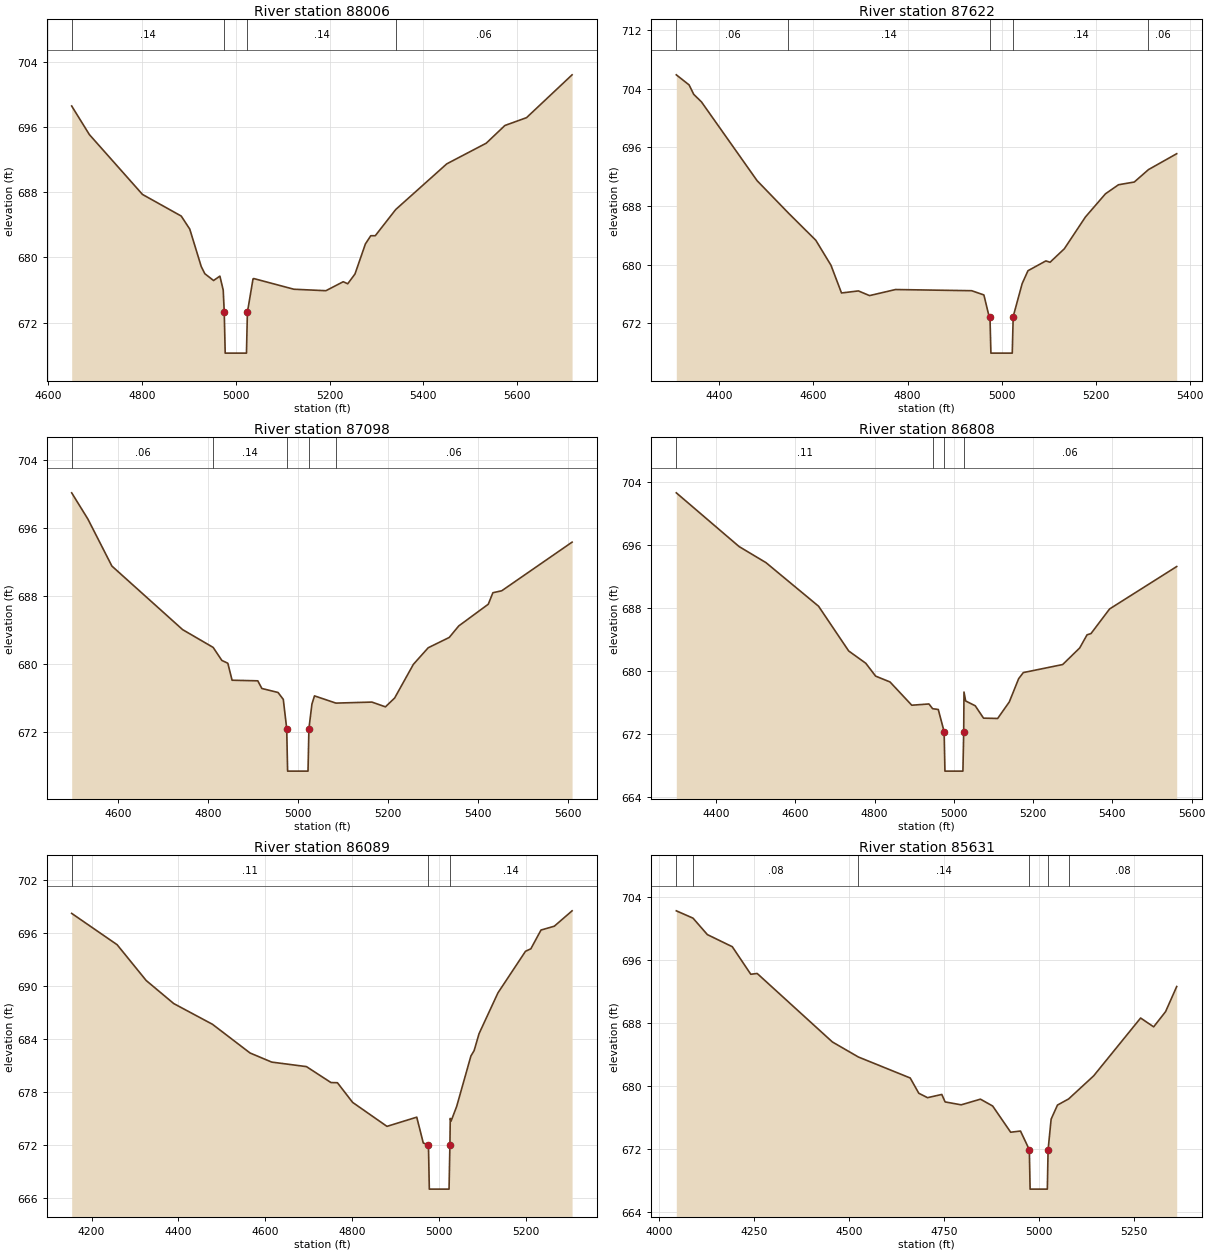
Type RM Length L Ch R = 1,88006,384,384,384
BEGIN DESCRIPTION:
Dutchman Creek 99.0
END DESCRIPTION:
XS GIS Cut Line= 4
      1544810.51       808849.50      1544512.55       808860.67
      1544196.00       808789.91      1543752.88       808745.23
#Sta/Elev= 30
  4649.7  698.56  4687.4  695.06  4800.8  687.72  4883.5  685.07  4901.7  683.47
  4926.2  678.88  4933.9  678.00  4952.5  677.17  4966.0  677.71  4973.1  675.99
  4975.3  673.27  4977.3  668.27  5022.7  668.27  5024.7  673.27  5036.7  677.37
  5038.3  677.41  5124.0  676.10  5192.2  675.92  5229.2  677.02  5238.8  676.77
  5254.3  677.97  5276.5  681.65  5288.0  682.66  5297.6  682.66  5341.2  685.87
  5450.2  691.47  5534.4  694.00  5574.2  696.17  5620.4  697.13  5717.6  702.38
#Mann=4,-1,0
  4649.7    0.14       0  4975.3   0.045       0  5024.7    0.14       0
  5341.2    0.06       0
Bank Sta=4975.3,5024.7
XS Rating Curve= 0
Exp/Cntr=0.3,0.1

Type RM Length L Ch R = 1,87622,524,524,524
BEGIN DESCRIPTION:
Dutchman Creek 98.0
END DESCRIPTION:
XS GIS Cut Line= 5
      1544911.02       808819.70      1544590.76       808659.57
      1544311.45       808573.91      1544196.00       808566.47
      1543913.02       808473.38
#Sta/Elev= 30
  4308.5  705.93  4335.7  704.55  4345.6  703.26  4362.0  702.23  4480.2  691.47
  4547.0  687.03  4605.1  683.32  4637.3  679.91  4659.7  676.12  4695.6  676.40
  4719.3  675.76  4774.5  676.59  4936.4  676.43  4962.4  675.85  4975.2  672.44
  4975.3  672.90  4977.3  667.90  5022.7  667.90  5024.7  672.90  5043.8  677.41
  5056.1  679.16  5094.1  680.50  5103.1  680.32  5133.4  682.16  5178.2  686.50
  5220.8  689.67  5248.6  690.91  5282.1  691.28  5312.3  692.98  5372.3  695.15
#Mann=5,-1,0
  4308.5    0.06       0  4547.0    0.14       0  4975.3   0.045       0
  5024.7    0.14       0  5312.3    0.06       0
Bank Sta=4975.3,5024.7
XS Rating Curve= 0
Exp/Cntr=0.3,0.1

Type RM Length L Ch R = 1,87098,290,290,290
BEGIN DESCRIPTION:
Dutchman Creek 97.0
END DESCRIPTION:
XS GIS Cut Line= 4
      1545026.48       808413.78      1544628.00       808216.40
      1544438.07       808175.44      1543965.13       808208.95
#Sta/Elev= 30
  4497.0  700.12  4533.0  697.04  4586.4  691.51  4743.8  684.03  4811.7  681.94
  4831.0  680.41  4844.3  680.08  4853.8  678.08  4911.0  678.01  4920.0  677.11
  4956.0  676.64  4967.7  675.83  4975.3  672.39  4977.3  667.39  5022.7  667.39
  5024.7  672.39  5031.4  675.27  5037.1  676.24  5084.7  675.39  5164.9  675.51
  5194.9  674.95  5215.4  675.99  5257.1  679.95  5290.1  681.90  5336.8  683.11
  5358.1  684.47  5423.7  687.02  5433.9  688.37  5453.6  688.60  5610.1  694.32
#Mann=5,-1,0
  4497.0    0.06       0  4811.7    0.14       0  4975.3   0.045       0
  5024.7    0.14       0  5084.7    0.06       0
Bank Sta=4975.3,5024.7
XS Rating Curve= 0
Exp/Cntr=0.3,0.1

Type RM Length L Ch R = 1,86808,719,719,719
BEGIN DESCRIPTION:
Dutchman Creek 96.0
END DESCRIPTION:
XS GIS Cut Line= 5
      1545127.89       807712.55      1544901.75       807717.11
      1544470.89       807944.92      1544238.53       808097.16
      1543976.29       808167.99
#Sta/Elev= 30
  4299.3  702.59  4457.9  695.77  4525.5  693.74  4658.3  688.21  4734.4  682.53
  4777.6  680.97  4802.4  679.34  4838.7  678.60  4893.6  675.65  4937.0  675.81
  4946.2  675.21  4960.5  675.11  4975.3  672.29  4977.3  667.29  5022.7  667.29
  5024.7  672.29  5025.4  677.32  5029.6  676.19  5053.8  675.58  5074.7  674.01
  5110.4  673.97  5139.8  676.07  5163.4  679.02  5175.2  679.79  5274.5  680.81
  5317.4  682.91  5336.0  684.58  5346.0  684.74  5392.9  687.86  5562.3  693.24
#Mann=4,-1,0
  4299.3    0.11       0  4946.2    0.06       0  4975.3   0.045       0
  5024.7    0.06       0
Bank Sta=4975.3,5024.7
XS Rating Curve= 0
Exp/Cntr=0.3,0.1

Type RM Length L Ch R = 1,86089,458,458,458
BEGIN DESCRIPTION:
Dutchman Creek 95.0
END DESCRIPTION:
XS GIS Cut Line= 4
      1544892.40       807400.83      1544382.21       807452.96
      1544009.80       807456.69      1543745.35       807486.48
#Sta/Elev= 30
  4154.4  698.20  4259.0  694.66  4325.8  690.62  4389.3  688.01  4478.4  685.67
  4564.8  682.43  4614.7  681.40  4694.6  680.89  4751.0  679.09  4765.9  679.07
  4800.8  676.85  4879.9  674.14  4948.4  675.18  4963.4  672.26  4975.3  672.05
  4977.3  667.05  5022.7  667.05  5024.7  672.05  5025.5  675.04  5027.4  674.74
  5040.3  676.40  5073.0  682.09  5080.4  682.70  5091.8  684.62  5135.2  689.22
  5198.6  693.92  5210.9  694.20  5234.3  696.32  5264.8  696.75  5305.8  698.49
#Mann=3,-1,0
  4154.4    0.11       0  4975.3   0.045       0  5024.7    0.14       0
Bank Sta=4975.3,5024.7
XS Rating Curve= 0
Exp/Cntr=0.3,0.1

Type RM Length L Ch R = 1,85631,547,547,547
BEGIN DESCRIPTION:
Dutchman Creek 94.0
END DESCRIPTION:
XS GIS Cut Line= 4
      1545041.42       807263.04      1544520.00       807214.62
      1544356.14       807181.10      1543812.42       806868.28
#Sta/Elev= 30
  4045.3  702.26  4089.3  701.33  4127.1  699.24  4192.8  697.70  4241.5  694.20
  4258.4  694.30  4456.4  685.60  4524.8  683.69  4661.5  681.02  4684.1  679.08
  4707.1  678.52  4744.7  678.93  4753.4  677.98  4795.7  677.61  4846.5  678.33
  4878.7  677.46  4926.1  674.13  4952.0  674.28  4975.3  671.90  4977.3  666.90
  5022.7  666.90  5024.7  671.90  5032.7  675.79  5049.4  677.58  5078.8  678.36
  5144.7  681.29  5268.4  688.64  5302.8  687.52  5334.2  689.45  5363.5  692.64
#Mann=6,-1,0
  4045.3    0.14       0  4089.3    0.08       0  4524.8    0.14       0
  4975.3   0.045       0  5024.7    0.14       0  5078.8    0.08       0
Bank Sta=4975.3,5024.7
XS Rating Curve= 0
Exp/Cntr=0.3,0.1

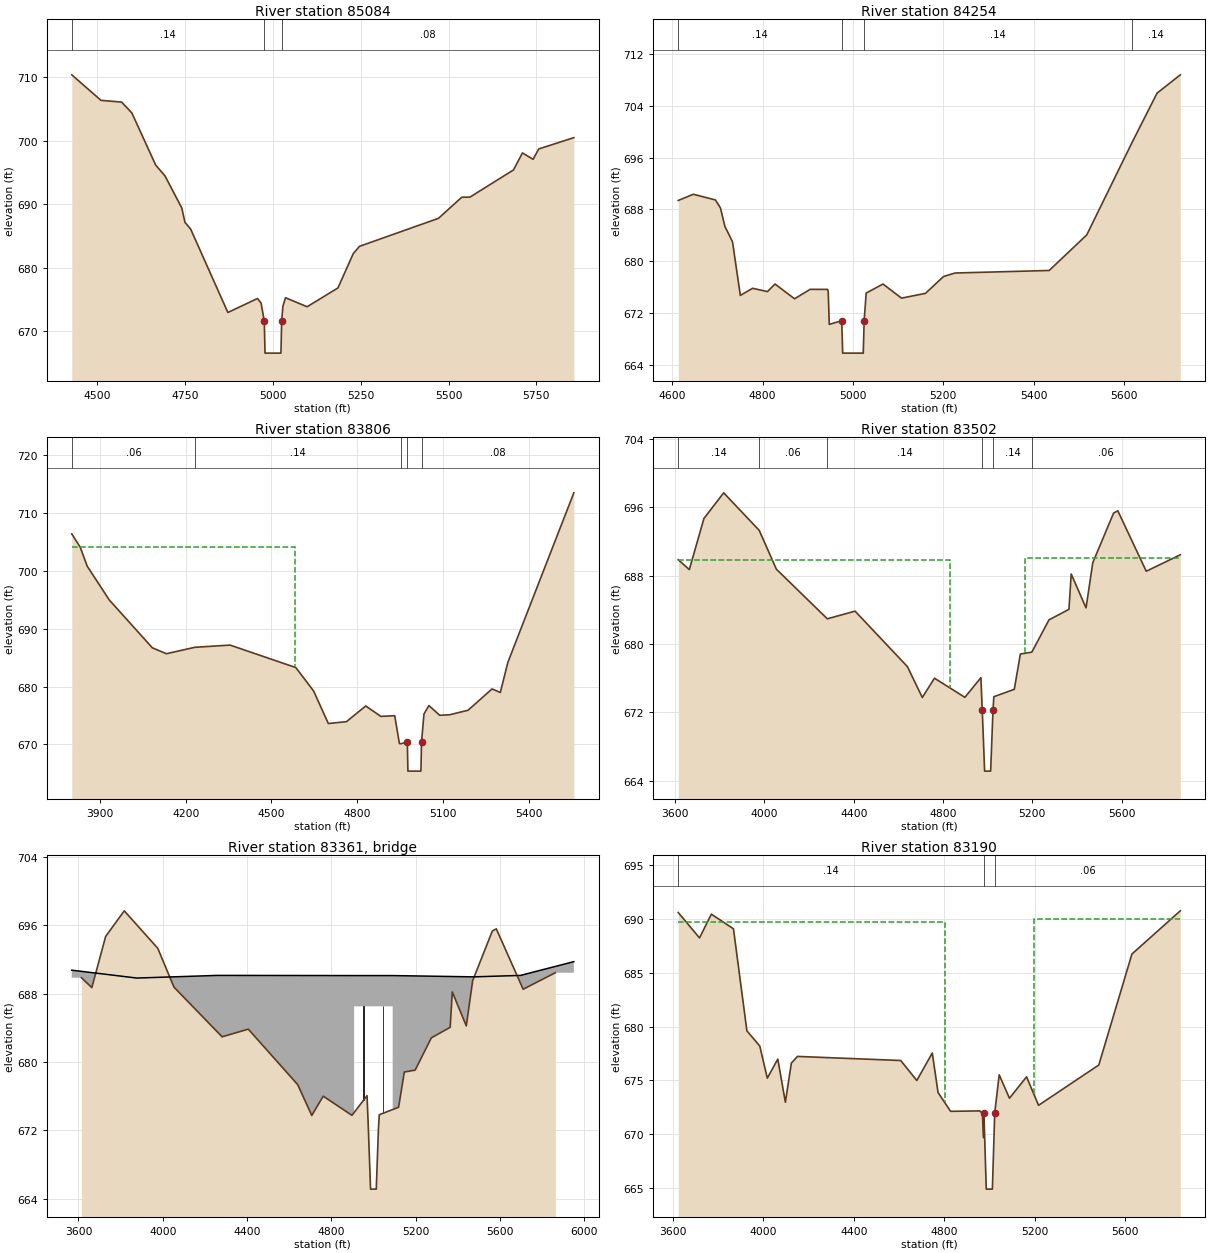
Type RM Length L Ch R = 1,85084,830,830,830
BEGIN DESCRIPTION:
Dutchman Creek 93.0
END DESCRIPTION:
XS GIS Cut Line= 3
      1544999.72       806690.94      1544270.58       806578.76
      1543589.52       806698.95
#Sta/Elev= 30
  4427.2  710.35  4510.5  706.33  4569.0  706.06  4598.2  704.36  4666.1  696.15
  4692.7  694.43  4740.4  689.39  4749.4  687.13  4765.7  686.06  4871.6  672.94
  4956.0  675.14  4966.2  674.41  4975.3  671.54  4977.3  666.54  5022.7  666.54
  5024.7  671.54  5028.2  673.91  5035.7  675.26  5097.2  673.84  5184.9  676.80
  5228.6  682.21  5246.3  683.35  5471.2  687.76  5537.4  691.08  5560.8  691.10
  5684.5  695.37  5710.3  698.06  5740.5  697.05  5756.5  698.68  5856.5  700.46
#Mann=3,-1,0
  4427.2    0.14       0  4975.3   0.045       0  5024.7    0.08       0
Bank Sta=4975.3,5024.7
XS Rating Curve= 0
Exp/Cntr=0.3,0.1

Type RM Length L Ch R = 1,84254,448,448,448
BEGIN DESCRIPTION:
Dutchman Creek 92.0
END DESCRIPTION:
XS GIS Cut Line= 5
      1544870.10       805911.19      1544564.69       805903.74
      1544419.45       805955.88      1543976.28       806056.43
      1543778.87       806048.98
#Sta/Elev= 30
  4613.1  689.37  4646.5  690.33  4695.5  689.45  4706.6  688.21  4716.4  685.37
  4733.3  682.99  4750.6  674.71  4777.8  675.81  4810.7  675.30  4827.4  676.47
  4870.7  674.19  4905.2  675.65  4943.8  675.64  4945.2  675.24  4947.6  670.24
  4975.2  670.80  4977.2  665.80  5022.8  665.80  5024.8  670.80  5029.3  675.07
  5066.5  676.47  5107.5  674.29  5160.6  675.03  5200.6  677.63  5226.1  678.17
  5434.5  678.56  5517.7  684.05  5617.8  698.29  5673.4  705.94  5724.9  708.77
#Mann=4,-1,0
  4613.1    0.14       0  4975.2   0.045       0  5024.8    0.14       0
  5617.8    0.14       0
Bank Sta=4975.2,5024.8
XS Rating Curve= 0
Exp/Cntr=0.3,0.1

Type RM Length L Ch R = 1,83806,304,304,304
BEGIN DESCRIPTION:
Dutchman Creek 91.0
END DESCRIPTION:
XS GIS Cut Line= 5
      1545352.29       806114.03      1544844.00       805747.33
      1544549.79       805643.05      1544017.25       805423.33
      1543864.56       805237.12
#Sta/Elev= 30
  3801.7  706.36  3831.4  704.05  3855.7  700.79  3932.8  694.96  4083.5  686.69
  4132.7  685.67  4232.3  686.78  4355.4  687.16  4585.2  683.28  4647.5  679.23
  4698.9  673.62  4762.4  673.94  4829.7  676.65  4882.7  674.85  4931.1  674.97
  4947.5  670.16  4952.3  670.13  4975.2  670.40  4977.2  665.40  5022.8  665.40
  5024.8  670.40  5033.4  675.27  5050.7  676.72  5088.4  675.04  5123.0  675.13
  5187.5  675.91  5271.4  679.59  5300.3  678.98  5327.1  684.23  5557.5  713.45
#Mann=5,-1,0
  3801.7    0.06       0  4232.3    0.14       0  4952.3    0.08       0
  4975.2   0.045       0  5024.8    0.08       0
#XS Ineff=2,0
    0.00 4581.80  704.05               0
Permanent Ineff=
       F       F
Bank Sta=4975.2,5024.8
XS Rating Curve= 0
Exp/Cntr=0.5,0.3

Type RM Length L Ch R = 1,83502,312,312,312
BEGIN DESCRIPTION:
I-40 (DC) us
END DESCRIPTION:
XS GIS Cut Line= 5
      1545662.33       806095.75      1545186.96       805861.67
      1544434.26       805267.44      1544272.20       805065.76
      1543912.08       804716.44
#Sta/Elev= 30
  3613.9  689.88  3663.6  688.72  3729.1  694.71  3817.5  697.71  3976.6  693.32
  4053.6  688.77  4281.9  682.96  4406.1  683.86  4640.7  677.36  4707.4  673.75
  4761.8  676.01  4898.1  673.77  4969.8  676.07  4976.0  672.23  4986.5  665.13
  5013.5  665.13  5024.0  672.23  5027.8  673.84  5119.5  674.71  5146.7  678.84
  5198.1  679.06  5275.0  682.84  5364.3  684.07  5374.4  688.21  5440.9  684.24
  5471.1  689.53  5564.5  695.35  5583.3  695.60  5710.7  688.53  5863.2  690.46
#Mann=6,-1,0
  3613.9    0.14       0  3976.6    0.06       0  4281.9    0.14       0
  4976.0   0.045       0  5024.0    0.14       0  5198.1    0.06       0
#XS Ineff=2,0
    0.00 4832.50  689.80 5167.50    0.00  690.05
Permanent Ineff=
       F       F
Bank Sta=4976,5024
XS Rating Curve= 0
Exp/Cntr=0.5,0.3

Type RM Length L Ch R =3,83361,,,
BEGIN DESCRIPTION:
I-40 (DC) tor
Structure ID: LDS_DC_08
Approximate Survey Structure
END DESCRIPTION:
Bridge Culvert--1,0,-1,-1,0
Deck Dist Width WeirC Skew NumUp NumDn MinLoCord MaxHiCord MaxSubmerge Is_Ogee
76,130,3,,11,11,,,0.95,0,1,1,,,
  3568.3  3877.1  4258.0  4908.5  4908.5  5091.5  5091.5  5479.1  5698.7  5856.9
  5951.3
  690.76  689.84  690.15  690.13  690.13  690.13  690.13  689.98  690.15  691.16
  691.76
  645.13  645.13  645.13  645.13  686.53  686.53  645.13  645.13  645.13  645.13
  645.13
  3568.3  3877.1  4258.0  4908.5  4908.5  5091.5  5091.5  5479.1  5698.7  5856.9
  5951.3
  690.76  689.84  690.15  690.13  690.13  690.13  690.13  689.98  690.15  691.16
  691.76
  645.13  645.13  645.13  645.13  686.53  686.53  645.13  645.13  645.13  645.13
  645.13
Pier Skew, UpSta & Num, DnSta & Num=,4954.3,2,4954.3,2,0,0,0,0,0
     2.8     2.8
  675.11  686.53
     2.8     2.8
  671.99  686.53
Pier Skew, UpSta & Num, DnSta & Num=,5045.8,2,5045.8,2,0,0,0,0,0
     2.8     2.8
  673.34  686.53
     2.8     2.8
  675.45  686.53
Abutment Skew #Up #Dn=,2,2
  4908.5  4932.5
  686.53  674.76
  4908.5  4932.5
  686.53  671.58
Abutment Skew #Up #Dn=,2,2
  5067.5  5091.5
  673.15  686.53
  5067.5  5091.5
  674.76  686.53
BR Coef=1,1,0,1.25,0,,,0.8,0,2,0,
WSPro=,,,, 1 ,,,, 0 ,,,, 0 ,,,,-1 ,-1 ,-1 , 0 , 0 , 0 , 0 , 0
BC Design=,,0,,0,,,,,,

Type RM Length L Ch R = 1,83190,908,908,908
BEGIN DESCRIPTION:
I-40 (DC) ds
END DESCRIPTION:
XS GIS Cut Line= 4
      1545640.73       806023.73      1545532.69       805724.81
      1544322.62       804792.05      1543976.92       804644.41
#Sta/Elev= 30
  3623.5  690.62  3717.7  688.26  3770.0  690.47  3867.9  689.11  3927.3  679.61
  3984.3  678.20  4017.6  675.21  4064.1  676.98  4097.6  672.97  4124.1  676.61
  4151.2  677.23  4608.0  676.85  4679.2  674.99  4747.6  677.55  4773.2  673.87
  4828.7  672.12  4957.5  672.16  4969.2  671.95  4974.8  669.67  4976.0  671.98
  4986.5  664.88  5013.5  664.88  5024.0  671.98  5043.7  675.52  5089.1  673.34
  5164.8  675.33  5217.8  672.68  5484.4  676.43  5631.0  686.76  5845.1  690.78
#Mann=3,-1,0
  3623.5    0.14       0  4976.0   0.045       0  5024.0    0.06       0
#XS Ineff=2,0
    0.00 4802.50  689.78 5197.50    0.00  690.03
Permanent Ineff=
       F       F
Bank Sta=4976,5024
XS Rating Curve= 0
Exp/Cntr=0.5,0.3

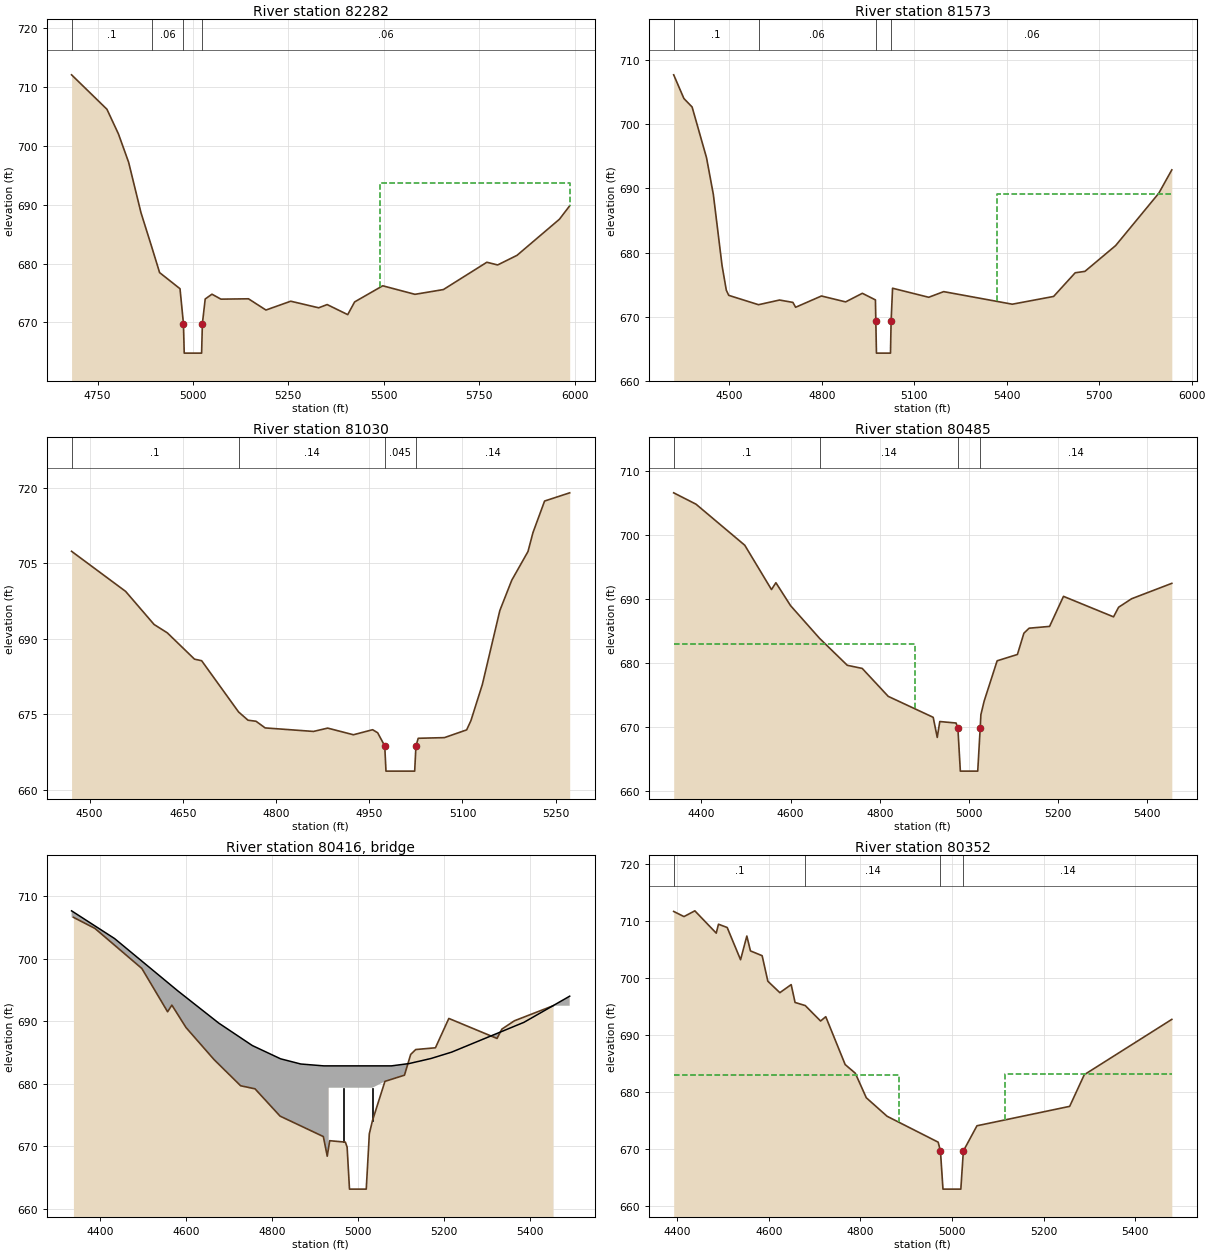
Type RM Length L Ch R = 1,82282,709,709,709
BEGIN DESCRIPTION:
Dutchman Creek 90.0
END DESCRIPTION:
XS GIS Cut Line= 4
      1545231.32       804268.86      1544989.24       804291.21
      1544680.14       804402.93      1543972.54       804596.59
#Sta/Elev= 30
  4682.0  712.07  4774.7  706.22  4804.9  702.02  4831.5  697.22  4863.9  688.65
  4891.7  682.91  4912.7  678.47  4966.2  675.73  4975.2  669.79  4977.2  664.79
  5022.8  664.79  5024.8  669.79  5032.2  673.99  5049.9  674.80  5073.5  673.96
  5145.6  674.02  5191.4  672.11  5256.3  673.61  5329.6  672.49  5351.8  673.04
  5405.7  671.33  5423.8  673.49  5497.4  676.23  5581.9  674.78  5656.5  675.59
  5770.3  680.23  5798.6  679.77  5849.3  681.40  5960.4  687.53  5987.4  689.82
#Mann=4,-1,0
  4682.0     0.1       0  4891.7    0.06       0  4975.2   0.045       0
  5024.8    0.06       0
#XS Ineff=2,0
       0                 5491.10    0.00  693.63
Permanent Ineff=
       F       F
Bank Sta=4975.2,5024.8
XS Rating Curve= 0
Exp/Cntr=0.3,0.1

Type RM Length L Ch R = 1,81573,543,543,543
BEGIN DESCRIPTION:
Dutchman Creek 89.0
END DESCRIPTION:
XS GIS Cut Line= 5
      1545261.14       803877.83      1545071.17       803915.08
      1544520.00       803889.01      1543972.56       803929.97
      1543760.29       804172.04
#Sta/Elev= 30
  4319.3  707.72  4352.5  704.02  4379.1  702.70  4425.9  694.78  4448.0  689.06
  4476.3  677.95  4490.1  674.13  4497.9  673.33  4594.6  671.87  4662.8  672.60
  4706.1  672.23  4714.9  671.47  4798.7  673.23  4877.2  672.31  4931.5  673.65
  4973.9  672.62  4975.2  669.32  4977.2  664.32  5022.8  664.32  5024.8  669.32
  5029.5  674.44  5146.8  673.03  5195.4  673.91  5418.0  671.95  5552.1  673.16
  5622.1  676.85  5653.7  677.07  5753.3  681.09  5893.4  689.26  5935.6  692.90
#Mann=4,-1,0
  4319.3     0.1       0  4594.6    0.06       0  4975.2   0.045       0
  5024.8    0.06       0
#XS Ineff=2,0
       0                 5366.90    0.00  689.13
Permanent Ineff=
       F       F
Bank Sta=4975.2,5024.8
XS Rating Curve= 0
Exp/Cntr=0.3,0.1

Type RM Length L Ch R = 1,81030,545,545,545
BEGIN DESCRIPTION:
Dutchman Creek 88.0
END DESCRIPTION:
XS GIS Cut Line= 4
      1545253.05       803726.81      1544996.68       803620.87
      1544810.48       803397.43      1544743.46       803174.02
#Sta/Elev= 30
  4471.0  707.37  4558.0  699.41  4603.8  692.84  4625.0  691.19  4668.8  685.96
  4680.3  685.65  4739.7  675.48  4754.9  673.84  4767.8  673.63  4782.5  672.31
  4860.2  671.61  4883.1  672.27  4924.5  670.95  4955.4  671.95  4963.5  671.35
  4974.9  668.73  4976.9  663.73  5023.1  663.73  5025.1  668.73  5028.8  670.25
  5070.9  670.38  5106.7  671.92  5113.5  673.73  5132.0  680.95  5160.1  695.61
  5179.2  701.61  5205.4  707.33  5213.4  711.08  5232.1  717.35  5272.5  718.98
#Mann=4,-1,0
  4471.0     0.1       0  4739.7    0.14       0  4974.9   0.045       0
  5025.1    0.14       0
Bank Sta=4974.9,5025.1
XS Rating Curve= 0
Exp/Cntr=0.5,0.3

Type RM Length L Ch R = 1,80485,133,133,133
BEGIN DESCRIPTION:
US 158 (DC) us
END DESCRIPTION:
XS GIS Cut Line= 5
      1545654.17       803592.49      1545406.51       803290.72
      1545156.75       802984.76      1545117.20       802872.37
      1545002.71       802693.34
#Sta/Elev= 30
  4337.7  706.58  4387.7  704.81  4497.1  698.40  4557.0  691.48  4566.9  692.55
  4599.9  688.96  4664.9  683.86  4727.0  679.66  4760.5  679.17  4818.8  674.81
  4919.6  671.54  4928.7  668.40  4934.4  670.88  4970.9  670.65  4975.0  669.84
  4980.5  663.14  5019.5  663.14  5025.0  669.84  5026.6  671.96  5033.9  674.07
  5063.0  680.36  5108.5  681.35  5123.0  684.67  5134.7  685.45  5180.6  685.73
  5211.8  690.42  5324.0  687.22  5335.4  688.72  5364.6  690.05  5454.7  692.45
#Mann=4,-1,0
  4337.7     0.1       0  4664.9    0.14       0  4975.0   0.045       0
  5025.0    0.14       0
#XS Ineff=2,0
    0.00 4878.50  682.94 5121.50    0.00  683.21
Permanent Ineff=
       F       F
Bank Sta=4975,5025
XS Rating Curve= 0
Exp/Cntr=0.5,0.3

Type RM Length L Ch R =3,80416,,,
BEGIN DESCRIPTION:
US 158 (DC) tor
Structure ID: LDS_DC_06
Approximate Survey Structure
END DESCRIPTION:
Bridge Culvert--1,0,-1,-1,0
Deck Dist Width WeirC Skew NumUp NumDn MinLoCord MaxHiCord MaxSubmerge Is_Ogee
53.5,31,3,,18,18,,,0.95,0,1,1,,,
  4333.4  4433.5  4580.9  4676.0  4754.2  4820.0  4867.0  4920.5  4932.0  4932.0
  5068.0  5068.0  5078.2  5119.3  5169.8  5218.5  5386.7  5493.2
  707.62  703.19  694.82  689.68  686.09  683.97  683.14  682.84  682.84  682.84
  682.84  682.84  682.84  683.21  684.01  685.04  689.80  693.98
  643.14  643.14  643.14  643.14  643.14  643.14  643.14  643.14  643.14  679.34
  679.34  643.14  643.14  643.14  643.14  643.14  643.14  643.14
  4333.4  4433.5  4580.9  4676.0  4754.2  4820.0  4867.0  4920.5  4932.0  4932.0
  5068.0  5068.0  5078.2  5119.3  5169.8  5218.5  5386.7  5493.2
  707.62  703.19  694.82  689.68  686.09  683.97  683.14  682.84  682.84  682.84
  682.84  682.84  682.84  683.21  684.01  685.04  689.80  693.98
  643.14  643.14  643.14  643.14  643.14  643.14  643.14  643.14  643.14  679.34
  679.34  643.14  643.14  643.14  643.14  643.14  643.14  643.14
Pier Skew, UpSta & Num, DnSta & Num=,4966,2,4966,2,0,0,0,0,0
       3       3
  670.69  679.34
       3       3
  671.18  679.34
Pier Skew, UpSta & Num, DnSta & Num=,5034,2,5034,2,0,0,0,0,0
       3       3
  674.09  679.34
       3       3
  671.74  679.34
Abutment Skew #Up #Dn=,2,2
  4932.0  4935.0
  679.34  670.84
  4932.0  4935.0
  679.34  672.35
Abutment Skew #Up #Dn=,2,2
  5065.0  5068.0
  680.42  679.34
  5065.0  5068.0
  674.00  679.34
BR Coef=1,1,0,1.25,0,,,0.8,0,2,0,
WSPro=,,,, 1 ,,,, 0 ,,,, 0 ,,,,-1 ,-1 ,-1 , 0 , 0 , 0 , 0 , 0
BC Design=,,0,,0,,,,,,

Type RM Length L Ch R = 1,80352,118,118,118
BEGIN DESCRIPTION:
US 158 (DC) ds
END DESCRIPTION:
XS GIS Cut Line= 5
      1545714.56       803505.11      1545500.17       803232.44
      1545439.81       803130.46      1545196.29       802822.42
      1545017.31       802678.82
#Sta/Elev= 30
  4392.6  711.67  4415.1  710.77  4438.8  711.78  4485.5  707.86  4490.4  709.43
  4509.4  708.85  4538.6  703.19  4552.3  707.35  4560.2  704.74  4585.7  703.90
  4598.2  699.41  4624.4  697.40  4649.1  698.82  4657.6  695.68  4679.8  695.14
  4713.3  692.42  4724.6  693.18  4767.0  684.77  4789.1  683.25  4813.1  678.94
  4858.5  675.69  4970.0  671.14  4975.0  669.59  4980.5  662.89  5019.5  662.89
  5025.0  669.59  5054.7  674.02  5257.1  677.43  5289.0  682.99  5480.1  692.71
#Mann=4,-1,0
  4392.6     0.1       0  4679.8    0.14       0  4975.0   0.045       0
  5025.0    0.14       0
#XS Ineff=2,0
    0.00 4883.50  682.99 5116.50    0.00  683.19
Permanent Ineff=
       F       F
Bank Sta=4975,5025
XS Rating Curve= 0
Exp/Cntr=0.5,0.3

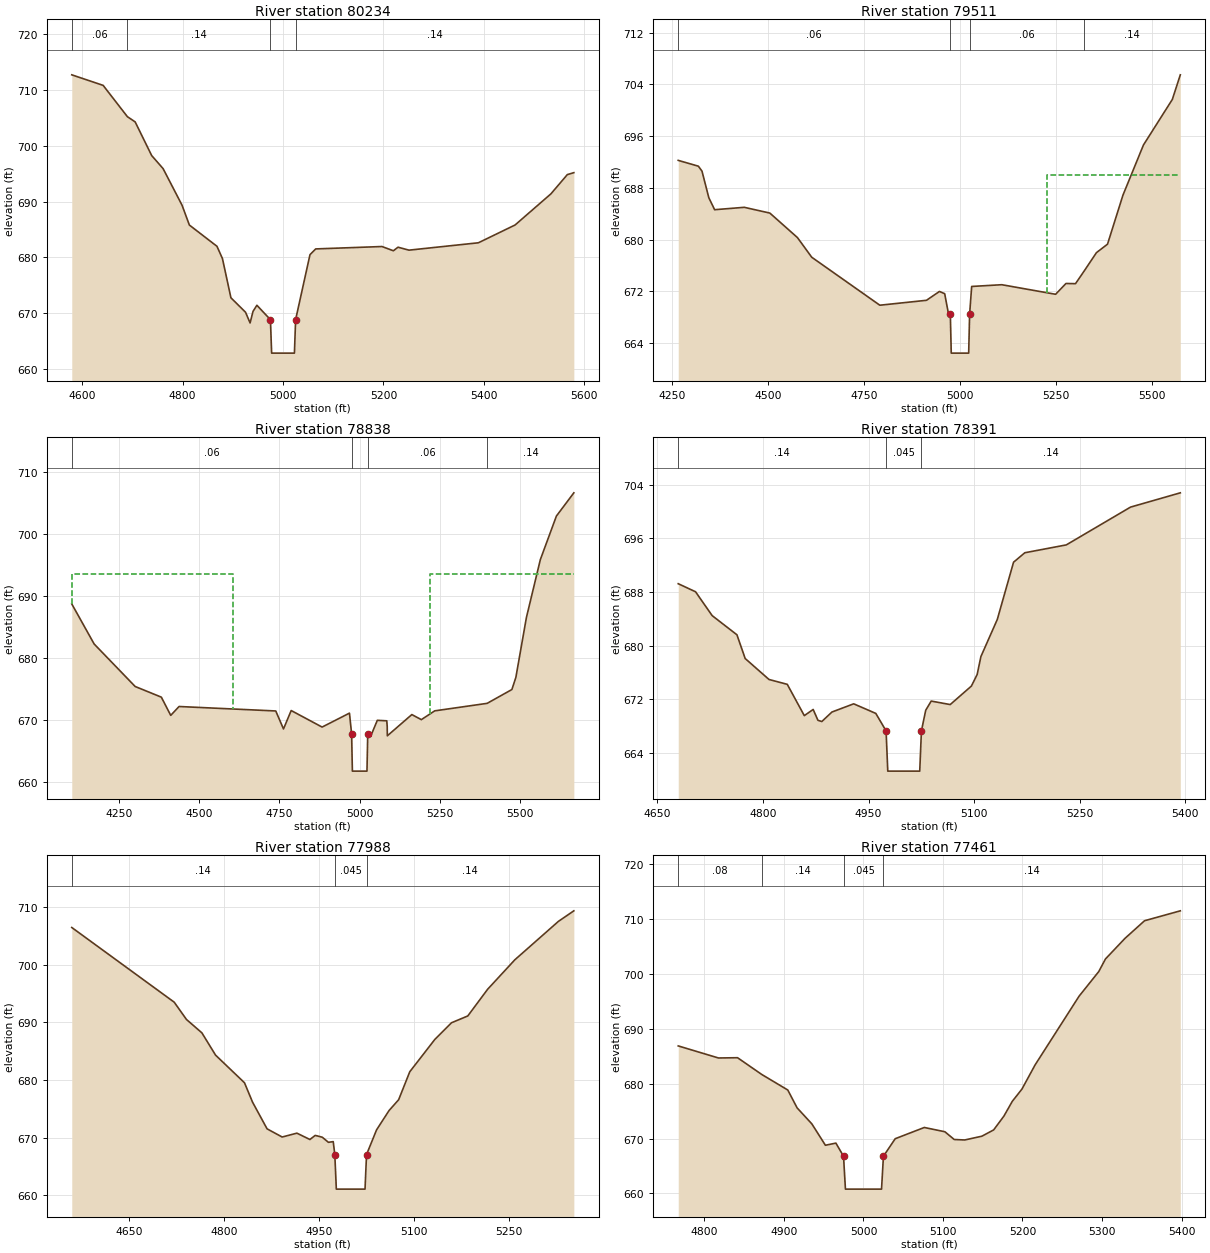
Type RM Length L Ch R = 1,80234,723,723,723
BEGIN DESCRIPTION:
Dutchman Creek 87.0
END DESCRIPTION:
XS GIS Cut Line= 4
      1545723.38       803257.77      1545516.05       803034.18
      1545227.43       802676.45      1545028.22       802550.42
#Sta/Elev= 30
  4579.1  712.73  4641.6  710.84  4689.9  705.23  4705.4  704.29  4738.3  698.26
  4761.1  695.91  4798.8  689.36  4813.4  685.80  4868.4  681.99  4879.3  679.79
  4896.2  672.76  4925.3  670.17  4934.4  668.25  4940.2  670.32  4947.9  671.42
  4974.9  668.84  4977.3  662.84  5022.7  662.84  5025.1  668.84  5053.7  680.49
  5065.1  681.52  5197.2  681.95  5219.8  681.19  5229.1  681.83  5250.9  681.30
  5389.2  682.62  5462.3  685.81  5533.7  691.39  5566.4  694.84  5579.4  695.19
#Mann=4,-1,0
  4579.1    0.06       0  4689.9    0.14       0  4974.9   0.045       0
  5025.1    0.14       0
Bank Sta=4974.9,5025.1
XS Rating Curve= 0
Exp/Cntr=0.3,0.1

Type RM Length L Ch R = 1,79511,673,673,673
BEGIN DESCRIPTION:
Dutchman Creek 86.0
END DESCRIPTION:
XS GIS Cut Line= 3
      1545903.44       803069.62      1545978.75       802768.38
      1545403.69       801953.70
#Sta/Elev= 30
  4266.2  692.24  4318.7  691.34  4328.1  690.57  4345.9  686.46  4361.0  684.61
  4438.2  684.98  4504.8  684.09  4576.7  680.30  4613.9  677.26  4791.3  669.84
  4912.8  670.60  4946.6  671.97  4960.2  671.62  4969.3  668.76  4974.9  668.43
  4977.3  662.43  5022.7  662.43  5025.1  668.43  5030.5  672.74  5109.0  673.01
  5249.1  671.53  5276.1  673.20  5300.9  673.17  5322.7  675.06  5355.5  677.97
  5384.3  679.28  5424.5  686.86  5477.9  694.62  5553.1  701.66  5573.9  705.47
#Mann=4,-1,0
  4266.2    0.06       0  4974.9   0.045       0  5025.1    0.06       0
  5322.7    0.14       0
#XS Ineff=2,0
       0                 5226.70    0.00  690.04
Permanent Ineff=
       F       F
Bank Sta=4974.9,5025.1
XS Rating Curve= 0
Exp/Cntr=0.3,0.1

Type RM Length L Ch R = 1,78838,447,447,447
BEGIN DESCRIPTION:
Dutchman Creek 85.0
END DESCRIPTION:
XS GIS Cut Line= 4
      1546542.18       803192.60      1546531.01       802909.57
      1546333.63       802283.92      1546225.63       801669.44
#Sta/Elev= 30
  4103.6  688.68  4173.3  682.21  4301.0  675.35  4382.5  673.63  4411.7  670.69
  4437.7  672.12  4738.7  671.40  4762.8  668.50  4786.8  671.47  4883.0  668.80
  4968.2  671.05  4974.9  667.69  4977.3  661.69  5022.7  661.69  5025.1  667.69
  5035.1  667.42  5054.9  669.89  5084.4  669.81  5085.7  668.93  5086.1  667.39
  5162.4  670.82  5192.0  670.00  5233.7  671.42  5396.9  672.63  5473.9  674.86
  5486.3  676.82  5519.1  686.48  5562.5  695.83  5612.5  702.86  5666.8  706.61
#Mann=4,-1,0
  4103.6    0.06       0  4974.9   0.045       0  5025.1    0.06       0
  5396.9    0.14       0
#XS Ineff=2,0
    0.00 4605.60  693.48 5220.10    0.00  693.48
Permanent Ineff=
       F       F
Bank Sta=4974.9,5025.1
XS Rating Curve= 0
Exp/Cntr=0.3,0.1

Type RM Length L Ch R = 1,78391,403,403,403
BEGIN DESCRIPTION:
Dutchman Creek 84.0
END DESCRIPTION:
XS GIS Cut Line= 4
      1546986.76       802568.49      1546843.83       802466.41
      1546743.28       802201.99      1546810.32       801956.20
#Sta/Elev= 30
  4679.6  689.23  4704.2  688.03  4727.8  684.47  4763.0  681.61  4774.7  678.07
  4808.6  674.94  4834.5  674.22  4858.7  669.55  4871.3  670.47  4878.1  668.85
  4883.6  668.67  4898.0  670.09  4928.9  671.31  4960.3  669.88  4974.9  667.27
  4977.3  661.27  5022.7  661.27  5025.1  667.27  5031.2  670.35  5039.0  671.72
  5066.0  671.20  5096.1  673.96  5104.3  675.69  5109.6  678.36  5132.9  683.90
  5156.0  692.44  5172.0  693.85  5230.9  695.02  5322.2  700.66  5392.9  702.79
#Mann=3,-1,0
  4679.6    0.14       0  4974.9   0.045       0  5025.1    0.14       0
Bank Sta=4974.9,5025.1
XS Rating Curve= 0
Exp/Cntr=0.3,0.1

Type RM Length L Ch R = 1,77988,527,527,527
BEGIN DESCRIPTION:
Dutchman Creek 83.0
END DESCRIPTION:
XS GIS Cut Line= 3
      1547354.22       802552.45      1547110.28       802078.58
      1547152.35       801820.56
#Sta/Elev= 30
  4558.7  706.46  4720.8  693.50  4740.2  690.50  4764.6  688.18  4786.2  684.32
  4832.0  679.52  4844.7  676.17  4867.7  671.53  4891.6  670.11  4914.9  670.78
  4935.5  669.68  4943.9  670.39  4955.0  670.08  4964.8  669.19  4972.4  669.31
  4974.9  667.07  4977.3  661.07  5022.7  661.07  5025.1  667.07  5041.0  671.36
  5060.7  674.70  5075.9  676.58  5093.5  681.43  5133.3  687.06  5159.5  689.93
  5185.3  691.11  5216.6  695.73  5259.8  700.86  5328.7  707.52  5353.1  709.35
#Mann=3,-1,0
  4558.7    0.14       0  4974.9   0.045       0  5025.1    0.14       0
Bank Sta=4974.9,5025.1
XS Rating Curve= 0
Exp/Cntr=0.3,0.1

Type RM Length L Ch R = 1,77461,413,413,413
BEGIN DESCRIPTION:
Dutchman Creek 82.0
END DESCRIPTION:
XS GIS Cut Line= 4
      1547819.51       802142.39      1547715.27       802094.00
      1547566.31       801859.38      1547406.41       801682.20
#Sta/Elev= 30
  4767.0  686.89  4817.6  684.69  4841.6  684.74  4872.0  681.69  4904.8  678.85
  4916.5  675.60  4935.1  672.67  4952.1  668.78  4965.3  669.17  4974.9  666.78
  4977.3  660.78  5022.7  660.78  5025.1  666.78  5039.9  669.97  5076.5  672.02
  5102.4  671.24  5114.1  669.83  5127.3  669.74  5148.9  670.43  5163.7  671.57
  5176.6  674.09  5187.2  676.79  5199.3  679.02  5215.9  683.44  5271.2  695.96
  5295.9  700.44  5304.4  702.75  5329.0  706.51  5353.5  709.71  5398.5  711.52
#Mann=4,-1,0
  4767.0    0.08       0  4872.0    0.14       0  4974.9   0.045       0
  5025.1    0.14       0
Bank Sta=4974.9,5025.1
XS Rating Curve= 0
Exp/Cntr=0.3,0.1

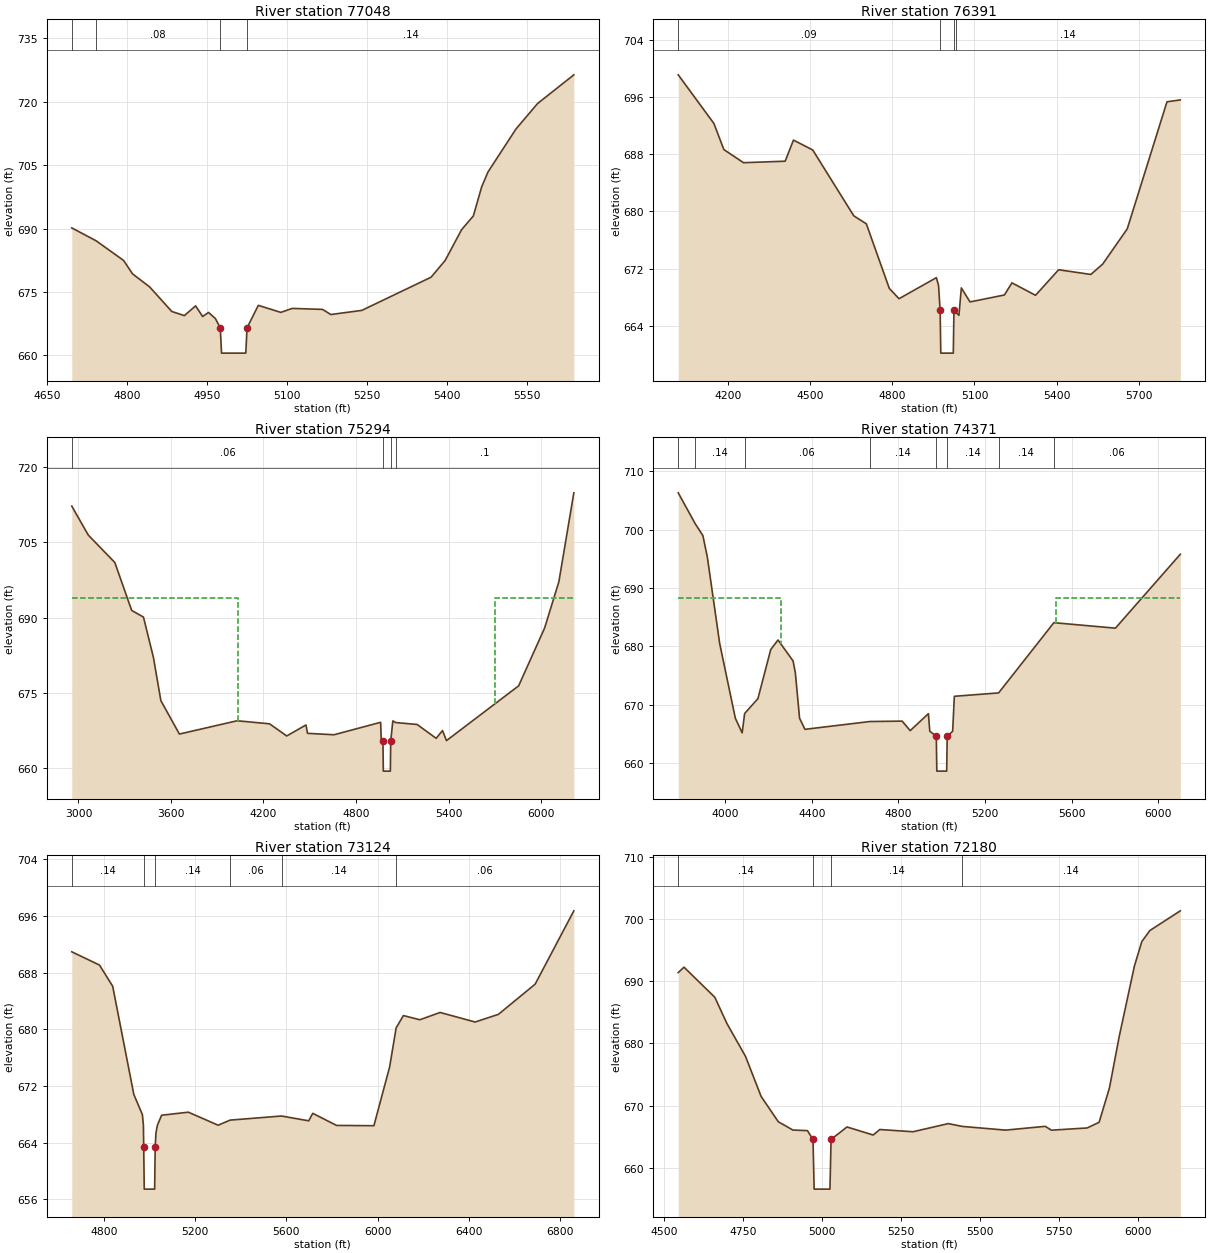
Type RM Length L Ch R = 1,77048,657,657,657
BEGIN DESCRIPTION:
Dutchman Creek 81.0
END DESCRIPTION:
XS GIS Cut Line= 4
      1548106.30       802008.33      1548076.51       801848.21
      1547774.86       801557.73      1547428.49       801464.62
#Sta/Elev= 30
  4696.8  690.15  4742.4  687.10  4793.9  682.45  4810.5  679.30  4842.9  676.17
  4884.1  670.39  4907.7  669.42  4928.7  671.72  4941.9  669.21  4952.9  670.16
  4965.6  668.75  4974.9  666.55  4977.3  660.55  5022.7  660.55  5025.1  666.55
  5046.2  671.84  5088.3  670.18  5109.8  671.12  5166.6  670.88  5181.9  669.67
  5240.0  670.65  5369.7  678.49  5396.1  682.45  5426.9  689.73  5448.9  692.97
  5464.6  699.89  5476.4  703.38  5528.9  713.55  5569.2  719.54  5637.1  726.32
#Mann=4,-1,0
  4696.8    0.09       0  4742.4    0.08       0  4974.9   0.045       0
  5025.1    0.14       0
Bank Sta=4974.9,5025.1
XS Rating Curve= 0
Exp/Cntr=0.3,0.1

Type RM Length L Ch R = 1,76391,1097,1097,1097
BEGIN DESCRIPTION:
Dutchman Creek 80.0
END DESCRIPTION:
XS GIS Cut Line= 4
      1549245.49       801956.29      1548839.38       801524.80
      1547910.41       801197.24      1547660.17       801158.51
#Sta/Elev= 30
  4019.8  699.16  4150.0  692.33  4186.2  688.68  4257.9  686.84  4409.7  687.05
  4440.0  690.01  4510.3  688.62  4660.0  679.39  4705.7  678.27  4789.5  669.21
  4824.9  667.77  4961.1  670.72  4969.0  669.64  4974.8  666.14  4977.2  660.14
  5022.8  660.14  5025.2  666.14  5033.4  665.82  5043.4  665.44  5052.1  669.28
  5083.8  667.32  5209.0  668.29  5236.7  669.99  5322.7  668.25  5406.9  671.83
  5524.3  671.17  5567.5  672.62  5657.1  677.56  5802.0  695.38  5850.6  695.64
#Mann=4,-1,0
  4019.8    0.09       0  4974.8   0.045       0  5025.2    0.09       0
  5033.4    0.14       0
Bank Sta=4974.8,5025.2
XS Rating Curve= 0
Exp/Cntr=0.3,0.1

Type RM Length L Ch R = 1,75294,923,923,923
BEGIN DESCRIPTION:
Dutchman Creek 79.0
END DESCRIPTION:
XS GIS Cut Line= 4
      1550387.75       800264.12      1548340.19       800331.81
      1547552.22       800358.16      1547138.75       800424.87
#Sta/Elev= 30
  2956.8  712.26  3063.6  706.49  3236.1  701.01  3345.3  691.46  3421.8  690.13
  3486.2  682.11  3534.6  673.48  3654.8  666.82  4029.1  669.47  4239.5  668.86
  4351.0  666.44  4475.5  668.63  4485.8  666.96  4657.7  666.68  4959.7  669.16
  4964.0  665.43  4974.8  665.43  4977.2  659.43  5022.8  659.43  5025.2  665.43
  5038.9  669.44  5057.5  669.11  5196.5  668.73  5319.8  665.97  5361.0  667.51
  5386.7  665.51  5854.8  676.43  6023.1  687.95  6115.4  697.15  6212.7  714.90
#Mann=4,-1,0
  2956.8    0.06       0  4974.8   0.045       0  5025.2    0.06       0
  5057.5     0.1       0
#XS Ineff=2,0
    0.00 4035.40  693.85 5699.80    0.00  693.85
Permanent Ineff=
       F       F
Bank Sta=4974.8,5025.2
XS Rating Curve= 0
Exp/Cntr=0.3,0.1

Type RM Length L Ch R = 1,74371,1247,1247,1247
BEGIN DESCRIPTION:
Dutchman Creek 78.0
END DESCRIPTION:
XS GIS Cut Line= 5
      1549663.55       799322.71      1549289.42       799614.71
      1548655.28       799623.84      1548459.11       799546.28
      1547460.21       799617.70
#Sta/Elev= 30
  3781.7  706.33  3860.1  701.04  3895.7  698.99  3916.4  695.28  3973.4  680.46
  4045.8  667.65  4077.2  665.14  4088.7  668.46  4150.1  671.02  4209.4  679.44
  4243.0  681.08  4312.6  677.49  4323.2  675.44  4342.7  667.65  4367.5  665.75
  4667.2  667.09  4816.9  667.16  4854.2  665.53  4938.3  668.44  4944.7  665.42
  4974.8  664.58  4977.2  658.58  5022.8  658.58  5025.2  664.58  5050.4  665.42
  5058.2  671.42  5262.9  672.00  5518.3  684.05  5802.9  683.11  6102.9  695.79
#Mann=8,-1,0
  3781.7    0.06       0  3860.1    0.14       0  4088.7    0.06       0
  4667.2    0.14       0  4974.8   0.045       0  5025.2    0.14       0
  5262.9    0.14       0  5518.3    0.06       0
#XS Ineff=2,0
    0.00 4255.50  688.37 5526.20    0.00  688.37
Permanent Ineff=
       F       F
Bank Sta=4974.8,5025.2
XS Rating Curve= 0
Exp/Cntr=0.3,0.1

Type RM Length L Ch R = 1,73124,944,944,944
BEGIN DESCRIPTION:
Dutchman Creek 77.0
END DESCRIPTION:
XS GIS Cut Line= 6
      1549451.30       799076.59      1549321.12       798976.79
      1549203.94       798968.11      1548787.27       799167.76
      1547806.37       799358.73      1547415.73       799597.46
#Sta/Elev= 30
  4659.5  690.95  4781.0  689.08  4838.9  686.08  4931.5  670.80  4969.0  667.95
  4973.5  666.48  4974.8  663.42  4977.2  657.42  5022.8  657.42  5025.2  663.42
  5028.5  665.35  5034.6  666.42  5053.2  667.86  5170.5  668.29  5301.0  666.45
  5353.5  667.17  5578.8  667.75  5698.1  667.07  5715.9  668.13  5820.0  666.42
  5983.8  666.38  6052.6  674.66  6081.4  680.21  6113.1  681.94  6185.2  681.35
  6274.1  682.38  6427.4  681.03  6529.4  682.11  6690.6  686.38  6860.2  696.74
#Mann=6,-1,0
  4659.5    0.14       0  4974.8   0.045       0  5025.2    0.14       0
  5353.5    0.06       0  5578.8    0.14       0  6081.4    0.06       0
Bank Sta=4974.8,5025.2
XS Rating Curve= 0
Exp/Cntr=0.3,0.1

Type RM Length L Ch R = 1,72180,928,928,928
BEGIN DESCRIPTION:
Dutchman Creek 76.0
END DESCRIPTION:
XS GIS Cut Line= 4
      1549389.37       798966.24      1549230.76       798741.58
      1549143.17       798438.60      1548379.26       797796.22
#Sta/Elev= 30
  4545.0  691.42  4563.2  692.29  4660.8  687.44  4698.7  683.25  4757.8  677.93
  4807.2  671.48  4861.6  667.40  4907.9  666.06  4953.8  665.97  4971.4  664.55
  4975.0  656.55  5025.0  656.55  5028.6  664.55  5078.9  666.56  5161.8  665.26
  5182.7  666.15  5287.9  665.79  5399.3  667.10  5443.5  666.65  5580.6  666.05
  5706.1  666.66  5725.7  666.04  5838.8  666.40  5876.6  667.31  5909.3  672.84
  5940.4  681.17  5988.3  692.47  6011.7  696.41  6037.3  698.19  6133.5  701.36
#Mann=4,-1,0
  4545.0    0.14       0  4971.4   0.045       0  5028.6    0.14       0
  5443.5    0.14       0
Bank Sta=4971.4,5028.6
XS Rating Curve= 0
Exp/Cntr=0.3,0.1