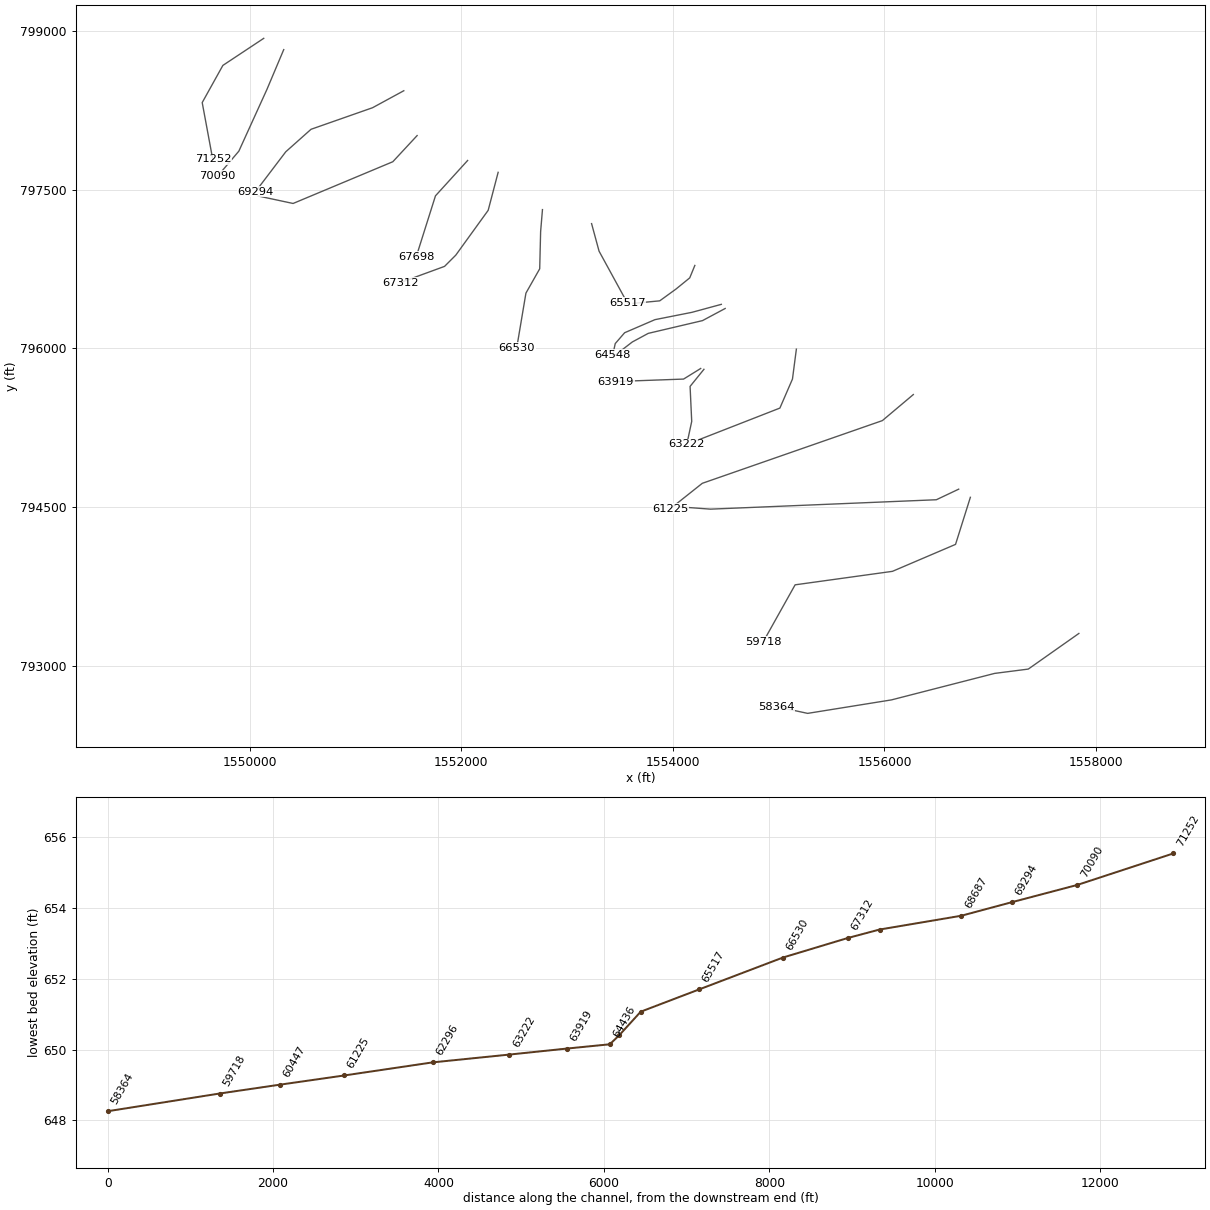
HEC-RAS study Dutchman Creek.prj: Dutchman Creek Limited Detail Study

--- Dutchman Creek.g01 (geometry) --- (continued)

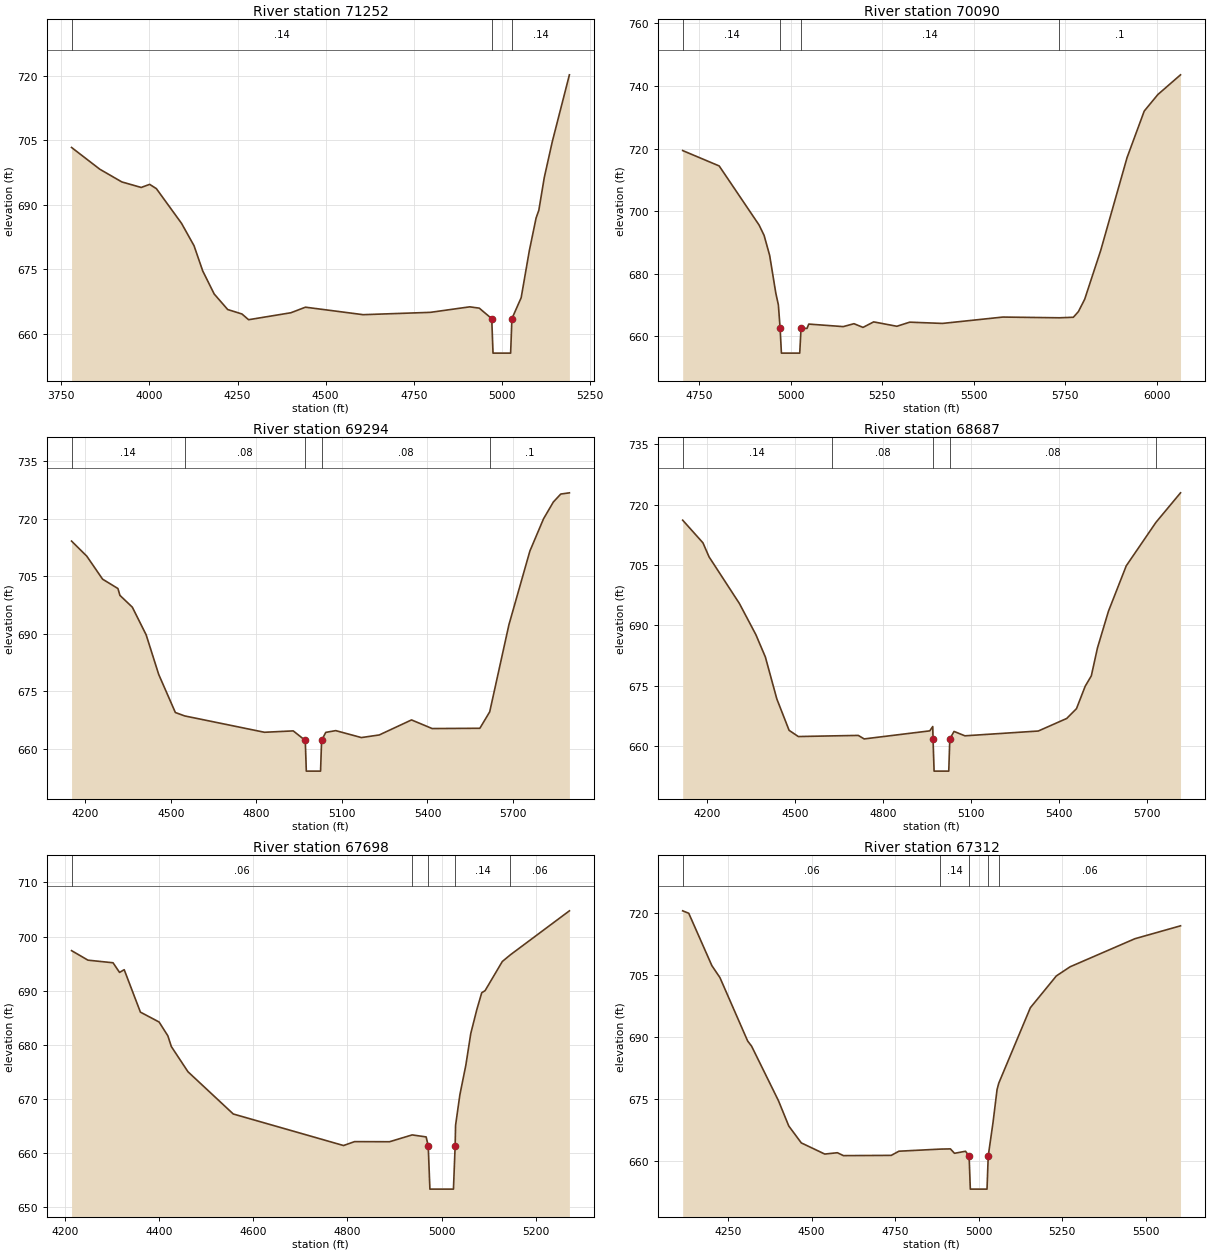
Type RM Length L Ch R = 1,71252,1162,1162,1162
BEGIN DESCRIPTION:
Dutchman Creek 75.0
END DESCRIPTION:
XS GIS Cut Line= 4
      1550132.76       798933.39      1549746.47       798677.31
      1549551.16       798325.75      1549650.98       797787.56
#Sta/Elev= 30
  3778.8  703.31  3858.9  698.26  3921.3  695.31  3976.5  694.02  4000.5  694.74
  4019.5  693.75  4090.9  685.69  4126.4  680.49  4151.1  674.63  4183.6  669.28
  4221.9  665.67  4262.5  664.63  4281.3  663.30  4401.5  664.92  4442.6  666.21
  4606.5  664.47  4797.1  665.01  4908.8  666.29  4936.0  665.99  4971.4  663.54
  4975.0  655.54  5025.0  655.54  5028.6  663.54  5054.9  668.41  5078.0  679.31
  5097.3  686.94  5105.0  688.71  5120.5  696.33  5143.1  704.62  5191.8  720.18
#Mann=3,-1,0
  3778.8    0.14       0  4971.4   0.045       0  5028.6    0.14       0
Bank Sta=4971.4,5028.6
XS Rating Curve= 0
Exp/Cntr=0.3,0.1

Type RM Length L Ch R = 1,70090,796,796,796
BEGIN DESCRIPTION:
Dutchman Creek 74.0
END DESCRIPTION:
XS GIS Cut Line= 4
      1550321.76       798826.75      1550162.68       798449.66
      1549897.56       797866.40      1549697.22       797630.70
#Sta/Elev= 30
  4705.4  719.36  4805.1  714.45  4914.1  695.56  4927.7  692.27  4942.9  685.87
  4959.7  673.82  4966.7  670.06  4971.4  662.65  4975.0  654.65  5025.0  654.65
  5028.6  662.65  5044.8  662.54  5049.7  663.93  5143.8  663.12  5173.1  664.05
  5197.8  662.87  5226.9  664.63  5290.2  663.23  5325.3  664.54  5414.8  664.14
  5579.5  666.17  5733.7  665.94  5772.1  666.11  5785.9  667.92  5803.0  671.85
  5846.7  687.43  5918.7  717.11  5965.6  731.98  6002.7  737.25  6064.7  743.56
#Mann=4,-1,0
  4705.4    0.14       0  4971.4   0.045       0  5028.6    0.14       0
  5733.7     0.1       0
Bank Sta=4971.4,5028.6
XS Rating Curve= 0
Exp/Cntr=0.3,0.1

Type RM Length L Ch R = 1,69294,607,607,607
BEGIN DESCRIPTION:
Dutchman Creek 73.0
END DESCRIPTION:
XS GIS Cut Line= 5
      1551456.57       798437.74      1551161.40       798277.14
      1550579.80       798073.14      1550341.09       797860.47
      1550054.66       797482.90
#Sta/Elev= 30
  4151.7  714.13  4205.2  710.20  4260.5  704.21  4314.3  701.77  4321.4  699.98
  4364.8  696.91  4413.3  689.70  4457.3  679.38  4515.8  669.44  4548.6  668.55
  4828.3  664.29  4929.2  664.65  4971.4  662.16  4975.0  654.16  5025.0  654.16
  5028.6  662.16  5043.2  664.26  5078.2  664.72  5168.2  662.91  5230.8  663.59
  5344.0  667.51  5416.5  665.26  5583.6  665.33  5618.2  669.62  5685.6  692.33
  5759.1  711.54  5806.9  719.94  5841.4  724.33  5867.4  726.40  5897.7  726.72
#Mann=5,-1,0
  4151.7    0.14       0  4548.6    0.08       0  4971.4   0.045       0
  5028.6    0.08       0  5618.2     0.1       0
Bank Sta=4971.4,5028.6
XS Rating Curve= 0
Exp/Cntr=0.3,0.1

Type RM Length L Ch R = 1,68687,989,989,989
BEGIN DESCRIPTION:
Dutchman Creek 72.0
END DESCRIPTION:
XS GIS Cut Line= 4
      1551582.52       798013.67      1551352.77       797766.24
      1550410.12       797371.51      1550080.22       797442.20
#Sta/Elev= 30
  4118.0  716.11  4187.2  710.47  4207.9  707.00  4311.3  695.42  4367.6  687.66
  4399.9  682.12  4438.9  671.72  4480.8  663.91  4512.2  662.37  4625.7  662.53
  4716.6  662.65  4736.7  661.78  4960.2  663.78  4970.4  664.86  4971.4  661.78
  4975.0  653.78  5025.0  653.78  5028.6  661.78  5043.0  663.64  5080.0  662.55
  5330.2  663.74  5427.1  666.86  5460.4  669.30  5490.1  674.87  5510.9  677.44
  5531.9  684.38  5569.2  693.46  5630.0  704.77  5731.2  715.56  5815.0  722.90
#Mann=5,-1,0
  4118.0    0.14       0  4625.7    0.08       0  4971.4   0.045       0
  5028.6    0.08       0  5731.2     0.1       0
Bank Sta=4971.4,5028.6
XS Rating Curve= 0
Exp/Cntr=0.3,0.1

Type RM Length L Ch R = 1,67698,386,386,386
BEGIN DESCRIPTION:
Dutchman Creek 71.0
END DESCRIPTION:
XS GIS Cut Line= 3
      1552059.87       797778.04      1551756.02       797443.80
      1551573.72       796866.51
#Sta/Elev= 30
  4214.1  697.42  4249.0  695.66  4302.2  695.18  4316.0  693.40  4325.9  693.90
  4360.3  686.07  4400.0  684.24  4418.6  681.69  4426.0  679.71  4461.3  675.06
  4557.5  667.26  4791.6  661.44  4815.0  662.16  4889.3  662.14  4937.3  663.40
  4967.0  663.03  4971.4  661.39  4975.0  653.39  5025.0  653.39  5028.6  661.39
  5029.5  665.17  5038.6  670.79  5051.3  676.27  5061.8  682.13  5074.6  686.53
  5085.0  689.64  5092.2  690.04  5128.7  695.41  5145.9  696.65  5271.2  704.77
#Mann=5,-1,0
  4214.1    0.06       0  4937.3    0.14       0  4971.4   0.045       0
  5028.6    0.14       0  5145.9    0.06       0
Bank Sta=4971.4,5028.6
XS Rating Curve= 0
Exp/Cntr=0.3,0.1

Type RM Length L Ch R = 1,67312,782,782,782
BEGIN DESCRIPTION:
Dutchman Creek 70.0
END DESCRIPTION:
XS GIS Cut Line= 5
      1552348.43       797666.06      1552254.18       797306.70
      1551947.82       796882.51      1551841.77       796776.46
      1551423.48       796623.28
#Sta/Elev= 30
  4114.0  720.52  4132.2  719.93  4201.4  707.25  4225.5  704.36  4308.5  689.01
  4320.4  687.74  4400.7  674.56  4431.6  668.43  4469.1  664.34  4539.3  661.64
  4577.0  661.96  4595.2  661.26  4738.2  661.32  4761.3  662.33  4885.6  662.84
  4915.4  662.89  4927.7  661.82  4960.6  662.32  4971.4  661.15  4975.0  653.15
  5025.0  653.15  5028.6  661.15  5043.0  669.31  5055.1  677.28  5060.2  678.81
  5154.7  697.06  5232.5  704.76  5273.6  706.97  5467.7  713.77  5604.2  716.89
#Mann=5,-1,0
  4114.0    0.06       0  4885.6    0.14       0  4971.4   0.045       0
  5028.6    0.14       0  5060.2    0.06       0
Bank Sta=4971.4,5028.6
XS Rating Curve= 0
Exp/Cntr=0.3,0.1

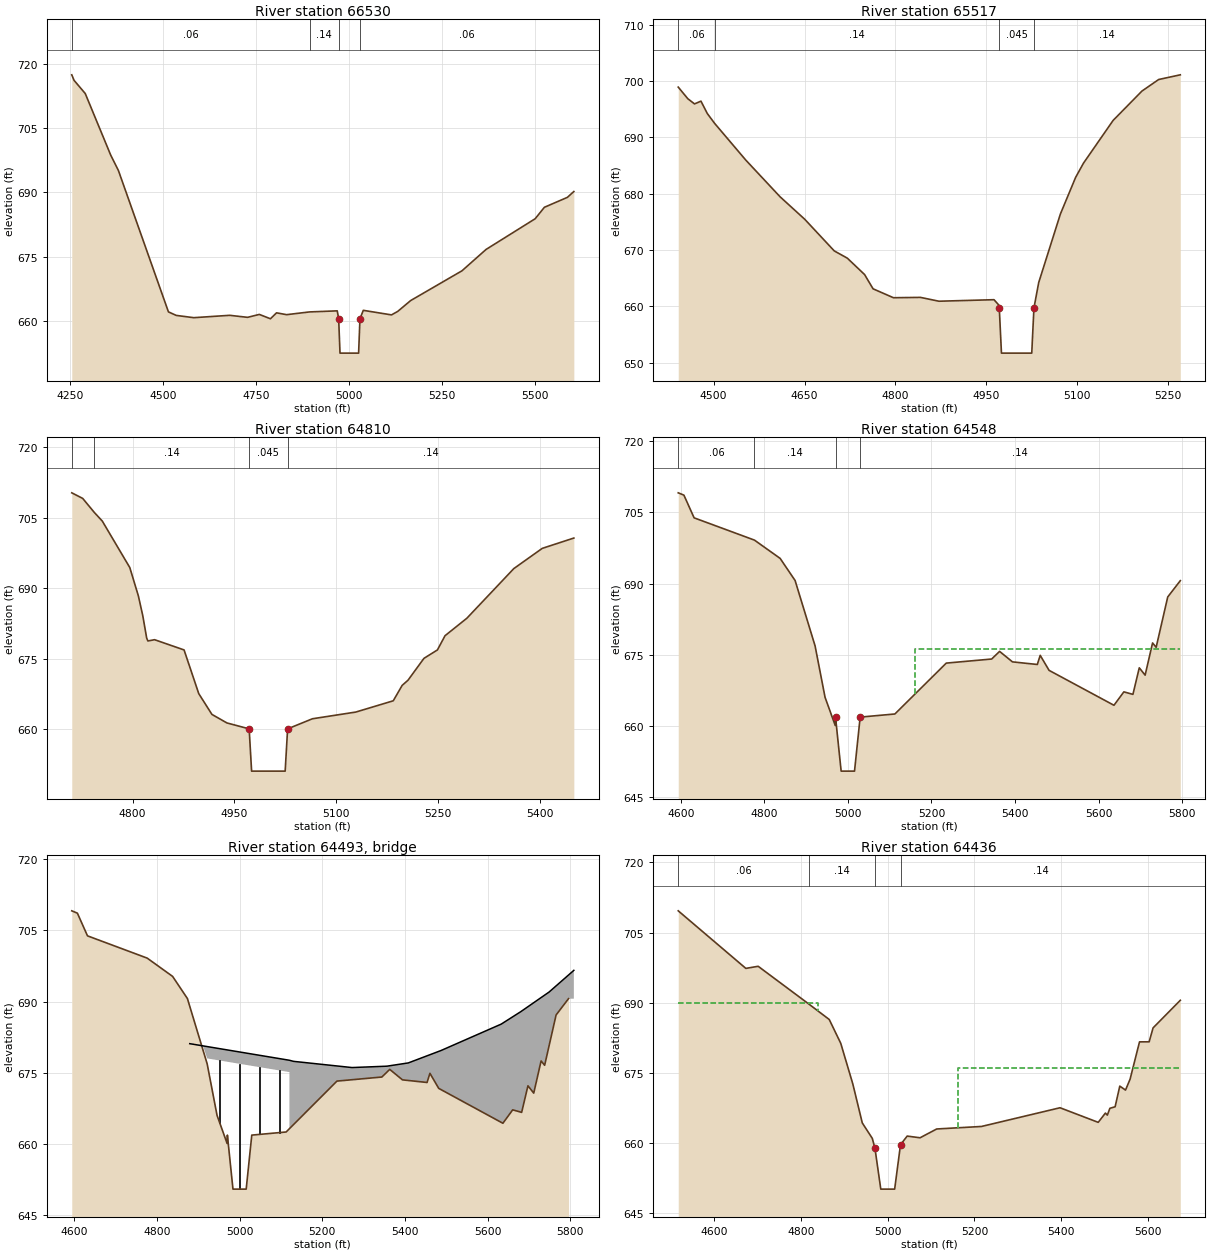
Type RM Length L Ch R = 1,66530,1013,1013,1013
BEGIN DESCRIPTION:
Dutchman Creek 69.0
END DESCRIPTION:
XS GIS Cut Line= 5
      1552767.30       797313.58      1552749.94       797105.26
      1552741.26       796753.70      1552611.05       796523.67
      1552524.25       796007.15
#Sta/Elev= 30
  4254.4  717.38  4260.5  716.10  4290.6  713.03  4359.2  698.66  4379.7  695.11
  4514.1  662.20  4535.1  661.38  4582.0  660.85  4678.7  661.40  4726.7  660.93
  4758.3  661.61  4788.1  660.60  4804.5  661.98  4831.4  661.55  4893.2  662.19
  4967.6  662.44  4971.4  660.60  4975.0  652.60  5025.0  652.60  5028.6  660.60
  5037.6  662.56  5113.3  661.50  5129.9  662.30  5164.9  664.84  5302.8  671.77
  5367.3  676.73  5499.3  683.88  5524.1  686.55  5585.9  688.86  5603.2  690.22
#Mann=4,-1,0
  4254.4    0.06       0  4893.2    0.14       0  4971.4   0.045       0
  5028.6    0.06       0
Bank Sta=4971.4,5028.6
XS Rating Curve= 0
Exp/Cntr=0.3,0.1

Type RM Length L Ch R = 1,65517,707,707,707
BEGIN DESCRIPTION:
Dutchman Creek 68.0
END DESCRIPTION:
XS GIS Cut Line= 3
      1553231.59       797181.09      1553302.28       796920.33
      1553570.00       796430.14
#Sta/Elev= 30
  4441.5  698.90  4457.4  696.83  4468.4  695.92  4479.0  696.41  4489.5  694.21
  4501.7  692.45  4553.1  685.94  4609.7  679.43  4650.4  675.44  4699.0  669.84
  4720.6  668.55  4749.1  665.64  4763.1  663.11  4796.7  661.53  4841.3  661.59
  4871.8  660.91  4962.7  661.18  4970.7  660.22  4971.4  659.70  4975.0  651.70
  5025.0  651.70  5028.6  659.70  5036.5  664.23  5072.3  676.39  5097.4  682.88
  5110.4  685.41  5159.3  692.99  5206.9  698.20  5234.5  700.25  5270.2  701.08
#Mann=4,-1,0
  4441.5    0.06       0  4501.7    0.14       0  4971.4   0.045       0
  5028.6    0.14       0
Bank Sta=4971.4,5028.6
XS Rating Curve= 0
Exp/Cntr=0.3,0.1

Type RM Length L Ch R = 1,64810,262,262,262
BEGIN DESCRIPTION:
Dutchman Creek 67.0
END DESCRIPTION:
XS GIS Cut Line= 5
      1554207.61       796785.44      1554159.34       796667.78
      1554029.63       796562.20      1553875.79       796450.59
      1553622.42       796426.46
#Sta/Elev= 30
  4710.6  710.34  4726.7  709.15  4743.8  706.16  4755.5  704.33  4796.0  694.43
  4808.6  688.40  4815.1  684.19  4820.9  679.38  4822.7  678.79  4832.5  679.06
  4875.9  676.88  4897.5  667.58  4916.9  663.15  4939.0  661.33  4971.7  660.07
  4975.3  651.07  5024.7  651.07  5028.3  660.07  5064.8  662.22  5128.7  663.65
  5183.8  666.05  5196.9  669.33  5205.5  670.43  5229.0  675.09  5248.8  676.88
  5260.0  679.91  5292.2  683.64  5361.3  694.21  5403.1  698.51  5449.6  700.71
#Mann=4,-1,0
  4710.6    0.12       0  4743.8    0.14       0  4971.7   0.045       0
  5028.3    0.14       0
Bank Sta=4971.7,5028.3
XS Rating Curve= 0
Exp/Cntr=0.5,0.3

Type RM Length L Ch R = 1,64548,112,112,112
BEGIN DESCRIPTION:
Milling Rd (DC) us
END DESCRIPTION:
XS GIS Cut Line= 6
      1554457.98       796417.41      1554180.45       796342.00
      1553830.54       796272.62      1553543.98       796148.94
      1553455.21       796046.40      1553431.88       795939.37
#Sta/Elev= 30
  4594.1  709.14  4607.7  708.65  4632.1  703.86  4776.5  699.16  4838.0  695.30
  4873.8  690.63  4921.6  676.84  4945.5  665.97  4969.9  660.03  4970.5  661.80
  4984.0  650.40  5016.0  650.40  5029.5  661.80  5112.6  662.46  5235.6  673.20
  5344.2  674.06  5363.2  675.67  5394.0  673.46  5453.5  672.91  5460.4  674.84
  5481.6  671.67  5636.9  664.30  5660.6  667.13  5682.3  666.60  5697.5  672.21
  5711.5  670.66  5729.3  677.45  5737.9  676.54  5765.6  687.16  5795.7  690.60
#Mann=4,-1,0
  4594.1    0.06       0  4776.5    0.14       0  4970.5   0.045       0
  5029.5    0.14       0
#XS Ineff=2,0
    0.00 4840.00  689.92 5160.00    0.00  676.13
Permanent Ineff=
       F       F
Bank Sta=4970.5,5029.5
XS Rating Curve= 0
Exp/Cntr=0.5,0.3

Type RM Length L Ch R =3,64493,,,
BEGIN DESCRIPTION:
Milling Rd (DC) tor
Structure ID: LDS_DC_05
Approximate Survey Structure
END DESCRIPTION:
Bridge Culvert--1,0,-1,-1,0
Deck Dist Width WeirC Skew NumUp NumDn MinLoCord MaxHiCord MaxSubmerge Is_Ogee
39.5,31,3,,13,13,,,0.95,0,1,1,,,
  4879.5  4879.5  5120.5  5120.5  5130.5  5272.0  5356.2  5408.1  5487.0  5632.8
  5680.0  5748.6  5808.5
  681.10  681.10  677.60  677.60  677.37  676.06  676.35  677.04  679.65  685.23
  687.85  692.00  696.58
  630.40  678.60  675.10  630.40  630.40  630.40  630.40  630.40  630.40  630.40
  630.40  630.40  630.40
  4879.5  4879.5  5120.5  5120.5  5130.5  5272.0  5356.2  5408.1  5487.0  5632.8
  5680.0  5748.6  5808.5
  681.10  681.10  677.60  677.60  677.37  676.06  676.35  677.04  679.65  685.23
  687.85  692.00  696.58
  630.40  678.60  675.10  630.40  630.40  630.40  630.40  630.40  630.40  630.40
  630.40  630.40  630.40
Pier Skew, UpSta & Num, DnSta & Num=,4903.6,2,4903.6,2,0,0,0,0,0
       3       3
  681.64  678.60
       3       3
  677.16  678.60
Pier Skew, UpSta & Num, DnSta & Num=,4951.8,2,4951.8,2,0,0,0,0,0
       3       3
  664.64  678.60
       3       3
  663.09  678.60
Pier Skew, UpSta & Num, DnSta & Num=,5000,2,5000,2,0,0,0,0,0
       3       3
  650.40  678.60
       3       3
  650.15  678.60
Pier Skew, UpSta & Num, DnSta & Num=,5048.2,2,5048.2,2,0,0,0,0,0
       3       3
  661.46  678.60
       3       3
  661.38  678.60
Pier Skew, UpSta & Num, DnSta & Num=,5096.4,2,5096.4,2,0,0,0,0,0
       3       3
  661.94  676.00
       3       3
  661.82  676.00
Abutment Skew #Up #Dn=,2,2
  4879.5  4892.0
  678.60  685.10
  4879.5  4892.0
  678.60  675.10
Abutment Skew #Up #Dn=,2,2
  5108.0  5120.5
  662.29  675.10
  5108.0  5120.5
  662.68  675.10
BR Coef=1,1,0,1.25,0,,,0.8,0,2,0,
WSPro=,,,, 1 ,,,, 0 ,,,, 0 ,,,,-1 ,-1 ,-1 , 0 , 0 , 0 , 0 , 0
BC Design=,,0,,0,,,,,,

Type RM Length L Ch R = 1,64436,517,517,517
BEGIN DESCRIPTION:
Milling Rd (DC) ds
END DESCRIPTION:
XS GIS Cut Line= 5
      1554494.14       796378.18      1554280.00       796263.57
      1553767.20       796142.91      1553616.37       796061.47
      1553444.44       795928.75
#Sta/Elev= 30
  4516.7  709.66  4672.7  697.35  4701.1  697.80  4819.0  689.66  4865.1  686.42
  4891.6  681.34  4919.5  672.63  4941.3  664.31  4964.4  661.00  4970.5  658.91
  4984.0  650.15  5016.0  650.15  5029.5  659.66  5044.9  661.49  5074.6  661.13
  5113.0  663.01  5216.3  663.55  5397.5  667.55  5485.6  664.43  5502.2  666.41
  5506.7  665.97  5512.5  667.43  5524.6  667.76  5535.4  672.18  5548.6  671.33
  5559.1  673.65  5580.9  681.64  5603.1  681.65  5612.2  684.63  5675.0  690.53
#Mann=4,-1,0
  4516.7    0.06       0  4819.0    0.14       0  4970.5   0.045       0
  5029.5    0.14       0
#XS Ineff=2,0
    0.00 4838.00  690.03 5162.00    0.00  675.98
Permanent Ineff=
       F       F
Bank Sta=4970.5,5029.5
XS Rating Curve= 0
Exp/Cntr=0.5,0.3

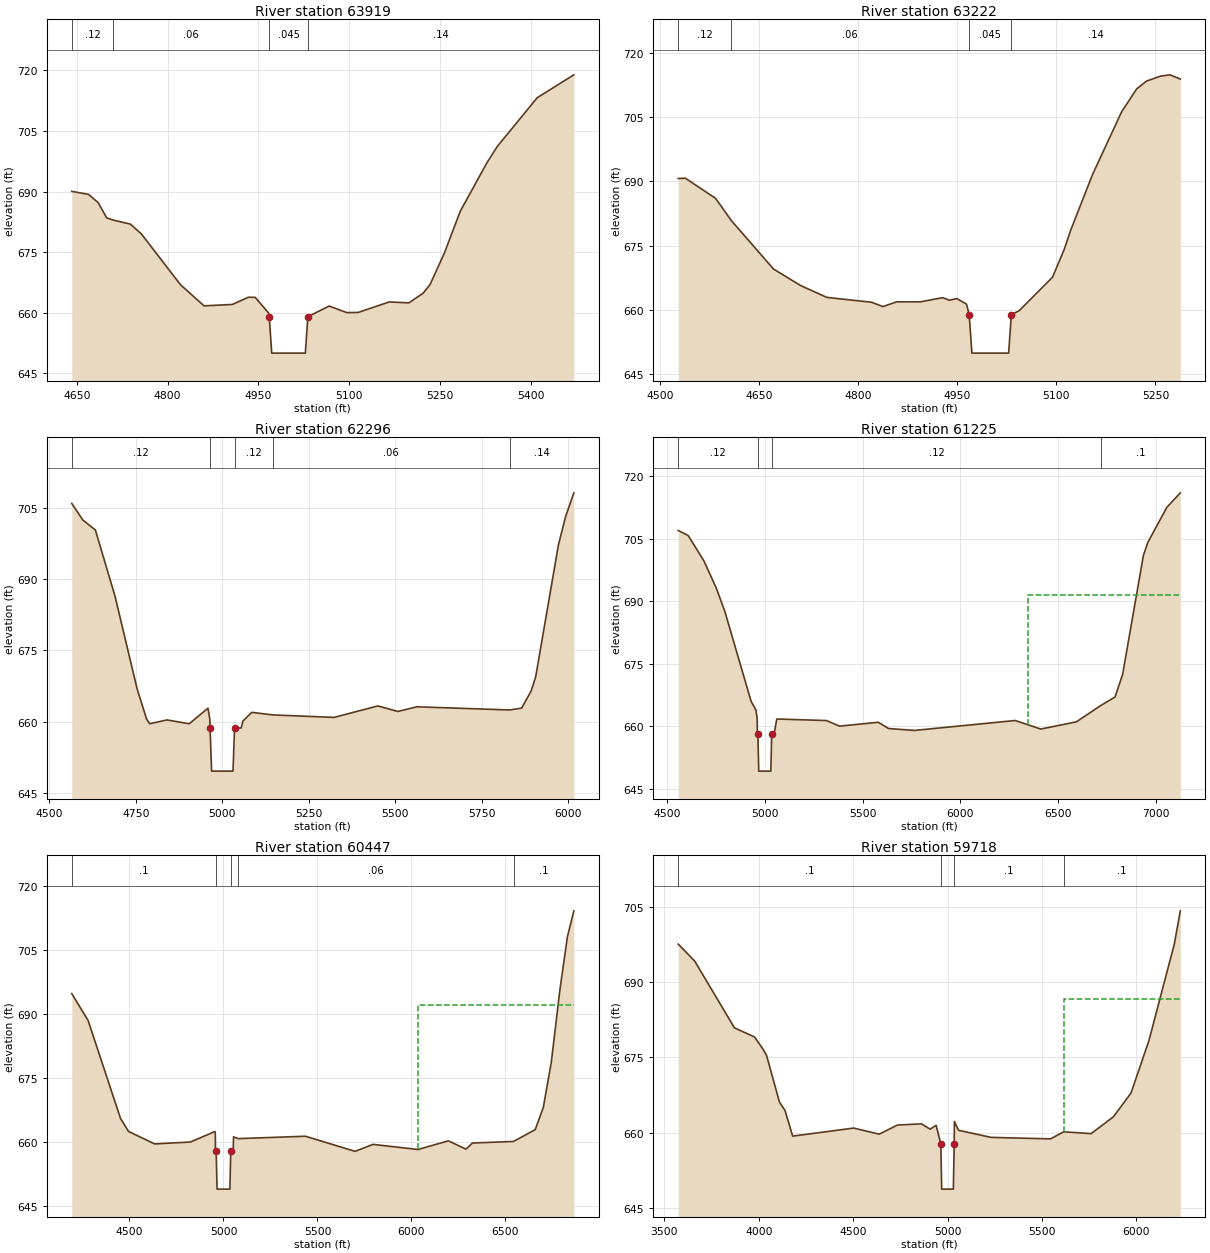
Type RM Length L Ch R = 1,63919,697,697,697
BEGIN DESCRIPTION:
Dutchman Creek 66.0
END DESCRIPTION:
XS GIS Cut Line= 3
      1554262.79       795810.78      1554101.03       795710.64
      1553461.79       795687.54
#Sta/Elev= 30
  4641.7  690.05  4669.4  689.30  4685.3  687.27  4699.4  683.50  4710.1  682.95
  4738.5  681.95  4756.7  679.54  4821.4  666.96  4860.3  661.73  4907.1  662.07
  4933.5  663.86  4944.9  663.83  4967.2  659.92  4968.1  659.03  4972.2  650.03
  5027.8  650.03  5031.9  659.03  5067.2  661.69  5096.2  660.06  5115.1  660.09
  5166.5  662.70  5198.9  662.46  5222.6  664.87  5234.0  667.02  5257.7  674.82
  5283.9  685.14  5328.2  697.19  5344.8  701.11  5411.0  713.21  5471.6  718.88
#Mann=4,-1,0
  4641.7    0.12       0  4710.1    0.06       0  4968.1   0.045       0
  5031.9    0.14       0
Bank Sta=4968.1,5031.9
XS Rating Curve= 0
Exp/Cntr=0.3,0.1

Type RM Length L Ch R = 1,63222,926,926,926
BEGIN DESCRIPTION:
Dutchman Creek 65.0
END DESCRIPTION:
XS GIS Cut Line= 4
      1554293.56       795803.07      1554162.64       795641.33
      1554178.04       795310.17      1554131.84       795094.57
#Sta/Elev= 30
  4527.6  690.69  4538.4  690.77  4584.2  686.05  4607.9  680.87  4671.9  669.52
  4713.1  665.65  4752.7  662.89  4820.2  661.76  4837.5  660.75  4858.2  661.85
  4894.1  661.85  4927.9  662.83  4938.4  662.23  4949.4  662.62  4964.0  661.32
  4968.1  658.86  4972.2  649.86  5027.8  649.86  5031.9  658.86  5043.8  659.78
  5094.2  667.61  5111.9  674.09  5121.4  678.46  5154.9  691.66  5198.9  706.30
  5221.7  711.65  5236.4  713.46  5257.6  714.63  5272.0  714.94  5287.7  713.96
#Mann=4,-1,0
  4527.6    0.12       0  4607.9    0.06       0  4968.1   0.045       0
  5031.9    0.14       0
Bank Sta=4968.1,5031.9
XS Rating Curve= 0
Exp/Cntr=0.3,0.1

Type RM Length L Ch R = 1,62296,1071,1071,1071
BEGIN DESCRIPTION:
Dutchman Creek 64.0
END DESCRIPTION:
XS GIS Cut Line= 4
      1555167.28       795993.82      1555130.39       795710.98
      1555011.52       795436.37      1554204.07       795120.77
#Sta/Elev= 30
  4564.8  705.89  4596.7  702.42  4633.1  700.30  4689.9  686.38  4753.5  666.99
  4780.8  660.64  4790.0  659.60  4840.0  660.40  4904.2  659.59  4958.5  662.86
  4964.0  660.51  4964.6  658.64  4969.1  649.64  5030.9  649.64  5035.4  658.64
  5054.5  658.72  5059.6  660.17  5085.1  661.99  5146.5  661.45  5323.3  660.93
  5449.6  663.34  5507.4  662.18  5562.7  663.16  5830.2  662.49  5865.2  662.88
  5892.7  666.47  5905.9  669.46  5971.6  697.16  5992.4  703.13  6016.2  708.12
#Mann=5,-1,0
  4564.8    0.12       0  4964.6   0.045       0  5035.4    0.12       0
  5146.5    0.06       0  5830.2    0.14       0
Bank Sta=4964.6,5035.4
XS Rating Curve= 0
Exp/Cntr=0.3,0.1

Type RM Length L Ch R = 1,61225,778,778,778
BEGIN DESCRIPTION:
Dutchman Creek 63.0
END DESCRIPTION:
XS GIS Cut Line= 4
      1556272.79       795564.30      1555980.17       795317.87
      1554278.16       794724.87      1553977.81       794486.12
#Sta/Elev= 30
  4557.2  706.99  4608.1  705.77  4688.4  699.72  4751.5  693.21  4795.3  687.63
  4930.0  666.02  4954.6  663.92  4961.2  661.90  4962.0  658.12  4964.6  658.27
  4969.1  649.27  5030.9  649.27  5035.4  658.27  5047.8  658.12  5061.2  661.77
  5315.6  661.40  5382.6  660.06  5581.0  660.99  5633.4  659.49  5765.8  659.03
  6280.9  661.41  6412.1  659.36  6593.9  661.09  6720.6  665.06  6791.7  667.04
  6830.5  672.44  6937.0  701.00  6959.6  704.13  7057.0  712.55  7125.8  716.02
#Mann=4,-1,0
  4557.2    0.12       0  4964.6   0.045       0  5035.4    0.12       0
  6720.6     0.1       0
#XS Ineff=2,0
       0                 6348.50    0.00  691.62
Permanent Ineff=
       F       F
Bank Sta=4964.6,5035.4
XS Rating Curve= 0
Exp/Cntr=0.3,0.1

Type RM Length L Ch R = 1,60447,729,729,729
BEGIN DESCRIPTION:
Dutchman Creek 62.0
END DESCRIPTION:
XS GIS Cut Line= 4
      1556701.53       794669.36      1556490.32       794569.32
      1554355.77       794480.38      1554055.60       794502.61
#Sta/Elev= 30
  4192.9  694.73  4279.7  688.46  4452.3  665.54  4494.8  662.51  4633.8  659.58
  4824.4  660.03  4954.8  662.48  4956.6  661.99  4957.4  657.94  4961.1  658.01
  4966.0  649.01  5034.0  649.01  5038.9  658.01  5051.7  657.94  5053.5  661.24
  5078.0  660.82  5435.8  661.38  5700.1  657.85  5795.4  659.47  6035.2  658.28
  6196.1  660.30  6290.4  658.36  6324.4  659.79  6543.2  660.16  6658.5  662.93
  6701.7  668.14  6744.4  678.79  6789.9  695.64  6829.9  708.05  6864.0  714.09
#Mann=5,-1,0
  4192.9     0.1       0  4961.1   0.045       0  5038.9     0.1       0
  5078.0    0.06       0  6543.2     0.1       0
#XS Ineff=2,0
       0                 6032.90    0.00  692.12
Permanent Ineff=
       F       F
Bank Sta=4961.1,5038.9
XS Rating Curve= 0
Exp/Cntr=0.3,0.1

Type RM Length L Ch R = 1,59718,1354,1354,1354
BEGIN DESCRIPTION:
Dutchman Creek 61.0
END DESCRIPTION:
XS GIS Cut Line= 5
      1556811.92       794592.42      1556671.81       794147.16
      1556075.28       793892.15      1555155.43       793764.64
      1554854.86       793227.28
#Sta/Elev= 30
  3573.4  697.52  3660.7  694.15  3871.2  680.86  3977.7  679.04  4023.4  676.57
  4041.3  675.38  4110.0  666.05  4139.0  664.43  4179.6  659.31  4503.1  660.91
  4638.3  659.70  4735.1  661.52  4862.4  661.75  4908.0  660.69  4939.6  661.47
  4964.6  657.76  4969.1  648.76  5030.9  648.76  5035.4  657.76  5036.5  662.22
  5058.7  660.47  5231.1  659.06  5545.5  658.76  5615.2  660.17  5760.9  659.81
  5878.5  663.14  5972.2  667.88  6067.6  678.39  6201.4  697.51  6233.3  704.15
#Mann=4,-1,0
  3573.4     0.1       0  4964.6   0.045       0  5035.4     0.1       0
  5615.2     0.1       0
#XS Ineff=2,0
       0                 5616.90    0.00  686.61
Permanent Ineff=
       F       F
Bank Sta=4964.6,5035.4
XS Rating Curve= 0
Exp/Cntr=0.3,0.1

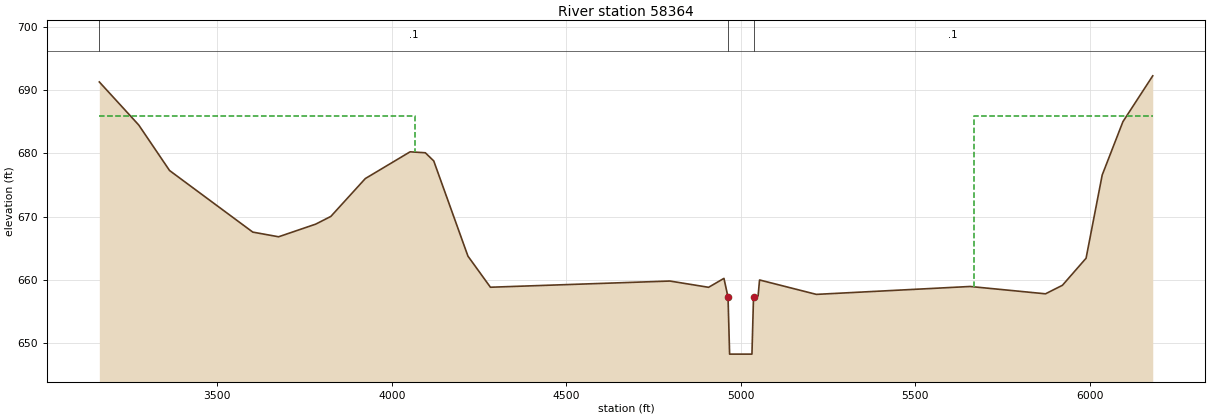
Type RM Length L Ch R = 1,58364,1536,1536,1536
BEGIN DESCRIPTION:
Dutchman Creek 60.0
END DESCRIPTION:
XS GIS Cut Line= 6
      1557837.55       793304.71      1557359.42       792967.75
      1557040.66       792926.76      1556066.17       792676.31
      1555273.82       792548.80      1554977.83       792612.56
#Sta/Elev= 30
  3162.4  691.31  3275.3  684.50  3363.6  677.30  3602.0  667.56  3675.9  666.82
  3782.2  668.82  3825.6  670.04  3924.4  676.03  4052.7  680.26  4096.3  680.11
  4120.4  678.82  4218.4  663.76  4282.8  658.84  4796.9  659.82  4907.8  658.83
  4951.8  660.24  4963.5  657.26  4968.0  648.26  5032.0  648.26  5036.5  657.26
  5049.6  657.46  5053.8  659.99  5216.5  657.71  5657.1  658.96  5873.0  657.80
  5921.5  659.15  5989.2  663.43  6035.4  676.59  6094.8  685.03  6180.2  692.28
#Mann=3,-1,0
  3162.4     0.1       0  4963.5   0.045       0  5036.5     0.1       0
#XS Ineff=2,0
    0.00 4065.40  685.87 5669.20    0.00  685.87
Permanent Ineff=
       F       F
Bank Sta=4963.5,5036.5
XS Rating Curve= 0
Exp/Cntr=0.3,0.1