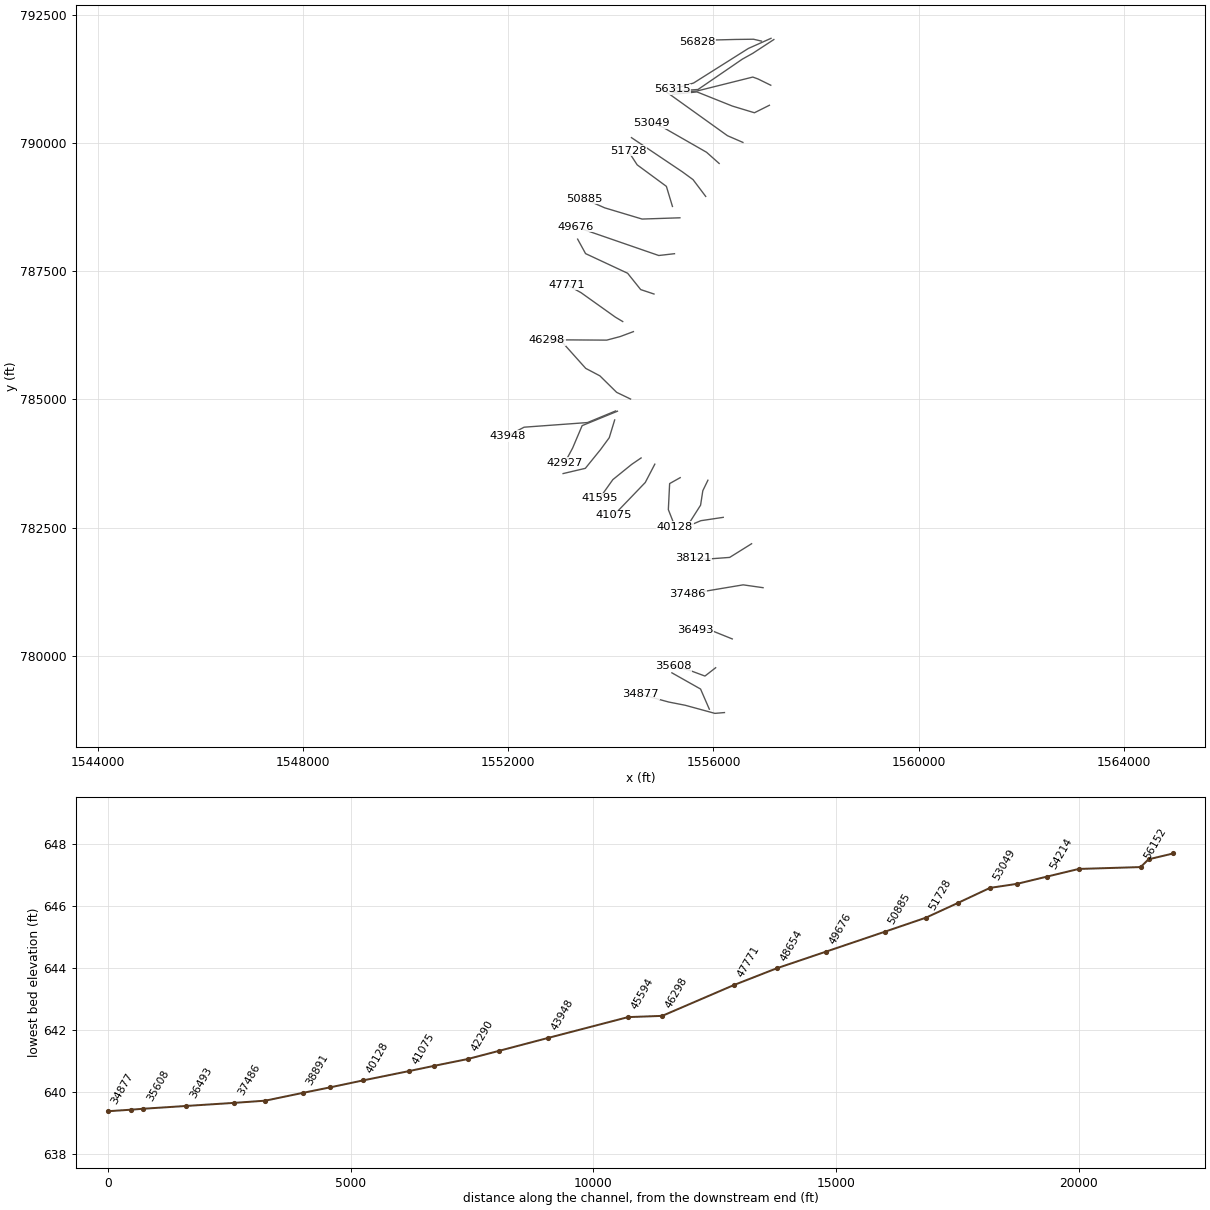
HEC-RAS study Dutchman Creek.prj: Dutchman Creek Limited Detail Study

--- Dutchman Creek.g01 (geometry) --- (continued)

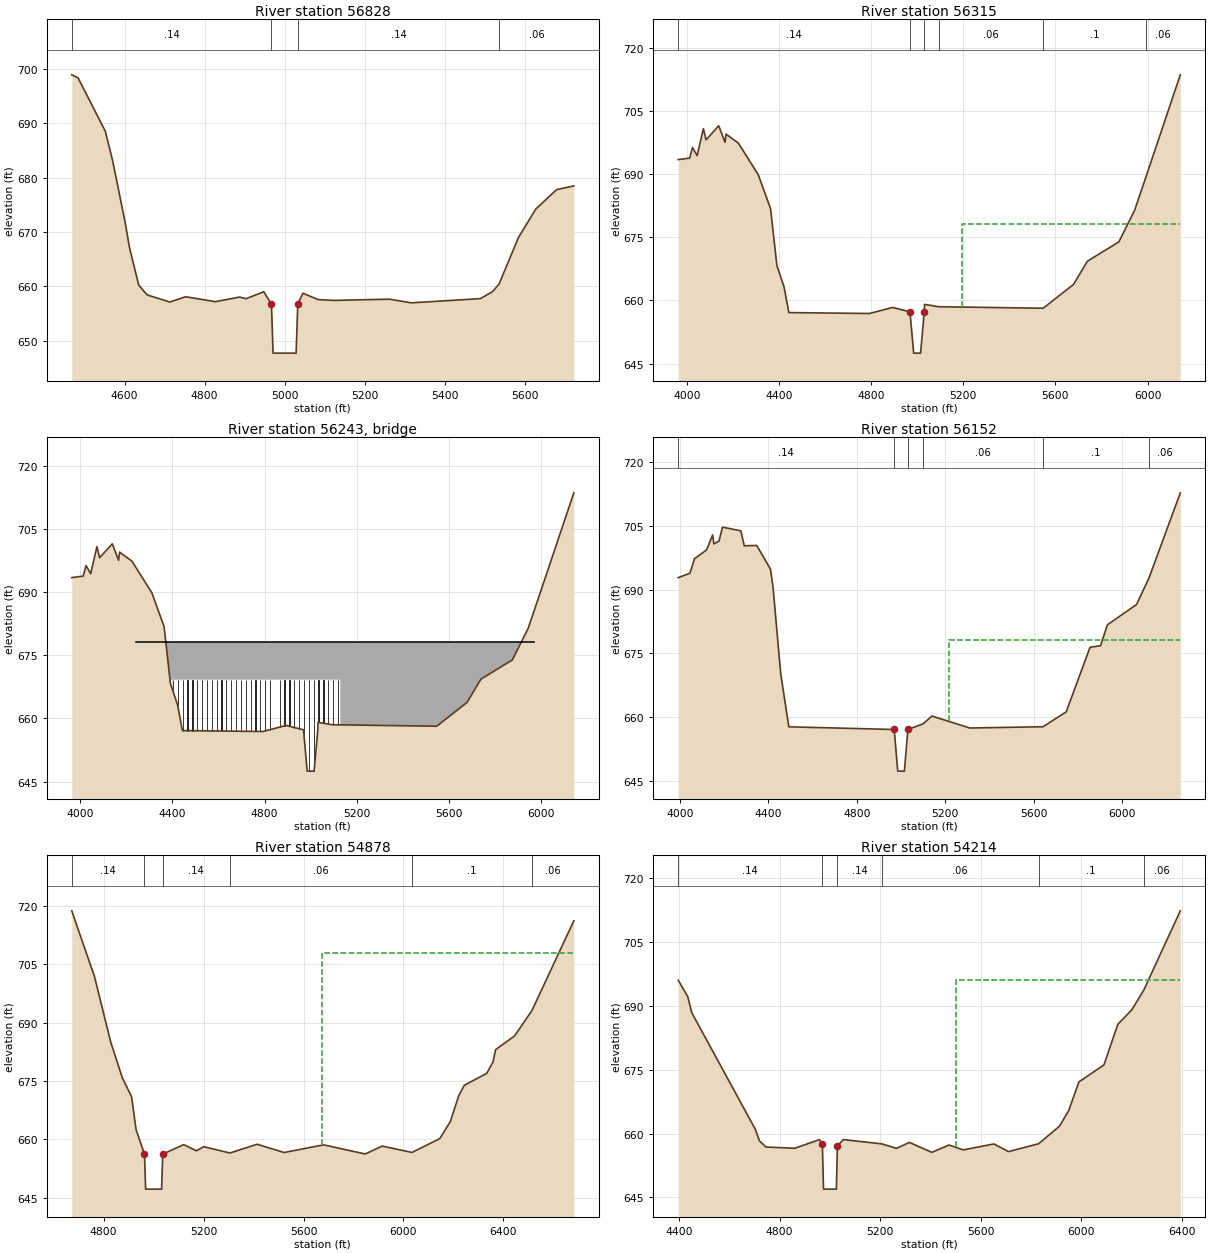
Type RM Length L Ch R = 1,56828,513,513,513
BEGIN DESCRIPTION:
Dutchman Creek 59.0
END DESCRIPTION:
XS GIS Cut Line= 5
      1556935.93       791984.14      1556781.10       792020.57
      1556425.91       792016.02      1555893.13       792002.36
      1555688.23       791970.49
#Sta/Elev= 30
  4468.2  698.92  4483.9  698.35  4552.1  688.53  4570.3  683.11  4601.5  671.79
  4612.4  667.13  4635.5  660.22  4656.5  658.41  4713.1  657.09  4752.6  658.07
  4827.1  657.16  4887.1  658.01  4903.6  657.71  4948.0  658.99  4967.2  656.69
  4971.2  647.69  5028.8  647.69  5032.9  656.69  5045.9  658.73  5083.3  657.55
  5122.9  657.39  5262.3  657.62  5316.5  656.95  5489.2  657.72  5520.4  659.04
  5536.2  660.45  5584.4  668.98  5627.9  674.23  5679.6  677.78  5722.8  678.47
#Mann=4,-1,0
  4468.2    0.14       0  4967.2   0.045       0  5032.9    0.14       0
  5536.2    0.06       0
Bank Sta=4967.2,5032.9
XS Rating Curve= 0
Exp/Cntr=0.5,0.3

Type RM Length L Ch R = 1,56315,163,163,163
BEGIN DESCRIPTION:
RR (DC) us
END DESCRIPTION:
XS GIS Cut Line= 4
      1557122.78       792037.91      1556681.15       791840.76
      1555612.56       791166.48      1555198.51       791044.24
#Sta/Elev= 30
  3963.3  693.42  4013.0  693.77  4025.3  696.27  4045.3  694.35  4072.5  700.76
  4084.0  698.12  4139.1  701.44  4166.5  697.52  4170.9  699.46  4224.5  697.31
  4310.6  689.84  4364.1  681.75  4391.4  668.29  4422.6  663.19  4443.3  657.12
  4793.2  656.90  4893.3  658.34  4969.0  657.30  4985.0  647.50  5015.0  647.50
  5031.0  657.30  5032.0  659.07  5094.2  658.51  5547.1  658.15  5678.9  663.81
  5739.0  669.31  5875.4  673.89  5944.0  681.39  5993.5  689.37  6142.2  713.53
#Mann=6,-1,0
  3963.3    0.14       0  4969.0   0.045       0  5031.0    0.14       0
  5094.2    0.06       0  5547.1     0.1       0  5993.5    0.06       0
#XS Ineff=2,0
    0.00 4328.60  678.20 5195.00    0.00  678.20
Permanent Ineff=
       F       F
Bank Sta=4969,5031
XS Rating Curve= 0
Exp/Cntr=0.5,0.3

Type RM Length L Ch R =3,56243,,,
BEGIN DESCRIPTION:
RR (DC) tor
Structure ID: LDS_DC_04
Approximate Survey Structure
END DESCRIPTION:
Bridge Culvert--1,0,-1,-1,0
Deck Dist Width WeirC Skew NumUp NumDn MinLoCord MaxHiCord MaxSubmerge Is_Ogee
66,12,3,,6,6,,,0.95,0,1,1,,,
  4242.8  4371.0  4371.0  5129.0  5129.0  5967.4
  678.20  678.20  678.20  678.20  678.20  678.20
  627.50  627.50  669.20  669.20  627.50  627.50
  4242.8  4371.0  4371.0  5129.0  5129.0  5967.4
  678.20  678.20  678.20  678.20  678.20  678.20
  627.50  627.50  669.20  669.20  627.50  627.50
Pier Skew, UpSta & Num, DnSta & Num=,4381.5,2,4381.5,2,0,0,0,0,0
       1       1
    0.00  669.20
       1       1
    0.00  669.20
Pier Skew, UpSta & Num, DnSta & Num=,4402.6,2,4402.6,2,0,0,0,0,0
       1       1
    0.00  669.20
       1       1
    0.00  669.20
Pier Skew, UpSta & Num, DnSta & Num=,4423.6,2,4423.6,2,0,0,0,0,0
       1       1
    0.00  669.20
       1       1
    0.00  669.20
Pier Skew, UpSta & Num, DnSta & Num=,4444.7,2,4444.7,2,0,0,0,0,0
       1       1
    0.00  669.20
       1       1
    0.00  669.20
Pier Skew, UpSta & Num, DnSta & Num=,4465.8,2,4465.8,2,0,0,0,0,0
       1       1
    0.00  669.20
       1       1
    0.00  669.20
Pier Skew, UpSta & Num, DnSta & Num=,4486.8,2,4486.8,2,0,0,0,0,0
       1       1
    0.00  669.20
       1       1
    0.00  669.20
Pier Skew, UpSta & Num, DnSta & Num=,4507.9,2,4507.9,2,0,0,0,0,0
       1       1
    0.00  669.20
       1       1
    0.00  669.20
Pier Skew, UpSta & Num, DnSta & Num=,4528.9,2,4528.9,2,0,0,0,0,0
       1       1
    0.00  669.20
       1       1
    0.00  669.20
Pier Skew, UpSta & Num, DnSta & Num=,4550,2,4550,2,0,0,0,0,0
       1       1
    0.00  669.20
       1       1
    0.00  669.20
Pier Skew, UpSta & Num, DnSta & Num=,4571,2,4571,2,0,0,0,0,0
       1       1
    0.00  669.20
       1       1
    0.00  669.20
Pier Skew, UpSta & Num, DnSta & Num=,4592.1,2,4592.1,2,0,0,0,0,0
       1       1
    0.00  669.20
       1       1
    0.00  669.20
Pier Skew, UpSta & Num, DnSta & Num=,4613.1,2,4613.1,2,0,0,0,0,0
       1       1
    0.00  669.20
       1       1
    0.00  669.20
Pier Skew, UpSta & Num, DnSta & Num=,4634.2,2,4634.2,2,0,0,0,0,0
       1       1
    0.00  669.20
       1       1
    0.00  669.20
Pier Skew, UpSta & Num, DnSta & Num=,4655.3,2,4655.3,2,0,0,0,0,0
       1       1
    0.00  669.20
       1       1
    0.00  669.20
Pier Skew, UpSta & Num, DnSta & Num=,4676.6,2,4676.3,2,0,0,0,0,0
       1       1
    0.00  669.20
       1       1
    0.00  669.20
Pier Skew, UpSta & Num, DnSta & Num=,4697.4,2,4697.4,2,0,0,0,0,0
       1       1
    0.00  669.20
       1       1
    0.00  669.20
Pier Skew, UpSta & Num, DnSta & Num=,4718.4,2,4718.4,2,0,0,0,0,0
       1       1
    0.00  669.20
       1       1
    0.00  669.20
Pier Skew, UpSta & Num, DnSta & Num=,4739.5,2,4739.5,2,0,0,0,0,0
       1       1
    0.00  669.20
       1       1
    0.00  669.20
Pier Skew, UpSta & Num, DnSta & Num=,4760.5,2,4760.5,2,0,0,0,0,0
       1       1
    0.00  669.20
       1       1
    0.00  669.20
Pier Skew, UpSta & Num, DnSta & Num=,4781.6,2,4781.6,2,0,0,0,0,0
       1       1
    0.00  669.20
       1       1
    0.00  669.20
Pier Skew, UpSta & Num, DnSta & Num=,4802.6,2,4802.6,2,0,0,0,0,0
       1       1
    0.00  669.20
       1       1
    0.00  669.20
Pier Skew, UpSta & Num, DnSta & Num=,4823.7,2,4823.7,2,0,0,0,0,0
       1       1
    0.00  669.20
       1       1
    0.00  669.20
Pier Skew, UpSta & Num, DnSta & Num=,484.8,2,4844.8,2,0,0,0,0,0
       1       1
    0.00  669.20
       1       1
    0.00  669.20
Pier Skew, UpSta & Num, DnSta & Num=,4865.8,2,4865.8,2,0,0,0,0,0
       1       1
    0.00  669.20
       1       1
    0.00  669.20
Pier Skew, UpSta & Num, DnSta & Num=,4886.9,2,4886.9,2,0,0,0,0,0
       1       1
    0.00  669.20
       1       1
    0.00  669.20
Pier Skew, UpSta & Num, DnSta & Num=,4907.9,2,4907.9,2,0,0,0,0,0
       1       1
    0.00  669.20
       1       1
    0.00  669.20
Pier Skew, UpSta & Num, DnSta & Num=,4929,2,4929,2,0,0,0,0,0
       1       1
    0.00  669.20
       1       1
    0.00  669.20
Pier Skew, UpSta & Num, DnSta & Num=,4950,2,4950,2,0,0,0,0,0
       1       1
    0.00  669.20
       1       1
    0.00  669.20
Pier Skew, UpSta & Num, DnSta & Num=,4971.1,2,4971.1,2,0,0,0,0,0
       1       1
    0.00  669.20
       1       1
    0.00  669.20
Pier Skew, UpSta & Num, DnSta & Num=,4992.1,2,4992.1,2,0,0,0,0,0
       1       1
    0.00  669.20
       1       1
    0.00  669.20
Pier Skew, UpSta & Num, DnSta & Num=,5013.2,2,5013.2,2,0,0,0,0,0
       1       1
    0.00  669.20
       1       1
    0.00  669.20
Pier Skew, UpSta & Num, DnSta & Num=,5034.3,2,5034.3,2,0,0,0,0,0
       1       1
    0.00  669.20
       1       1
    0.00  669.20
Pier Skew, UpSta & Num, DnSta & Num=,5055.3,2,5055.3,2,0,0,0,0,0
       1       1
    0.00  669.20
       1       1
    0.00  669.20
Pier Skew, UpSta & Num, DnSta & Num=,5076.4,2,5076.4,2,0,0,0,0,0
       1       1
    0.00  669.20
       1       1
    0.00  669.20
Pier Skew, UpSta & Num, DnSta & Num=,5097.4,2,5097.6,2,0,0,0,0,0
       1       1
    0.00  669.20
       1       1
    0.00  669.20
Pier Skew, UpSta & Num, DnSta & Num=,5118.5,2,5118.5,2,0,0,0,0,0
       1       1
    0.00  669.20
       1       1
    0.00  669.20
Abutment Skew #Up #Dn=,2,2
  4371.0  4384.0
  669.20  657.02
  4371.0  4384.0
  669.20  656.31
Abutment Skew #Up #Dn=,2,2
  5086.0  5129.0
  658.08  669.20
  5086.0  5129.0
  657.48  669.20
BR Coef=1,1,0,1.25,0,,,0.8,0,2,0,
WSPro=,,,, 1 ,,,, 0 ,,,, 0 ,,,,-1 ,-1 ,-1 , 0 , 0 , 0 , 0 , 0
BC Design=,,0,,0,,,,,,

Type RM Length L Ch R = 1,56152,1274,1274,1274
BEGIN DESCRIPTION:
RR (DC) ds
END DESCRIPTION:
XS GIS Cut Line= 6
      1557178.00       792014.27      1556767.89       791746.12
      1556562.85       791631.77      1556223.75       791399.13
      1555699.31       791040.30      1555202.45       791008.76
#Sta/Elev= 30
  3992.9  692.79  4046.0  693.84  4066.4  697.25  4120.6  699.30  4148.5  702.85
  4153.9  700.74  4177.2  701.40  4192.9  704.68  4275.7  703.82  4291.5  700.29
  4347.9  700.37  4409.9  694.78  4421.7  690.43  4455.8  670.28  4492.7  657.68
  4969.0  657.05  4985.0  647.25  5015.0  647.25  5031.0  657.05  5099.0  658.37
  5139.7  660.21  5310.8  657.40  5641.7  657.70  5746.6  661.21  5854.1  676.39
  5901.5  676.78  5932.7  681.69  6064.3  686.47  6120.0  692.63  6262.2  712.76
#Mann=6,-1,0
  3992.9    0.14       0  4969.0   0.045       0  5031.0    0.14       0
  5099.0    0.06       0  5641.7     0.1       0  6120.0    0.06       0
#XS Ineff=2,0
    0.00 4431.40  678.20 5215.00    0.00  678.20
Permanent Ineff=
       F       F
Bank Sta=4969,5031
XS Rating Curve= 0
Exp/Cntr=0.5,0.3

Type RM Length L Ch R = 1,54878,664,664,664
BEGIN DESCRIPTION:
Dutchman Creek 58.0
END DESCRIPTION:
XS GIS Cut Line= 5
      1557118.08       791123.49      1556867.62       791246.44
      1556767.44       791282.87      1555674.55       791009.65
      1555178.24       790982.33
#Sta/Elev= 30
  4672.5  718.76  4763.0  701.93  4828.6  684.96  4874.5  675.89  4911.8  670.94
  4930.0  662.43  4963.5  656.19  4968.0  647.19  5032.0  647.19  5036.5  656.19
  5120.4  658.63  5171.8  657.03  5200.3  658.11  5305.5  656.48  5414.0  658.73
  5522.6  656.61  5680.2  658.58  5846.8  656.23  5915.0  658.26  6033.9  656.62
  6145.4  660.19  6187.7  664.60  6220.4  671.10  6243.2  673.88  6333.2  676.97
  6358.2  679.88  6368.7  683.07  6444.5  686.58  6514.1  693.13  6681.7  716.19
#Mann=6,-1,0
  4672.5    0.14       0  4963.5   0.045       0  5036.5    0.14       0
  5305.5    0.06       0  6033.9     0.1       0  6514.1    0.06       0
#XS Ineff=2,0
       0                 5675.00    0.00  707.93
Permanent Ineff=
       F       F
Bank Sta=4963.5,5036.5
XS Rating Curve= 0
Exp/Cntr=0.3,0.1

Type RM Length L Ch R = 1,54214,607,607,607
BEGIN DESCRIPTION:
Dutchman Creek 57.0
END DESCRIPTION:
XS GIS Cut Line= 5
      1557091.25       790732.75      1556799.44       790586.85
      1556369.64       790716.97      1555679.60       790992.99
      1555202.45       790945.67
#Sta/Elev= 30
  4396.3  696.04  4434.0  692.20  4450.1  688.41  4703.2  660.99  4719.3  658.30
  4745.2  656.84  4859.6  656.54  4958.3  658.57  4969.9  657.54  4974.4  646.94
  5025.6  646.94  5029.7  657.11  5053.4  658.58  5206.3  657.58  5264.9  656.52
  5316.4  657.92  5405.4  655.58  5474.0  657.30  5530.4  656.16  5652.6  657.56
  5710.7  655.76  5830.7  657.61  5913.6  661.75  5949.9  665.36  5990.8  672.15
  6090.4  676.13  6145.5  685.66  6201.3  689.08  6248.9  693.72  6394.3  712.35
#Mann=6,-1,0
  4396.3    0.14       0  4969.9   0.045       0  5029.7    0.14       0
  5206.3    0.06       0  5830.7     0.1       0  6248.9    0.06       0
#XS Ineff=2,0
       0                 5500.00    0.00  696.00
Permanent Ineff=
       F       F
Bank Sta=4969.9,5029.7
XS Rating Curve= 0
Exp/Cntr=0.3,0.1

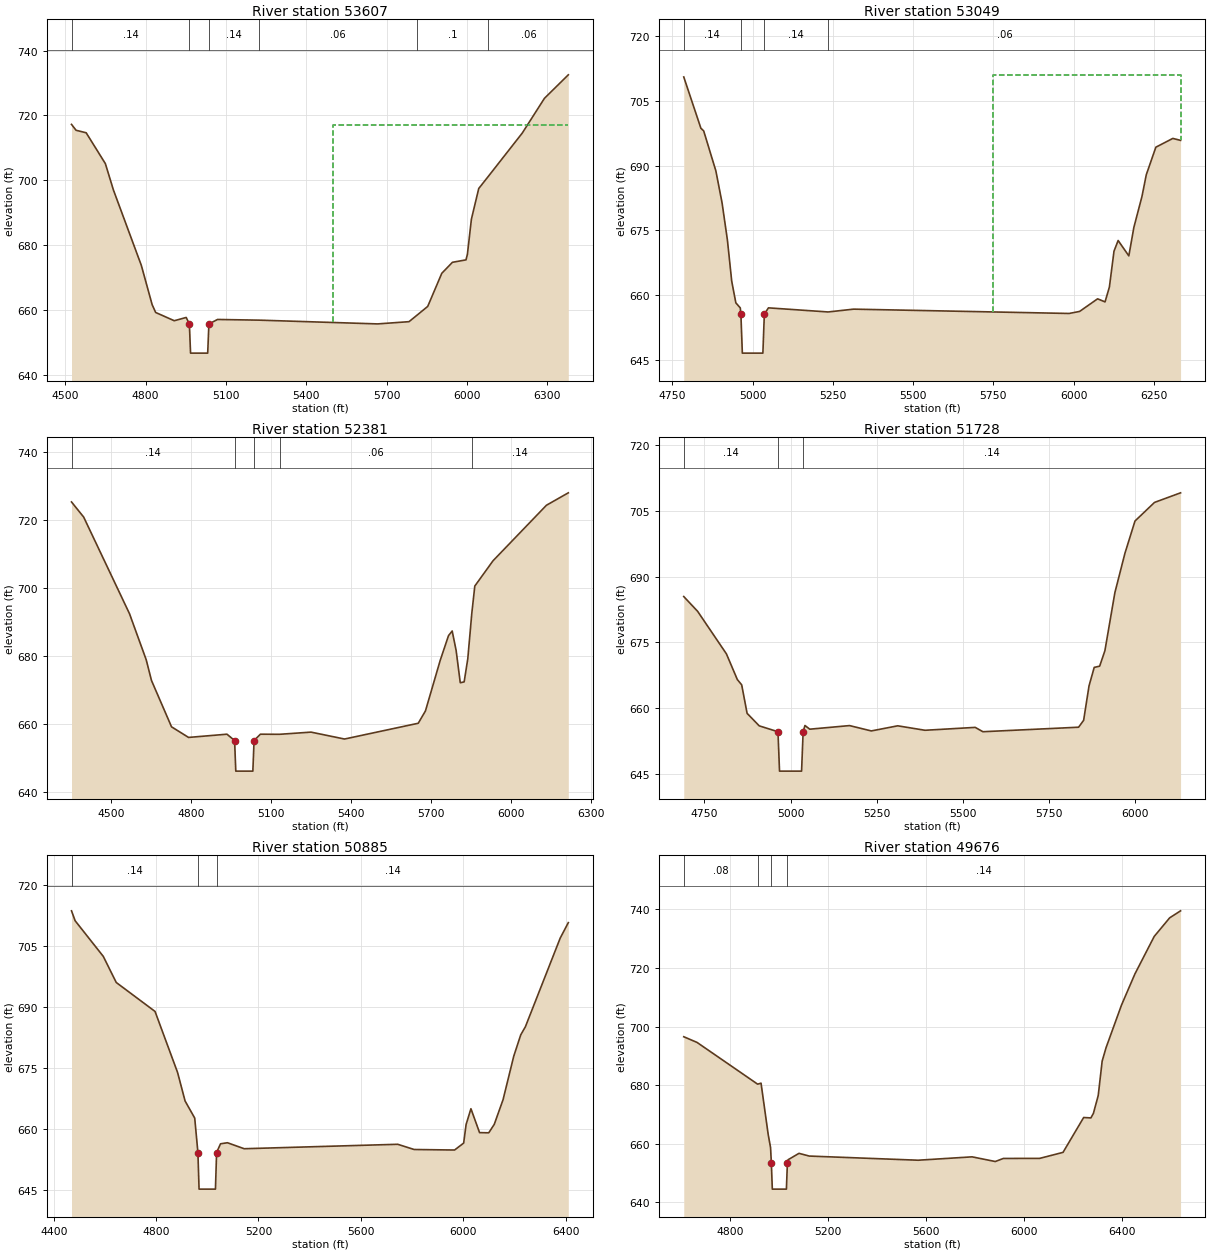
Type RM Length L Ch R = 1,53607,558,558,558
BEGIN DESCRIPTION:
Dutchman Creek 56.0
END DESCRIPTION:
XS GIS Cut Line= 3
      1556575.21       790008.69      1556273.70       790139.34
      1555032.41       791028.85
#Sta/Elev= 30
  4523.3  717.25  4540.4  715.43  4578.1  714.66  4649.8  705.14  4679.9  697.01
  4784.2  673.75  4824.4  661.68  4837.6  659.25  4907.1  656.70  4951.7  657.71
  4963.5  655.71  4968.0  646.71  5032.0  646.71  5036.5  655.71  5068.9  657.09
  5224.0  656.88  5666.7  655.72  5784.0  656.41  5814.0  658.42  5853.9  661.12
  5906.4  671.33  5946.2  674.72  5996.8  675.47  6002.1  677.21  6017.0  688.02
  6044.4  697.47  6080.8  701.28  6206.9  714.56  6289.9  725.29  6379.0  732.53
#Mann=6,-1,0
  4523.3    0.14       0  4963.5   0.045       0  5036.5    0.14       0
  5224.0    0.06       0  5814.0     0.1       0  6080.8    0.06       0
#XS Ineff=2,0
       0                 5500.00    0.00  717.00
Permanent Ineff=
       F       F
Bank Sta=4963.5,5036.5
XS Rating Curve= 0
Exp/Cntr=0.3,0.1

Type RM Length L Ch R = 1,53049,668,668,668
BEGIN DESCRIPTION:
Dutchman Creek 55.0
END DESCRIPTION:
XS GIS Cut Line= 4
      1556111.70       789598.01      1555865.80       789816.58
      1555014.26       790303.83      1554791.13       790385.79
#Sta/Elev= 30
  4785.5  710.51  4838.8  698.65  4847.6  698.02  4885.6  688.75  4904.9  681.34
  4921.5  672.76  4934.9  663.24  4947.8  658.21  4961.6  657.05  4963.5  655.58
  4968.0  646.58  5032.0  646.58  5036.5  655.58  5049.3  657.06  5235.1  656.11
  5314.4  656.76  5986.0  655.76  6018.7  656.23  6074.8  659.15  6098.0  658.44
  6111.5  661.86  6125.9  670.18  6138.8  672.65  6172.1  669.09  6187.8  675.69
  6212.9  682.81  6226.5  687.88  6256.3  694.25  6309.2  696.28  6333.3  695.83
#Mann=4,-1,0
  4785.5    0.14       0  4963.5   0.045       0  5036.5    0.14       0
  5235.1    0.06       0
#XS Ineff=2,0
       0                 5750.00    0.00  711.00
Permanent Ineff=
       F       F
Bank Sta=4963.5,5036.5
XS Rating Curve= 0
Exp/Cntr=0.3,0.1

Type RM Length L Ch R = 1,52381,653,653,653
BEGIN DESCRIPTION:
Dutchman Creek 54.0
END DESCRIPTION:
XS GIS Cut Line= 4
      1555849.05       788955.82      1555602.79       789282.48
      1555396.74       789433.25      1554401.69       790101.64
#Sta/Elev= 30
  4351.9  725.26  4397.6  720.80  4569.5  692.37  4632.1  678.83  4651.8  672.76
  4727.0  659.12  4790.9  656.00  4934.9  656.95  4963.5  655.09  4968.0  646.09
  5032.0  646.09  5036.5  655.09  5060.3  656.95  5132.1  656.92  5250.1  657.56
  5375.8  655.53  5652.2  660.17  5679.2  663.79  5734.8  678.72  5765.7  685.94
  5779.5  687.30  5794.3  681.57  5809.8  672.09  5824.4  672.34  5838.0  679.14
  5852.9  692.37  5864.3  700.52  5932.7  707.96  6133.0  724.29  6215.0  727.94
#Mann=5,-1,0
  4351.9    0.14       0  4963.5   0.045       0  5036.5    0.14       0
  5132.1    0.06       0  5852.9    0.14       0
Bank Sta=4963.5,5036.5
XS Rating Curve= 0
Exp/Cntr=0.3,0.1

Type RM Length L Ch R = 1,51728,843,843,843
BEGIN DESCRIPTION:
Dutchman Creek 53.0
END DESCRIPTION:
XS GIS Cut Line= 4
      1555200.95       788760.16      1555082.57       789151.74
      1554513.35       789570.68      1554335.77       789843.89
#Sta/Elev= 30
  4690.1  685.49  4730.4  682.11  4813.9  672.40  4845.6  666.53  4858.2  665.33
  4873.9  658.82  4909.1  655.96  4963.5  654.62  4968.0  645.62  5032.0  645.62
  5036.5  654.62  5041.8  656.04  5055.7  655.20  5171.2  656.02  5234.4  654.80
  5311.0  655.97  5390.2  654.95  5535.8  655.61  5558.3  654.62  5835.9  655.65
  5850.5  657.23  5866.1  665.07  5881.2  669.31  5897.0  669.59  5912.2  673.12
  5941.2  686.39  5970.3  695.36  5999.5  702.74  6056.2  706.99  6131.8  709.18
#Mann=3,-1,0
  4690.1    0.14       0  4963.5   0.045       0  5036.5    0.14       0
Bank Sta=4963.5,5036.5
XS Rating Curve= 0
Exp/Cntr=0.3,0.1

Type RM Length L Ch R = 1,50885,1209,1209,1209
BEGIN DESCRIPTION:
Dutchman Creek 52.0
END DESCRIPTION:
XS GIS Cut Line= 4
      1555346.53       788538.70      1554608.98       788514.22
      1553880.39       788732.80      1553475.12       788910.39
#Sta/Elev= 30
  4469.6  713.57  4483.8  711.13  4593.8  702.37  4644.4  695.96  4796.0  688.84
  4884.1  673.83  4913.4  666.83  4951.0  662.64  4963.5  654.17  4968.0  645.17
  5032.0  645.17  5036.5  654.17  5051.8  656.31  5078.9  656.57  5144.3  655.10
  5744.3  656.19  5808.3  654.91  5966.3  654.78  6001.8  656.49  6011.3  661.05
  6030.2  664.93  6063.9  659.06  6099.8  659.01  6121.4  661.10  6155.7  667.15
  6197.4  677.82  6224.8  683.09  6243.0  685.08  6378.9  706.85  6410.7  710.67
#Mann=3,-1,0
  4469.6    0.14       0  4963.5   0.045       0  5036.5    0.14       0
Bank Sta=4963.5,5036.5
XS Rating Curve= 0
Exp/Cntr=0.3,0.1

Type RM Length L Ch R = 1,49676,1022,1022,1022
BEGIN DESCRIPTION:
Dutchman Creek 51.0
END DESCRIPTION:
XS GIS Cut Line= 3
      1555240.45       787838.64      1554933.89       787803.46
      1553305.60       788366.33
#Sta/Elev= 30
  4609.1  696.51  4663.5  694.57  4911.1  680.34  4925.1  680.67  4954.3  663.21
  4964.0  658.71  4967.2  653.53  4971.2  644.53  5028.8  644.53  5032.9  653.53
  5036.2  654.58  5080.3  656.74  5122.1  655.81  5567.6  654.39  5788.0  655.54
  5882.9  653.95  5915.7  654.99  6064.6  655.02  6159.9  657.07  6244.2  668.96
  6273.8  668.82  6284.1  670.37  6303.8  676.47  6319.9  688.20  6335.7  692.75
  6398.8  707.28  6453.8  717.93  6532.7  730.72  6595.8  737.06  6640.5  739.46
#Mann=4,-1,0
  4609.1    0.08       0  4911.1    0.14       0  4967.2   0.045       0
  5032.9    0.14       0
Bank Sta=4967.2,5032.9
XS Rating Curve= 0
Exp/Cntr=0.3,0.1

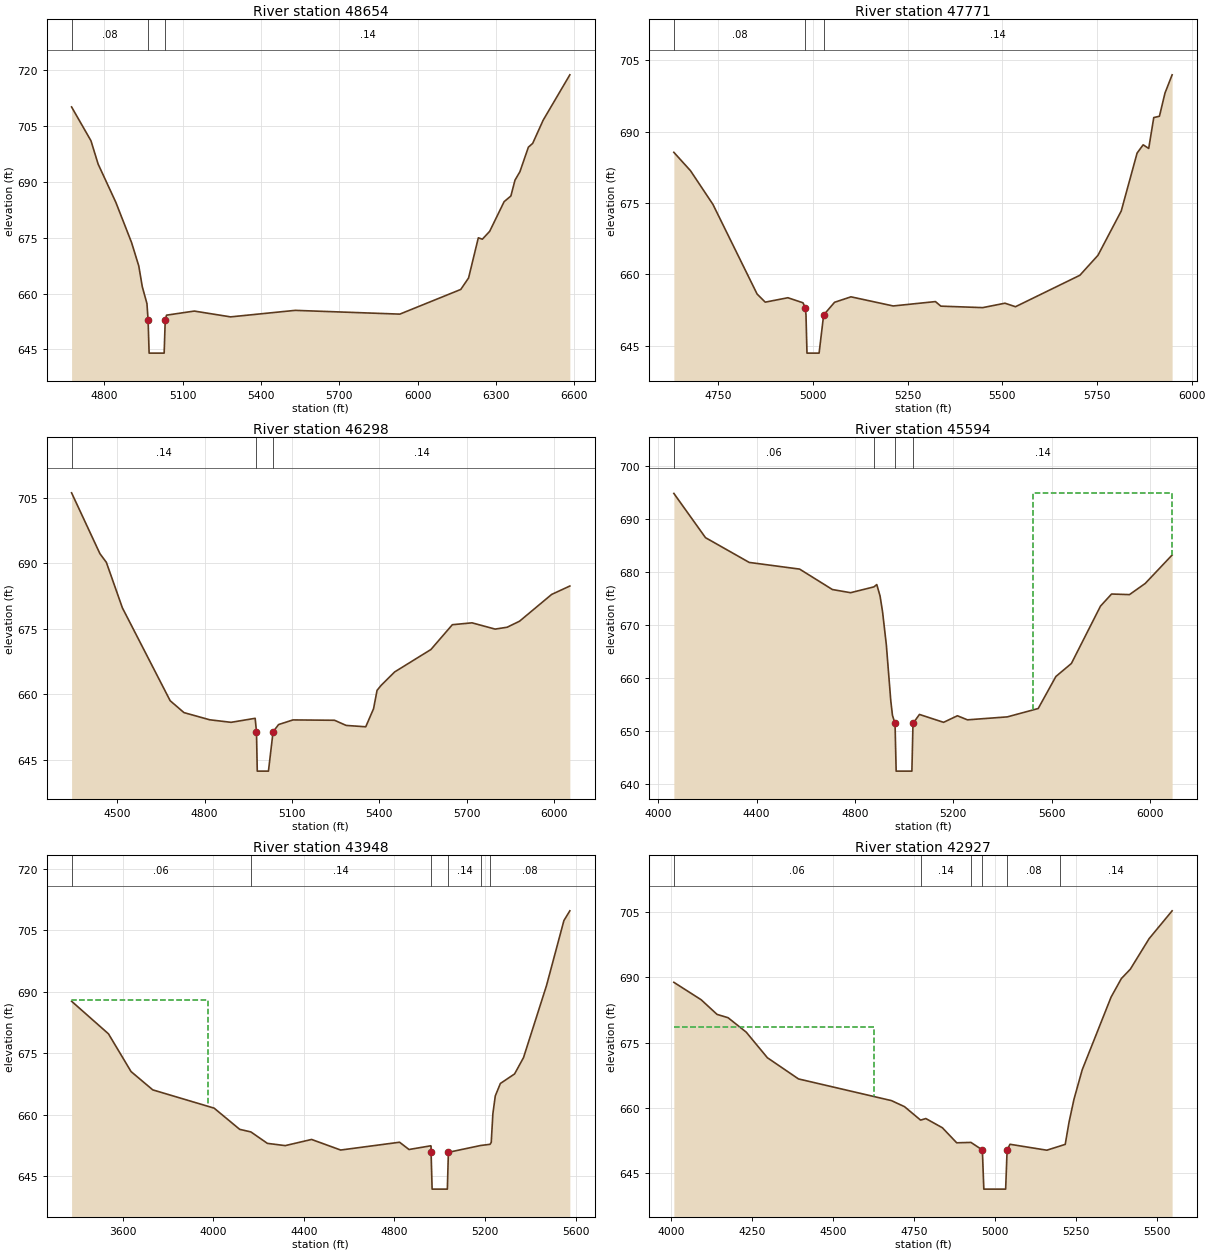
Type RM Length L Ch R = 1,48654,883,883,883
BEGIN DESCRIPTION:
Dutchman Creek 50.0
END DESCRIPTION:
XS GIS Cut Line= 5
      1554841.23       787052.48      1554581.66       787139.00
      1554326.65       787457.76      1553506.98       787840.27
      1553352.18       788122.57
#Sta/Elev= 30
  4674.2  710.14  4748.4  701.06  4775.8  694.81  4843.6  684.53  4904.0  673.70
  4931.6  667.41  4945.0  661.84  4962.8  657.31  4967.2  652.99  4971.2  643.99
  5028.8  643.99  5032.9  652.99  5037.9  654.19  5144.2  655.29  5283.0  653.73
  5530.7  655.48  5931.3  654.47  6164.7  661.10  6194.6  664.18  6232.0  674.98
  6247.4  674.60  6275.4  676.71  6330.8  684.69  6356.7  686.22  6372.4  690.47
  6391.3  692.74  6423.7  699.33  6440.2  700.35  6480.3  706.58  6582.5  718.77
#Mann=3,-1,0
  4674.2    0.08       0  4967.2   0.045       0  5032.9    0.14       0
Bank Sta=4967.2,5032.9
XS Rating Curve= 0
Exp/Cntr=0.3,0.1

Type RM Length L Ch R = 1,47771,1473,1473,1473
BEGIN DESCRIPTION:
Dutchman Creek 49.0
END DESCRIPTION:
XS GIS Cut Line= 4
      1554231.59       786515.98      1554088.90       786600.82
      1553418.04       787078.91      1553132.70       787237.00
#Sta/Elev= 30
  4632.4  685.68  4676.4  681.81  4735.7  674.72  4852.3  655.87  4873.8  654.17
  4933.6  655.10  4973.6  654.03  4979.7  652.90  4981.4  651.47  4984.0  643.45
  5016.0  643.45  5028.0  651.47  5056.8  654.14  5100.2  655.29  5211.7  653.37
  5323.3  654.29  5337.6  653.33  5448.2  653.02  5506.9  653.95  5534.7  653.21
  5704.7  659.82  5752.5  664.02  5814.0  673.34  5855.9  685.52  5871.9  687.26
  5886.6  686.50  5899.9  692.99  5914.9  693.27  5929.5  698.13  5948.4  701.98
#Mann=3,-1,0
  4632.4    0.08       0  4979.7   0.045       0  5028.0    0.14       0
Bank Sta=4979.7,5028
XS Rating Curve= 0
Exp/Cntr=0.3,0.1

Type RM Length L Ch R = 1,46298,704,704,704
BEGIN DESCRIPTION:
Dutchman Creek 48.0
END DESCRIPTION:
XS GIS Cut Line= 5
      1554439.73       786319.35      1554181.44       786222.98
      1553919.26       786153.58      1553162.89       786158.10
      1552755.80       786153.07
#Sta/Elev= 30
  4343.4  706.10  4440.7  692.19  4462.8  690.20  4517.8  679.80  4681.8  658.56
  4729.3  655.84  4817.6  654.20  4890.9  653.62  4973.6  654.54  4978.1  651.46
  4980.8  642.46  5019.2  642.46  5035.1  651.46  5054.0  653.11  5103.4  654.17
  5246.1  654.09  5285.9  652.91  5353.2  652.60  5380.0  656.73  5392.0  660.93
  5406.1  662.08  5452.4  665.14  5576.9  670.27  5650.4  675.94  5718.0  676.37
  5797.2  674.94  5838.4  675.36  5881.1  676.74  5991.2  682.86  6053.8  684.79
#Mann=3,-1,0
  4343.4    0.14       0  4978.1   0.045       0  5035.1    0.14       0
Bank Sta=4978.1,5035.1
XS Rating Curve= 0
Exp/Cntr=0.3,0.1

Type RM Length L Ch R = 1,45594,1646,1646,1646
BEGIN DESCRIPTION:
Dutchman Creek 47.0
END DESCRIPTION:
XS GIS Cut Line= 6
      1554384.13       785004.72      1554112.72       785135.40
      1553786.05       785457.03      1553509.65       785602.77
      1553037.25       786130.46      1552790.98       786135.48
#Sta/Elev= 30
  4063.8  694.89  4192.5  686.53  4370.4  681.85  4575.3  680.59  4708.7  676.73
  4782.6  676.13  4877.6  677.23  4889.2  677.67  4902.5  675.52  4912.7  672.53
  4928.1  666.27  4946.2  655.70  4953.0  652.95  4963.5  651.42  4968.0  642.42
  5032.0  642.42  5036.5  651.42  5062.7  653.13  5160.9  651.64  5217.1  652.88
  5258.0  652.11  5420.4  652.67  5545.8  654.25  5617.7  660.30  5680.8  662.76
  5799.2  673.60  5844.2  675.88  5917.0  675.77  5980.9  677.87  6090.5  683.25
#Mann=4,-1,0
  4063.8    0.06       0  4877.6    0.14       0  4963.5   0.045       0
  5036.5    0.14       0
#XS Ineff=2,0
       0                 5525.00    0.00  695.00
Permanent Ineff=
       F       F
Bank Sta=4963.5,5036.5
XS Rating Curve= 0
Exp/Cntr=0.3,0.1

Type RM Length L Ch R = 1,43948,1021,1021,1021
BEGIN DESCRIPTION:
Dutchman Creek 46.0
END DESCRIPTION:
XS GIS Cut Line= 4
      1554092.65       784772.57      1553544.83       784546.40
      1552308.54       784455.94      1551981.90       784285.08
#Sta/Elev= 30
  3373.8  687.70  3536.9  679.72  3636.5  670.50  3732.5  666.02  4003.3  661.56
  4116.4  656.37  4165.8  655.74  4238.8  652.94  4317.6  652.39  4433.9  653.90
  4562.4  651.31  4822.6  653.22  4864.3  651.44  4960.5  652.35  4961.6  652.25
  4961.8  650.75  4966.3  641.75  5033.7  641.75  5038.2  650.75  5180.5  652.42
  5222.3  652.71  5227.5  653.19  5234.7  660.17  5245.4  664.55  5267.9  667.59
  5330.6  669.92  5370.1  673.92  5471.5  691.51  5548.6  707.45  5574.7  709.81
#Mann=6,-1,0
  3373.8    0.06       0  4165.8    0.14       0  4961.8   0.045       0
  5038.2    0.14       0  5180.5    0.14       0  5222.3    0.08       0
#XS Ineff=2,0
    0.00 3975.00  688.00               0
Permanent Ineff=
       F       F
Bank Sta=4961.8,5038.2
XS Rating Curve= 0
Exp/Cntr=0.3,0.1

Type RM Length L Ch R = 1,42927,637,637,637
BEGIN DESCRIPTION:
Dutchman Creek 45.0
END DESCRIPTION:
XS GIS Cut Line= 4
      1554128.28       784767.52      1553439.79       784486.09
      1553253.85       784047.87      1553103.09       783767.45
#Sta/Elev= 30
  4009.4  688.83  4093.6  684.83  4142.8  681.46  4176.8  680.70  4232.9  677.38
  4298.1  671.51  4394.2  666.64  4681.2  661.66  4721.5  660.27  4771.1  657.18
  4787.3  657.54  4838.3  655.43  4882.6  651.97  4926.5  652.06  4961.8  650.33
  4966.3  641.33  5033.7  641.33  5038.2  650.33  5047.1  651.63  5160.8  650.27
  5201.2  651.22  5217.6  651.61  5229.2  656.65  5244.5  661.94  5269.9  668.71
  5359.3  685.46  5390.7  689.67  5418.6  691.85  5476.6  698.86  5547.6  705.25
#Mann=6,-1,0
  4009.4    0.06       0  4771.1    0.14       0  4926.5    0.08       0
  4961.8   0.045       0  5038.2    0.08       0  5201.2    0.14       0
#XS Ineff=2,0
    0.00 4628.60  678.54               0
Permanent Ineff=
       F       F
Bank Sta=4961.8,5038.2
XS Rating Curve= 0
Exp/Cntr=0.3,0.1

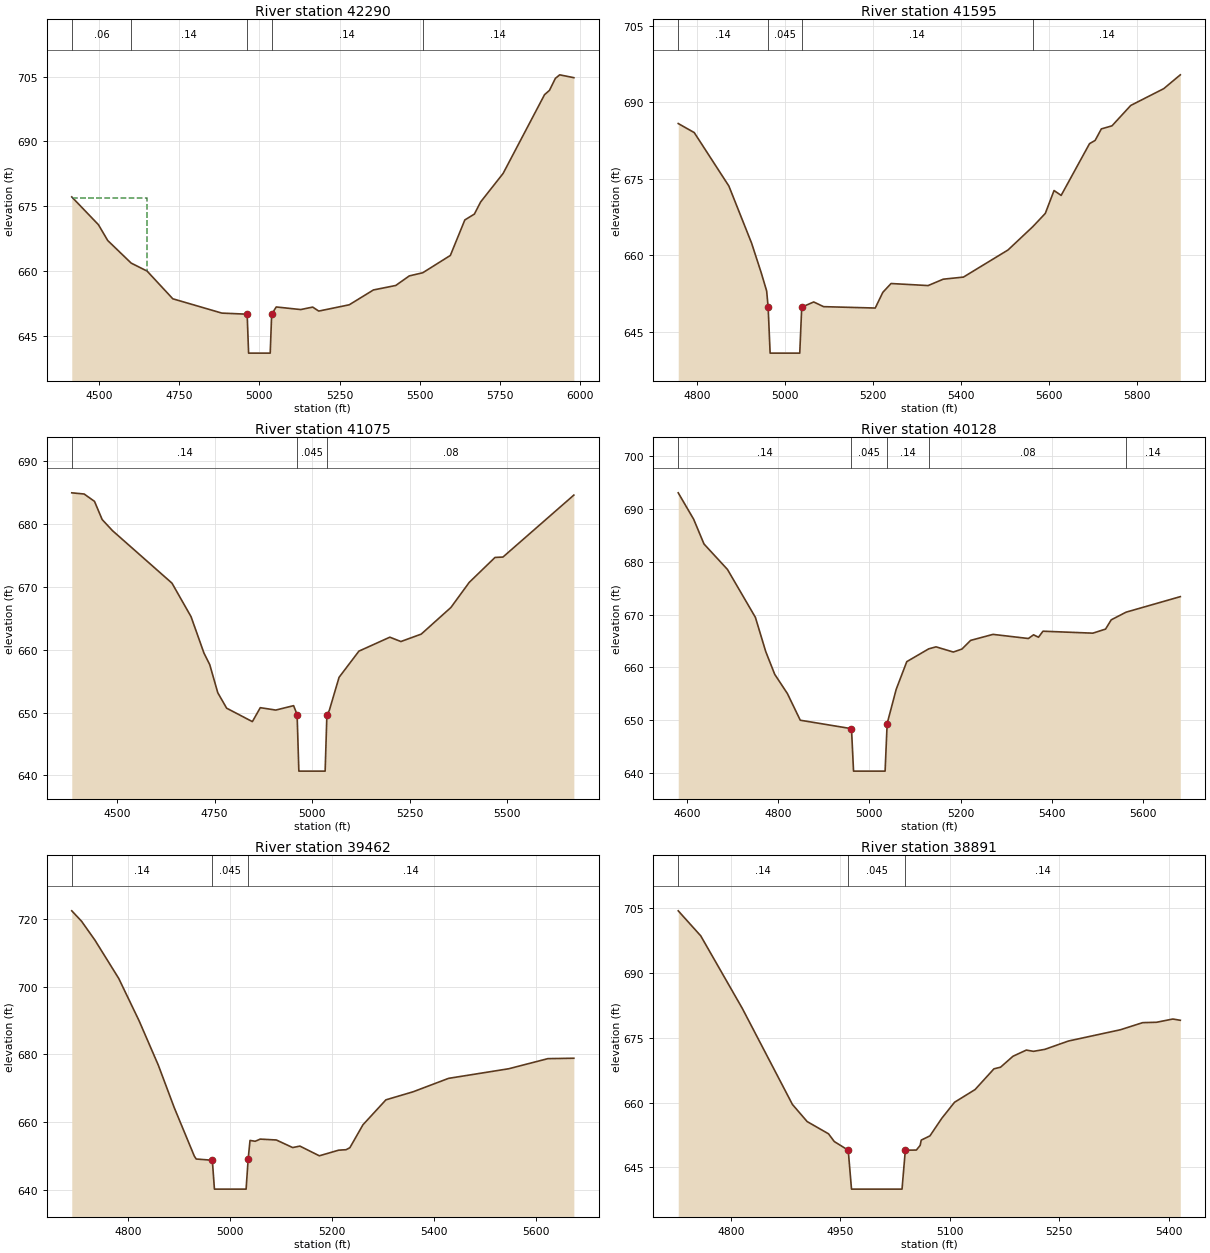
Type RM Length L Ch R = 1,42290,695,695,695
BEGIN DESCRIPTION:
Dutchman Creek 44.0
END DESCRIPTION:
XS GIS Cut Line= 5
      1554074.37       784597.11      1553968.73       784251.04
      1553797.51       784017.89      1553502.43       783653.59
      1553068.88       783551.58
#Sta/Elev= 30
  4415.0  677.18  4498.1  670.76  4527.1  667.10  4600.2  661.88  4649.8  660.04
  4730.0  653.63  4883.0  650.32  4961.8  650.07  4966.3  641.07  5033.7  641.07
  5038.2  650.07  5052.5  651.74  5128.8  651.14  5166.1  651.71  5185.0  650.79
  5280.0  652.24  5355.4  655.67  5425.1  656.71  5467.3  658.92  5509.3  659.65
  5595.3  663.65  5640.4  671.85  5670.2  673.21  5689.7  676.01  5759.9  682.62
  5888.9  700.81  5904.3  701.81  5922.7  704.58  5936.2  705.40  5980.3  704.74
#Mann=5,-1,0
  4415.0    0.06       0  4600.2    0.14       0  4961.8   0.045       0
  5038.2    0.14       0  5509.3    0.14       0
#XS Ineff=2,0
    0.00 4650.00  677.00               0
Permanent Ineff=
       F       F
Bank Sta=4961.8,5038.2
XS Rating Curve= 0
Exp/Cntr=0.3,0.1

Type RM Length L Ch R = 1,41595,520,520,520
BEGIN DESCRIPTION:
Dutchman Creek 43.0
END DESCRIPTION:
XS GIS Cut Line= 4
      1554589.49       783856.14      1554405.89       783730.83
      1554038.68       783433.56      1553779.27       783069.22
#Sta/Elev= 30
  4757.3  685.81  4793.7  684.04  4872.5  673.57  4924.2  662.38  4945.9  656.63
  4958.4  653.03  4961.8  649.85  4966.3  640.85  5033.7  640.85  5038.2  649.85
  5065.5  650.87  5087.9  649.95  5205.4  649.68  5222.7  652.76  5241.4  654.48
  5325.7  654.08  5360.1  655.33  5406.0  655.74  5507.4  661.05  5564.2  665.65
  5592.2  668.21  5612.1  672.69  5628.3  671.74  5692.8  681.87  5705.5  682.50
  5719.7  684.76  5743.9  685.36  5786.5  689.35  5861.6  692.64  5899.3  695.35
#Mann=4,-1,0
  4757.3    0.14       0  4961.8   0.045       0  5038.2    0.14       0
  5564.2    0.14       0
Bank Sta=4961.8,5038.2
XS Rating Curve= 0
Exp/Cntr=0.3,0.1

Type RM Length L Ch R = 1,41075,947,947,947
BEGIN DESCRIPTION:
Dutchman Creek 42.0
END DESCRIPTION:
XS GIS Cut Line= 3
      1554857.01       783734.79      1554671.05       783377.96
      1554057.94       782739.72
#Sta/Elev= 30
  4384.0  684.98  4415.8  684.79  4442.3  683.62  4462.0  680.72  4488.4  678.96
  4641.0  670.60  4689.9  665.26  4722.9  659.48  4737.8  657.63  4758.4  653.16
  4781.1  650.70  4847.1  648.56  4867.4  650.78  4907.1  650.40  4952.8  651.10
  4961.8  649.68  4966.3  640.68  5033.7  640.68  5038.2  649.68  5044.3  650.33
  5069.4  655.61  5120.3  659.78  5199.6  662.00  5227.9  661.31  5280.1  662.49
  5356.2  666.73  5403.1  670.72  5469.2  674.69  5489.7  674.76  5671.4  684.62
#Mann=3,-1,0
  4384.0    0.14       0  4961.8   0.045       0  5038.2    0.08       0
Bank Sta=4961.8,5038.2
XS Rating Curve= 0
Exp/Cntr=0.3,0.1

Type RM Length L Ch R = 1,40128,666,666,666
BEGIN DESCRIPTION:
Dutchman Creek 41.0
END DESCRIPTION:
XS GIS Cut Line= 4
      1555351.98       783471.91      1555145.97       783356.35
      1555120.84       782848.77      1555251.50       782517.09
#Sta/Elev= 30
  4581.0  693.03  4614.9  688.02  4637.5  683.35  4688.9  678.54  4750.2  669.47
  4772.9  662.99  4792.6  658.69  4820.4  655.05  4848.6  650.01  4960.9  648.41
  4965.4  640.38  5034.6  640.38  5039.1  649.38  5058.9  655.85  5082.1  661.09
  5130.2  663.51  5146.3  663.89  5184.2  662.91  5203.0  663.47  5222.1  665.11
  5271.1  666.25  5348.8  665.47  5360.1  666.17  5370.9  665.71  5380.8  666.85
  5490.1  666.48  5518.0  667.25  5530.4  669.00  5562.9  670.45  5681.9  673.39
#Mann=5,-1,0
  4581.0    0.14       0  4960.9   0.045       0  5039.1    0.14       0
  5130.2    0.08       0  5562.9    0.14       0
Bank Sta=4960.9,5039.1
XS Rating Curve= 0
Exp/Cntr=0.3,0.1

Type RM Length L Ch R = 1,39462,571,571,571
BEGIN DESCRIPTION:
Dutchman Creek 40.0
END DESCRIPTION:
XS GIS Cut Line= 4
      1555892.23       783421.92      1555793.13       783217.90
      1555749.41       782935.20      1555495.89       782535.97
#Sta/Elev= 30
  4688.8  722.51  4707.9  719.45  4734.3  713.83  4781.0  702.51  4821.0  689.97
  4858.8  676.82  4890.0  664.27  4929.4  649.94  4933.2  649.07  4964.8  648.70
  4968.9  640.16  5031.1  640.16  5035.2  649.16  5038.8  654.57  5048.9  654.32
  5058.8  654.96  5090.5  654.70  5122.5  652.46  5136.7  652.89  5174.9  650.02
  5212.9  651.69  5227.3  651.82  5234.8  652.41  5260.5  659.19  5305.6  666.58
  5359.1  668.97  5428.7  672.94  5546.8  675.78  5623.6  678.77  5674.6  678.89
#Mann=3,-1,0
  4688.8    0.14       0  4964.8   0.045       0  5035.2    0.14       0
Bank Sta=4964.8,5035.2
XS Rating Curve= 0
Exp/Cntr=0.3,0.1

Type RM Length L Ch R = 1,38891,770,770,770
BEGIN DESCRIPTION:
Dutchman Creek 39.0
END DESCRIPTION:
XS GIS Cut Line= 3
      1556191.33       782698.01      1555754.06       782632.67
      1555527.92       782537.19
#Sta/Elev= 30
  4728.1  704.31  4758.9  698.53  4815.9  681.74  4884.5  659.55  4904.7  655.59
  4933.9  652.77  4941.8  650.98  4960.9  648.98  4965.4  639.98  5034.6  639.98
  5039.1  648.98  5054.2  649.01  5059.4  650.09  5060.9  651.31  5072.8  652.29
  5089.0  656.34  5106.5  660.06  5134.6  662.99  5160.5  667.79  5169.5  668.16
  5186.6  670.70  5204.8  672.12  5214.6  671.83  5230.2  672.29  5262.4  674.21
  5333.7  676.82  5364.1  678.46  5383.2  678.55  5405.5  679.30  5415.7  679.01
#Mann=3,-1,0
  4728.1    0.14       0  4960.9   0.045       0  5039.1    0.14       0
Bank Sta=4960.9,5039.1
XS Rating Curve= 0
Exp/Cntr=0.3,0.1

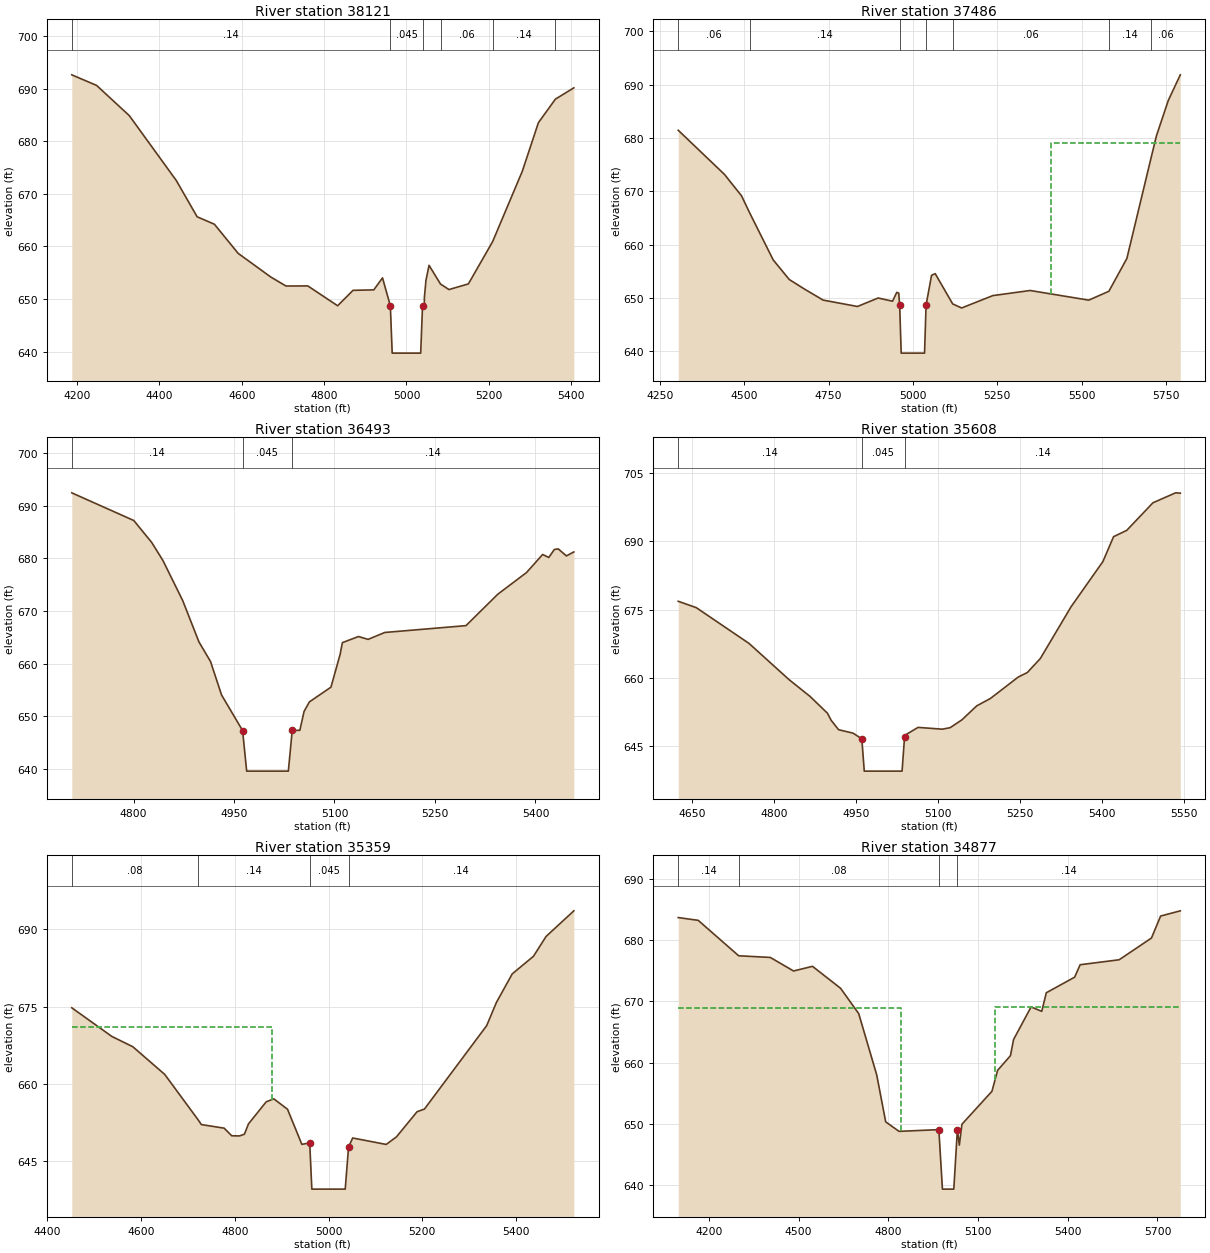
Type RM Length L Ch R = 1,38121,635,635,635
BEGIN DESCRIPTION:
Dutchman Creek 38.0
END DESCRIPTION:
XS GIS Cut Line= 4
      1556744.10       782183.39      1556316.92       781917.03
      1555844.52       781881.85      1555603.28       781901.96
#Sta/Elev= 30
  4187.3  692.61  4247.6  690.60  4327.1  684.85  4441.2  672.52  4491.7  665.64
  4533.7  664.22  4591.3  658.69  4670.6  654.19  4707.6  652.48  4760.5  652.50
  4832.9  648.73  4870.2  651.66  4920.7  651.75  4941.9  654.03  4960.9  648.73
  4965.4  639.73  5034.6  639.73  5039.1  648.73  5043.3  648.80  5043.6  650.33
  5047.4  653.56  5054.9  656.41  5082.7  652.86  5103.2  651.81  5150.4  652.88
  5209.3  660.92  5281.4  674.30  5320.4  683.51  5361.7  687.99  5406.5  690.14
#Mann=6,-1,0
  4187.3    0.14       0  4960.9   0.045       0  5039.1    0.14       0
  5082.7    0.06       0  5209.3    0.14       0  5361.7    0.06       0
Bank Sta=4960.9,5039.1
XS Rating Curve= 0
Exp/Cntr=0.3,0.1

Type RM Length L Ch R = 1,37486,993,993,993
BEGIN DESCRIPTION:
Dutchman Creek 37.0
END DESCRIPTION:
XS GIS Cut Line= 3
      1556967.67       781326.46      1556580.01       781381.84
      1555498.80       781201.15
#Sta/Elev= 30
  4304.7  681.47  4441.7  673.19  4492.4  669.16  4516.0  666.02  4586.1  657.15
  4633.7  653.47  4680.8  651.60  4734.1  649.61  4835.8  648.41  4897.1  650.00
  4939.8  649.40  4952.3  651.06  4958.1  650.92  4960.9  648.66  4965.4  639.66
  5034.6  639.66  5039.1  648.66  5055.4  654.26  5066.2  654.57  5118.0  648.89
  5144.5  648.13  5236.8  650.45  5347.4  651.41  5521.2  649.60  5580.8  651.26
  5634.1  657.41  5704.6  675.96  5721.7  680.41  5756.8  687.05  5792.5  691.87
#Mann=7,-1,0
  4304.7    0.06       0  4516.0    0.14       0  4960.9   0.045       0
  5039.1    0.14       0  5118.0    0.06       0  5580.8    0.14       0
  5704.6    0.06       0
#XS Ineff=2,0
       0                 5410.10    0.00  679.08
Permanent Ineff=
       F       F
Bank Sta=4960.9,5039.1
XS Rating Curve= 0
Exp/Cntr=0.3,0.1

Type RM Length L Ch R = 1,36493,885,885,885
BEGIN DESCRIPTION:
Dutchman Creek 36.0
END DESCRIPTION:
XS GIS Cut Line= 3
      1556367.20       780327.44      1555969.44       780487.86
      1555649.41       780507.14
#Sta/Elev= 30
  4707.8  692.43  4800.4  687.17  4827.1  683.01  4843.9  679.57  4873.5  671.94
  4897.6  664.12  4915.0  660.37  4931.4  654.03  4962.8  647.27  4968.9  639.56
  5031.1  639.56  5036.9  647.28  5048.3  647.32  5054.6  650.91  5062.5  652.71
  5094.7  655.51  5108.3  661.69  5111.8  663.97  5135.8  665.13  5150.2  664.59
  5175.0  665.90  5296.3  667.20  5343.7  673.16  5386.7  677.29  5410.7  680.72
  5419.9  680.15  5428.2  681.67  5434.1  681.77  5446.2  680.45  5457.3  681.20
#Mann=3,-1,0
  4707.8    0.14       0  4962.8   0.045       0  5036.9    0.14       0
Bank Sta=4962.8,5036.9
XS Rating Curve= 0
Exp/Cntr=0.3,0.1

Type RM Length L Ch R = 1,35608,249,249,249
BEGIN DESCRIPTION:
Dutchman Creek 35.0
END DESCRIPTION:
XS GIS Cut Line= 4
      1556042.94       779765.53      1555834.65       779603.53
      1555502.88       779726.97      1555209.65       779796.42
#Sta/Elev= 30
  4624.8  676.84  4657.8  675.44  4754.5  667.56  4827.8  659.59  4866.1  655.91
  4898.0  652.21  4904.8  650.65  4918.4  648.58  4944.8  647.83  4960.9  646.58
  4965.4  639.47  5034.6  639.47  5039.1  646.92  5043.1  647.60  5063.8  649.09
  5108.4  648.70  5122.6  649.03  5144.0  650.74  5171.3  653.83  5196.4  655.46
  5247.4  660.18  5263.9  661.16  5287.7  664.24  5344.2  675.67  5402.3  685.58
  5421.8  691.05  5446.0  692.45  5493.9  698.51  5535.4  700.70  5544.0  700.63
#Mann=3,-1,0
  4624.8    0.14       0  4960.9   0.045       0  5039.1    0.14       0
Bank Sta=4960.9,5039.1
XS Rating Curve= 0
Exp/Cntr=0.3,0.1

Type RM Length L Ch R = 1,35359,482,482,482
BEGIN DESCRIPTION:
Dutchman Creek 34.0
END DESCRIPTION:
XS GIS Cut Line= 3
      1555919.86       778957.44      1555748.97       779350.36
      1555189.96       779666.32
#Sta/Elev= 30
  4452.5  674.75  4538.0  669.17  4582.8  667.16  4650.8  661.77  4721.2  653.03
  4728.9  652.01  4777.5  651.31  4793.5  649.83  4810.4  649.80  4820.7  650.14
  4829.3  652.14  4867.1  656.44  4883.4  657.02  4912.6  654.99  4943.1  648.16
  4959.9  648.44  4964.4  639.44  5035.6  639.44  5042.7  647.62  5051.5  649.40
  5123.0  648.14  5145.0  649.63  5188.8  654.51  5204.5  655.03  5337.2  671.27
  5358.1  675.81  5391.8  681.36  5437.0  684.78  5463.9  688.64  5523.1  693.63
#Mann=4,-1,0
  4452.5    0.08       0  4721.2    0.14       0  4959.9   0.045       0
  5042.7    0.14       0
#XS Ineff=2,0
    0.00 4879.40  671.07               0
Permanent Ineff=
       F       F
Bank Sta=4959.9,5042.7
XS Rating Curve= 0
Exp/Cntr=0.5,0.3

Type RM Length L Ch R = 1,34877,154,154,154
BEGIN DESCRIPTION:
US 64 (DC) us
END DESCRIPTION:
XS GIS Cut Line= 5
      1556214.80       778891.63      1556028.34       778875.83
      1555450.02       779033.84      1555127.67       779097.04
      1554584.13       779245.57
#Sta/Elev= 30
  4097.7  683.67  4164.4  683.22  4299.8  677.44  4405.5  677.17  4483.2  674.96
  4546.6  675.72  4640.5  672.14  4701.2  668.00  4761.3  658.02  4791.3  650.36
  4836.0  648.81  4969.0  649.09  4981.0  639.39  5019.0  639.39  5031.0  649.09
  5037.5  646.57  5046.2  649.97  5146.5  655.34  5165.5  658.76  5208.4  661.15
  5218.8  663.78  5277.4  669.10  5313.0  668.38  5328.3  671.41  5423.0  673.95
  5441.4  675.98  5571.9  676.79  5679.8  680.33  5710.5  683.92  5776.3  684.77
#Mann=4,-1,0
  4097.7    0.14       0  4299.8    0.08       0  4969.0   0.045       0
  5031.0    0.14       0
#XS Ineff=2,0
    0.00 4843.50  668.89 5156.50    0.00  669.04
Permanent Ineff=
       F       F
Bank Sta=4969,5031
XS Rating Curve= 0
Exp/Cntr=0.5,0.3