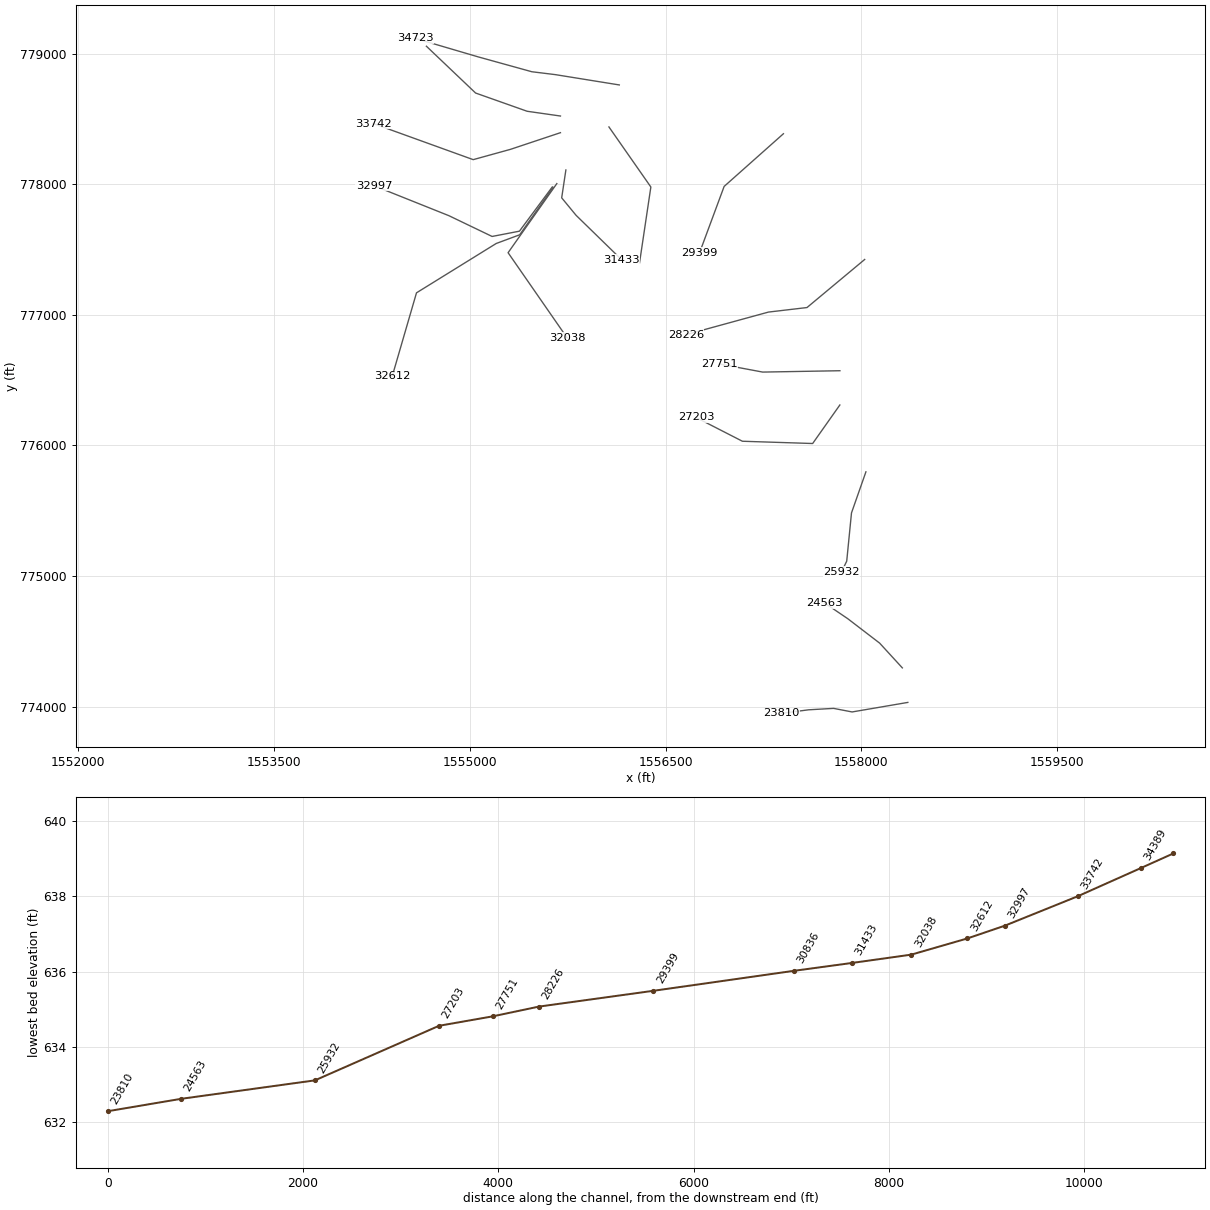
HEC-RAS study Dutchman Creek.prj: Dutchman Creek Limited Detail Study

--- Dutchman Creek.g01 (geometry) --- (continued)

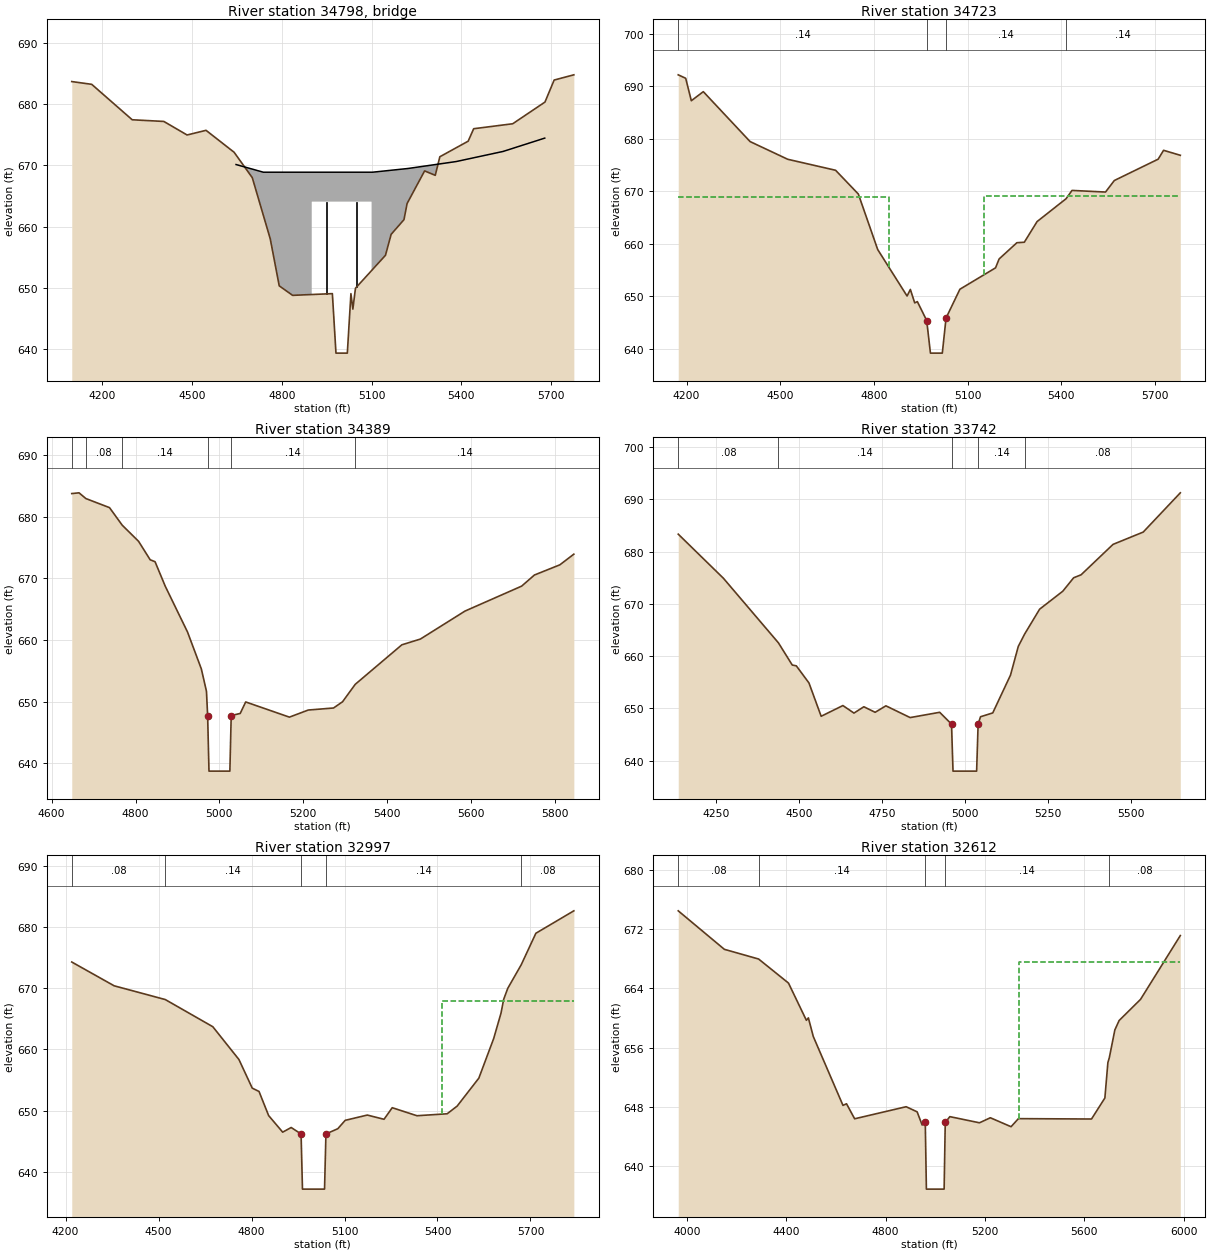
Type RM Length L Ch R =3,34798,,,
BEGIN DESCRIPTION:
US 64 (DC) tor
Structure ID: LDS_DC_02
Approximate Survey Structure
END DESCRIPTION:
Bridge Culvert--1,0,-1,-1,0
Deck Dist Width WeirC Skew NumUp NumDn MinLoCord MaxHiCord MaxSubmerge Is_Ogee
56.5,45,3,,11,11,,,0.95,0,1,1,,,
  4647.0  4738.3  4900.0  4900.0  5100.0  5100.0  5103.0  5222.1  5383.0  5540.0
  5679.0
  670.14  668.89  668.89  668.89  668.89  668.89  668.89  669.50  670.63  672.28
  674.45
  619.39  619.39  619.39  664.09  664.09  619.39  619.39  619.39  619.39  619.39
  619.39
  4647.0  4738.3  4900.0  4900.0  5100.0  5100.0  5103.0  5222.1  5383.0  5540.0
  5679.0
  670.14  668.89  668.89  668.89  668.89  668.89  668.89  669.50  670.63  672.28
  674.45
  619.39  619.39  619.39  664.09  664.09  619.39  619.39  619.39  619.39  619.39
  619.39
Pier Skew, UpSta & Num, DnSta & Num=,4950,2,4950,2,0,0,0,0,0
     3.5     3.5
  648.59  664.09
     3.5     3.5
  647.07  664.09
Pier Skew, UpSta & Num, DnSta & Num=,5050,2,5050,2,0,0,0,0,0
     3.5     3.5
  650.19  664.09
     3.5     3.5
  648.82  664.09
Abutment Skew #Up #Dn=,2,2
  4900.0  4902.0
  664.09  649.18
  4900.0  4902.0
  664.09  650.51
Abutment Skew #Up #Dn=,2,2
  5098.0  5100.0
  652.34  664.09
  5098.0  5100.0
  651.39  664.09
BR Coef=1,1,0,1.25,0,,,0.8,0,2,0,
WSPro=,,,, 1 ,,,, 0 ,,,, 0 ,,,,-1 ,-1 ,-1 , 0 , 0 , 0 , 0 , 0
BC Design=,,0,,0,,,,,,

Type RM Length L Ch R = 1,34723,334,334,334
BEGIN DESCRIPTION:
US 64 (DC) ds
END DESCRIPTION:
XS GIS Cut Line= 5
      1556145.24       778762.06      1555655.43       778841.06
      1555475.30       778863.18      1555064.47       778976.95
      1554580.97       779119.16
#Sta/Elev= 30
  4173.3  692.20  4197.2  691.54  4215.2  687.26  4253.6  688.99  4403.5  679.47
  4523.9  676.10  4677.3  674.00  4750.1  669.47  4812.1  658.89  4906.1  650.03
  4916.7  651.28  4930.6  648.72  4939.1  648.96  4969.0  645.36  4981.0  639.14
  5019.0  639.14  5031.0  645.83  5075.3  651.32  5189.5  655.40  5200.9  657.09
  5257.8  660.19  5281.6  660.28  5322.5  664.22  5415.4  668.58  5434.4  670.16
  5541.7  669.85  5569.9  672.05  5710.3  676.12  5727.6  677.81  5781.2  676.86
#Mann=4,-1,0
  4173.3    0.14       0  4969.0   0.045       0  5031.0    0.14       0
  5415.4    0.14       0
#XS Ineff=2,0
    0.00 4847.50  668.89 5152.50    0.00  669.09
Permanent Ineff=
       F       F
Bank Sta=4969,5031
XS Rating Curve= 0
Exp/Cntr=0.5,0.3

Type RM Length L Ch R = 1,34389,647,647,647
BEGIN DESCRIPTION:
Dutchman Creek 33.0
END DESCRIPTION:
XS GIS Cut Line= 4
      1555694.32       778523.97      1555439.07       778560.43
      1555044.10       778700.19      1554667.34       779058.72
#Sta/Elev= 30
  4648.0  683.73  4665.3  683.85  4681.7  682.92  4738.0  681.45  4768.2  678.61
  4807.3  675.99  4834.9  673.00  4846.5  672.69  4870.9  668.71  4923.9  661.30
  4956.9  655.31  4969.1  651.69  4971.9  647.75  4975.1  638.75  5024.9  638.75
  5028.1  647.75  5049.6  648.10  5062.6  649.96  5166.8  647.50  5211.8  648.65
  5272.0  648.98  5293.5  649.99  5323.8  652.82  5434.9  659.22  5479.0  660.15
  5585.5  664.69  5720.5  668.73  5750.9  670.53  5811.5  672.18  5844.9  673.91
#Mann=6,-1,0
  4648.0    0.14       0  4681.7    0.08       0  4768.2    0.14       0
  4971.9   0.045       0  5028.1    0.14       0  5323.8    0.14       0
Bank Sta=4971.9,5028.1
XS Rating Curve= 0
Exp/Cntr=0.3,0.1

Type RM Length L Ch R = 1,33742,745,745,745
BEGIN DESCRIPTION:
Dutchman Creek 32.0
END DESCRIPTION:
XS GIS Cut Line= 5
      1555694.23       778396.35      1555311.47       778268.76
      1555025.88       778189.77      1554756.82       778286.98
      1554260.11       778466.43
#Sta/Elev= 30
  4135.8  683.36  4272.0  674.92  4438.0  662.55  4479.6  658.31  4491.9  658.15
  4530.0  654.88  4566.8  648.50  4632.3  650.55  4665.8  649.11  4695.5  650.32
  4729.6  649.26  4762.0  650.50  4835.1  648.25  4924.2  649.26  4959.9  647.00
  4964.4  638.00  5035.6  638.00  5040.1  647.00  5047.4  648.41  5084.2  649.14
  5137.7  656.37  5161.2  661.87  5180.4  664.24  5225.6  669.00  5295.3  672.43
  5328.2  675.01  5350.6  675.58  5446.9  681.40  5538.0  683.76  5649.8  691.27
#Mann=5,-1,0
  4135.8    0.08       0  4438.0    0.14       0  4959.9   0.045       0
  5040.1    0.14       0  5180.4    0.08       0
Bank Sta=4959.9,5040.1
XS Rating Curve= 0
Exp/Cntr=0.3,0.1

Type RM Length L Ch R = 1,32997,385,385,385
BEGIN DESCRIPTION:
Dutchman Creek 31.0
END DESCRIPTION:
XS GIS Cut Line= 5
      1555631.68       777980.33      1555379.93       777641.77
      1555170.59       777601.34      1554839.45       777760.54
      1554266.34       777989.78
#Sta/Elev= 30
  4220.1  674.26  4356.9  670.38  4521.7  668.14  4675.1  663.71  4759.4  658.36
  4802.4  653.69  4824.2  653.15  4855.2  649.22  4900.6  646.51  4927.9  647.27
  4959.9  646.22  4964.4  637.22  5035.6  637.22  5040.1  646.22  5078.3  647.07
  5102.3  648.44  5173.6  649.30  5227.5  648.61  5254.0  650.50  5333.7  649.19
  5431.2  649.51  5463.4  650.76  5533.4  655.32  5581.2  661.77  5604.8  665.90
  5613.6  668.18  5626.8  669.98  5670.2  673.82  5717.4  678.95  5839.9  682.61
#Mann=5,-1,0
  4220.1    0.08       0  4521.7    0.14       0  4959.9   0.045       0
  5040.1    0.14       0  5670.2    0.08       0
#XS Ineff=2,0
       0                 5415.00    0.00  667.92
Permanent Ineff=
       F       F
Bank Sta=4959.9,5040.1
XS Rating Curve= 0
Exp/Cntr=0.3,0.1

Type RM Length L Ch R = 1,32612,574,574,574
BEGIN DESCRIPTION:
Dutchman Creek 30.0
END DESCRIPTION:
XS GIS Cut Line= 5
      1555637.97       777977.63      1555382.12       777614.21
      1555201.88       777547.35      1554591.37       777169.41
      1554405.31       776529.83
#Sta/Elev= 30
  3965.5  674.47  4151.1  669.27  4289.0  667.96  4409.3  664.71  4481.3  659.68
  4489.3  660.01  4509.1  657.49  4628.6  648.19  4642.8  648.41  4675.5  646.38
  4882.8  648.01  4927.0  647.32  4947.3  645.54  4959.8  645.88  4964.3  636.88
  5035.7  636.88  5040.2  645.88  5058.7  646.67  5178.0  645.84  5221.7  646.52
  5305.1  645.31  5334.6  646.40  5628.9  646.35  5682.7  649.19  5694.8  653.97
  5700.5  654.62  5722.9  658.39  5740.0  659.65  5826.2  662.51  5986.3  671.13
#Mann=5,-1,0
  3965.5    0.08       0  4289.0    0.14       0  4959.8   0.045       0
  5040.2    0.14       0  5700.5    0.08       0
#XS Ineff=2,0
       0                 5337.30    0.00  667.54
Permanent Ineff=
       F       F
Bank Sta=4959.8,5040.2
XS Rating Curve= 0
Exp/Cntr=0.3,0.1

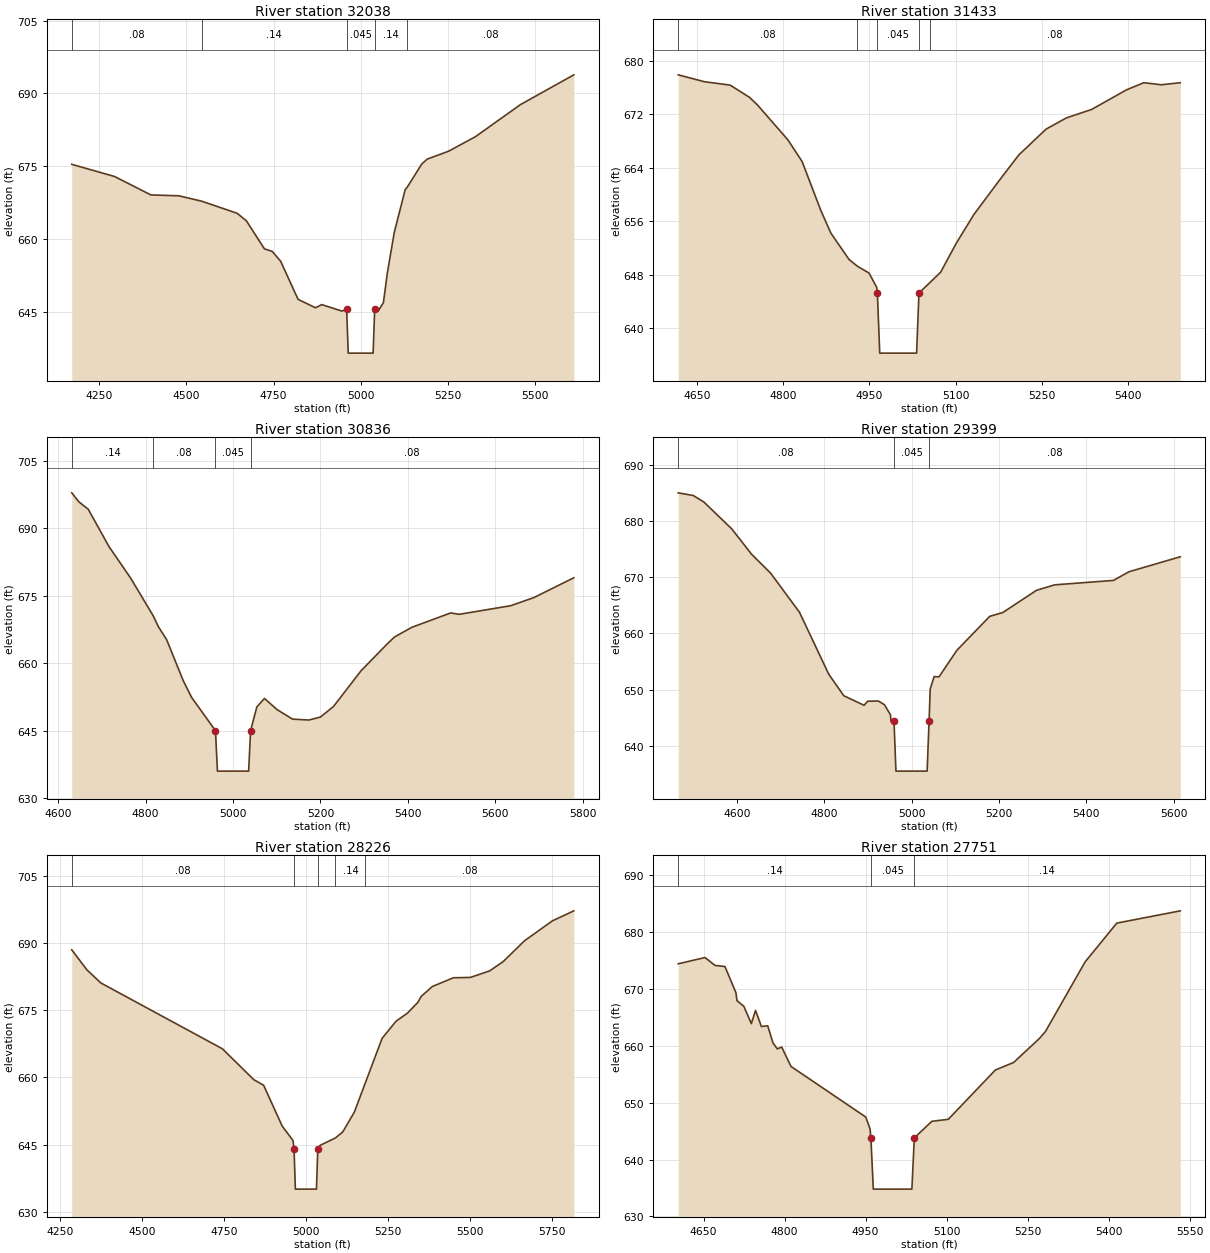
Type RM Length L Ch R = 1,32038,605,605,605
BEGIN DESCRIPTION:
Dutchman Creek 29.0
END DESCRIPTION:
XS GIS Cut Line= 3
      1555666.37       778006.32      1555293.12       777476.84
      1555744.50       776825.82
#Sta/Elev= 30
  4171.4  675.39  4294.2  672.88  4398.2  669.08  4478.5  668.90  4543.9  667.79
  4645.9  665.29  4672.3  663.73  4724.0  657.96  4746.5  657.42  4770.4  655.41
  4820.5  647.54  4870.6  645.80  4888.3  646.46  4945.9  645.13  4959.8  645.45
  4964.3  636.45  5035.7  636.45  5040.2  645.45  5050.2  645.13  5065.2  646.86
  5076.6  653.03  5096.3  661.31  5127.6  670.15  5134.1  670.74  5175.0  675.43
  5190.9  676.47  5251.7  678.08  5329.2  681.09  5458.1  687.70  5611.4  693.85
#Mann=5,-1,0
  4171.4    0.08       0  4543.9    0.14       0  4959.8   0.045       0
  5040.2    0.14       0  5134.1    0.08       0
Bank Sta=4959.8,5040.2
XS Rating Curve= 0
Exp/Cntr=0.3,0.1

Type RM Length L Ch R = 1,31433,597,597,597
BEGIN DESCRIPTION:
Dutchman Creek 28.0
END DESCRIPTION:
XS GIS Cut Line= 4
      1555735.84       778110.54      1555703.72       777897.19
      1555813.96       777763.30      1556161.15       777424.78
#Sta/Elev= 30
  4617.1  677.93  4662.4  676.90  4707.4  676.39  4741.3  674.55  4754.9  673.43
  4808.0  668.19  4832.9  664.92  4865.2  657.64  4882.8  654.22  4914.5  650.26
  4929.0  649.25  4949.3  648.23  4962.6  646.09  4963.8  645.23  4967.9  636.23
  5032.1  636.23  5036.2  645.23  5055.2  646.80  5073.9  648.35  5101.3  652.72
  5131.6  656.97  5175.7  662.07  5210.0  665.92  5257.4  669.79  5292.8  671.47
  5337.0  672.75  5397.3  675.67  5427.7  676.75  5458.0  676.44  5491.2  676.75
#Mann=5,-1,0
  4617.1    0.08       0  4929.0    0.14       0  4963.8   0.045       0
  5036.2    0.14       0  5055.2    0.08       0
Bank Sta=4963.8,5036.2
XS Rating Curve= 0
Exp/Cntr=0.3,0.1

Type RM Length L Ch R = 1,30836,1437,1437,1437
BEGIN DESCRIPTION:
Dutchman Creek 27.0
END DESCRIPTION:
XS GIS Cut Line= 3
      1556065.71       778440.36      1556386.87       777980.31
      1556300.07       777398.71
#Sta/Elev= 30
  4630.9  697.89  4647.4  695.87  4668.6  694.24  4716.5  685.87  4765.1  679.02
  4816.9  670.62  4829.2  668.12  4847.9  665.28  4885.7  656.21  4905.1  652.42
  4959.8  645.02  4964.3  636.02  5035.7  636.02  5040.2  645.02  5054.4  650.28
  5071.9  652.18  5100.9  649.69  5136.2  647.58  5173.7  647.38  5200.0  648.04
  5229.9  650.39  5293.0  658.33  5351.8  664.19  5369.4  665.83  5409.4  668.00
  5498.2  671.19  5517.6  670.88  5635.4  672.79  5689.0  674.62  5780.0  679.01
#Mann=4,-1,0
  4630.9    0.14       0  4816.9    0.08       0  4959.8   0.045       0
  5040.2    0.08       0
Bank Sta=4959.8,5040.2
XS Rating Curve= 0
Exp/Cntr=0.3,0.1

Type RM Length L Ch R = 1,29399,1173,1173,1173
BEGIN DESCRIPTION:
Dutchman Creek 26.0
END DESCRIPTION:
XS GIS Cut Line= 3
      1557402.53       778388.32      1556948.28       777984.58
      1556760.15       777476.86
#Sta/Elev= 30
  4466.0  685.03  4500.5  684.55  4524.9  683.38  4588.4  678.62  4633.9  674.10
  4677.6  670.72  4743.5  663.77  4810.4  652.76  4844.9  648.91  4891.4  647.21
  4899.7  647.94  4924.1  647.97  4938.0  647.31  4951.9  645.50  4952.9  644.31
  4959.8  644.49  4964.3  635.49  5035.7  635.49  5040.2  644.49  5042.8  650.15
  5051.8  652.32  5062.9  652.27  5103.8  657.00  5178.9  663.04  5209.1  663.73
  5285.9  667.67  5327.6  668.65  5462.2  669.44  5497.7  670.98  5615.2  673.65
#Mann=3,-1,0
  4466.0    0.08       0  4959.8   0.045       0  5040.2    0.08       0
Bank Sta=4959.8,5040.2
XS Rating Curve= 0
Exp/Cntr=0.3,0.1

Type RM Length L Ch R = 1,28226,475,475,475
BEGIN DESCRIPTION:
Dutchman Creek 24.0
END DESCRIPTION:
XS GIS Cut Line= 4
      1558025.03       777425.03      1557583.05       777056.70
      1557287.92       777021.98      1556654.28       776848.38
#Sta/Elev= 30
  4286.7  688.47  4332.6  684.02  4375.4  681.07  4745.5  666.39  4841.3  659.49
  4871.2  658.25  4927.6  649.16  4960.6  645.92  4963.8  644.07  4967.9  635.07
  5032.1  635.07  5036.2  644.07  5043.5  644.85  5090.1  646.50  5112.4  647.85
  5147.6  652.27  5181.1  658.80  5232.1  668.72  5274.7  672.55  5309.6  674.36
  5341.1  676.76  5351.6  678.11  5385.3  680.29  5449.3  682.23  5501.1  682.31
  5559.5  683.76  5601.2  685.86  5665.8  690.48  5750.8  694.93  5816.2  697.17
#Mann=5,-1,0
  4286.7    0.08       0  4963.8   0.045       0  5036.2    0.08       0
  5090.1    0.14       0  5181.1    0.08       0
Bank Sta=4963.8,5036.2
XS Rating Curve= 0
Exp/Cntr=0.3,0.1

Type RM Length L Ch R = 1,27751,548,548,548
BEGIN DESCRIPTION:
Dutchman Creek 23.0
END DESCRIPTION:
XS GIS Cut Line= 3
      1557835.28       776572.66      1557243.68       776562.28
      1556911.56       776624.55
#Sta/Elev= 30
  4603.1  674.41  4652.7  675.51  4671.1  674.13  4689.6  673.93  4710.0  669.31
  4711.9  667.92  4724.5  666.95  4738.5  663.90  4746.2  666.22  4757.1  663.39
  4768.8  663.51  4778.6  660.50  4786.5  659.45  4794.6  659.79  4811.9  656.37
  4950.3  647.48  4958.3  645.38  4959.8  643.81  4964.3  634.81  5035.7  634.81
  5040.2  643.81  5072.6  646.73  5103.1  647.08  5190.2  655.74  5224.1  657.07
  5272.1  661.31  5283.0  662.51  5356.4  674.74  5415.1  681.56  5532.7  683.72
#Mann=3,-1,0
  4603.1    0.14       0  4959.8   0.045       0  5040.2    0.14       0
Bank Sta=4959.8,5040.2
XS Rating Curve= 0
Exp/Cntr=0.3,0.1

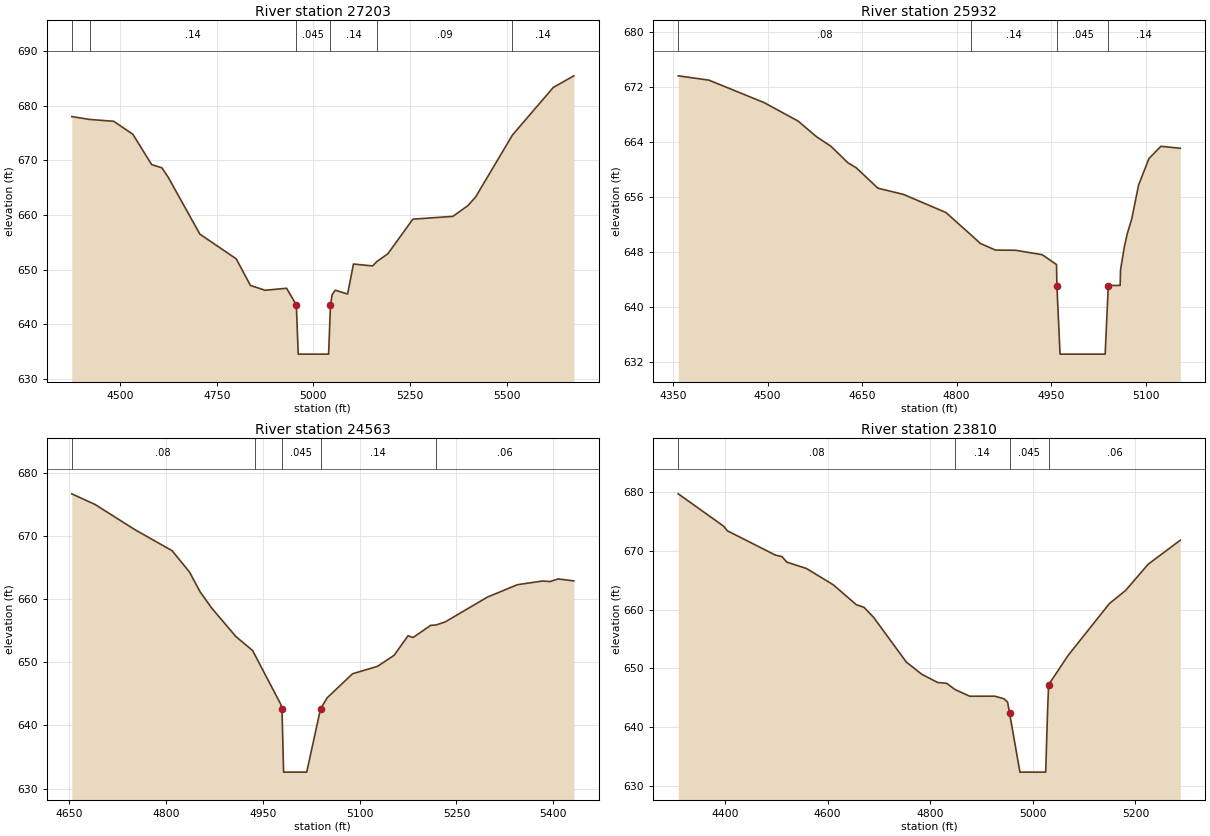
Type RM Length L Ch R = 1,27203,1271,1271,1271
BEGIN DESCRIPTION:
Dutchman Creek 22.0
END DESCRIPTION:
XS GIS Cut Line= 4
      1557834.77       776310.14      1557626.46       776015.03
      1557088.26       776032.39      1556732.33       776214.70
#Sta/Elev= 30
  4374.5  677.98  4420.6  677.46  4483.1  677.12  4532.7  674.74  4581.3  669.20
  4607.7  668.62  4624.2  666.89  4706.0  656.50  4800.2  651.98  4836.9  647.12
  4875.0  646.23  4930.5  646.60  4955.8  643.56  4960.7  634.56  5039.3  634.56
  5044.2  643.56  5048.4  645.42  5056.6  646.24  5088.5  645.55  5103.6  651.03
  5153.3  650.68  5164.3  651.49  5192.6  652.89  5257.4  659.23  5361.0  659.74
  5399.4  661.68  5419.5  663.24  5515.1  674.60  5620.9  683.31  5674.1  685.43
#Mann=6,-1,0
  4374.5    0.08       0  4420.6    0.14       0  4955.8   0.045       0
  5044.2    0.14       0  5164.3    0.09       0  5515.1    0.14       0
Bank Sta=4955.8,5044.2
XS Rating Curve= 0
Exp/Cntr=0.3,0.1

Type RM Length L Ch R = 1,25932,1369,1369,1369
BEGIN DESCRIPTION:
Dutchman Creek 21.0
END DESCRIPTION:
XS GIS Cut Line= 4
      1558034.43       775797.98      1557924.03       775483.38
      1557887.41       775113.89      1557847.47       775030.69
#Sta/Elev= 30
  4358.1  673.68  4406.9  673.05  4494.3  669.78  4548.3  667.09  4577.5  664.81
  4600.5  663.41  4628.0  660.96  4640.4  660.30  4675.1  657.30  4715.8  656.39
  4783.1  653.75  4822.7  650.50  4838.0  649.23  4861.6  648.28  4893.6  648.25
  4936.0  647.60  4958.6  646.16  4959.2  643.11  4964.2  633.11  5035.8  633.11
  5040.8  643.11  5059.6  643.13  5060.2  645.38  5066.2  648.71  5070.7  650.60
  5078.0  652.82  5088.9  657.77  5105.3  661.62  5124.3  663.41  5155.1  663.12
#Mann=4,-1,0
  4358.1    0.08       0  4822.7    0.14       0  4959.2   0.045       0
  5040.8    0.14       0
Bank Sta=4959.2,5040.8
XS Rating Curve= 0
Exp/Cntr=0.3,0.1

Type RM Length L Ch R = 1,24563,753,753,753
BEGIN DESCRIPTION:
Dutchman Creek 19.0
END DESCRIPTION:
XS GIS Cut Line= 4
      1558313.58       774296.04      1558139.66       774485.77
      1557896.21       774672.31      1557719.11       774792.48
#Sta/Elev= 30
  4653.8  676.66  4690.2  674.96  4752.1  670.96  4809.3  667.66  4836.2  664.29
  4852.7  661.16  4870.3  658.63  4908.1  654.08  4934.2  651.85  4937.4  651.21
  4977.4  643.42  4979.6  642.62  4982.1  632.62  5017.9  632.62  5039.3  642.62
  5049.5  644.37  5089.0  648.19  5127.6  649.36  5153.4  651.11  5174.9  654.19
  5182.8  653.93  5210.0  655.85  5218.3  655.90  5232.7  656.40  5298.2  660.33
  5344.4  662.28  5383.1  662.86  5395.1  662.78  5407.4  663.19  5431.9  662.88
#Mann=5,-1,0
  4653.8    0.08       0  4937.4    0.14       0  4979.6   0.045       0
  5039.3    0.14       0  5218.3    0.06       0
Bank Sta=4979.6,5039.3
XS Rating Curve= 0
Exp/Cntr=0.3,0.1

Type RM Length L Ch R = 1,23810,559,559,559
BEGIN DESCRIPTION:
Dutchman Creek 18.0
END DESCRIPTION:
XS GIS Cut Line= 5
      1558355.61       774031.52      1557928.75       773958.49
      1557786.60       773985.83      1557595.25       773974.89
      1557387.52       773947.56
#Sta/Elev= 30
  4308.6  679.74  4397.1  674.23  4404.2  673.45  4498.3  669.28  4510.9  669.04
  4520.2  668.10  4558.6  667.01  4610.8  664.24  4655.8  660.84  4670.8  660.39
  4689.4  658.70  4753.2  651.07  4783.4  648.98  4814.3  647.58  4832.3  647.42
  4848.1  646.38  4877.0  645.23  4925.8  645.24  4943.3  644.81  4950.8  644.24
  4954.8  642.29  4974.9  632.29  5025.1  632.29  5028.6  642.29  5030.8  647.19
  5068.5  652.15  5149.3  661.03  5181.0  663.27  5224.7  667.72  5287.6  671.84
#Mann=4,-1,0
  4308.6    0.08       0  4848.1    0.14       0  4954.8   0.045       0
  5030.8    0.06       0
Bank Sta=4954.8,5030.8
XS Rating Curve= 0
Exp/Cntr=0.3,0.1