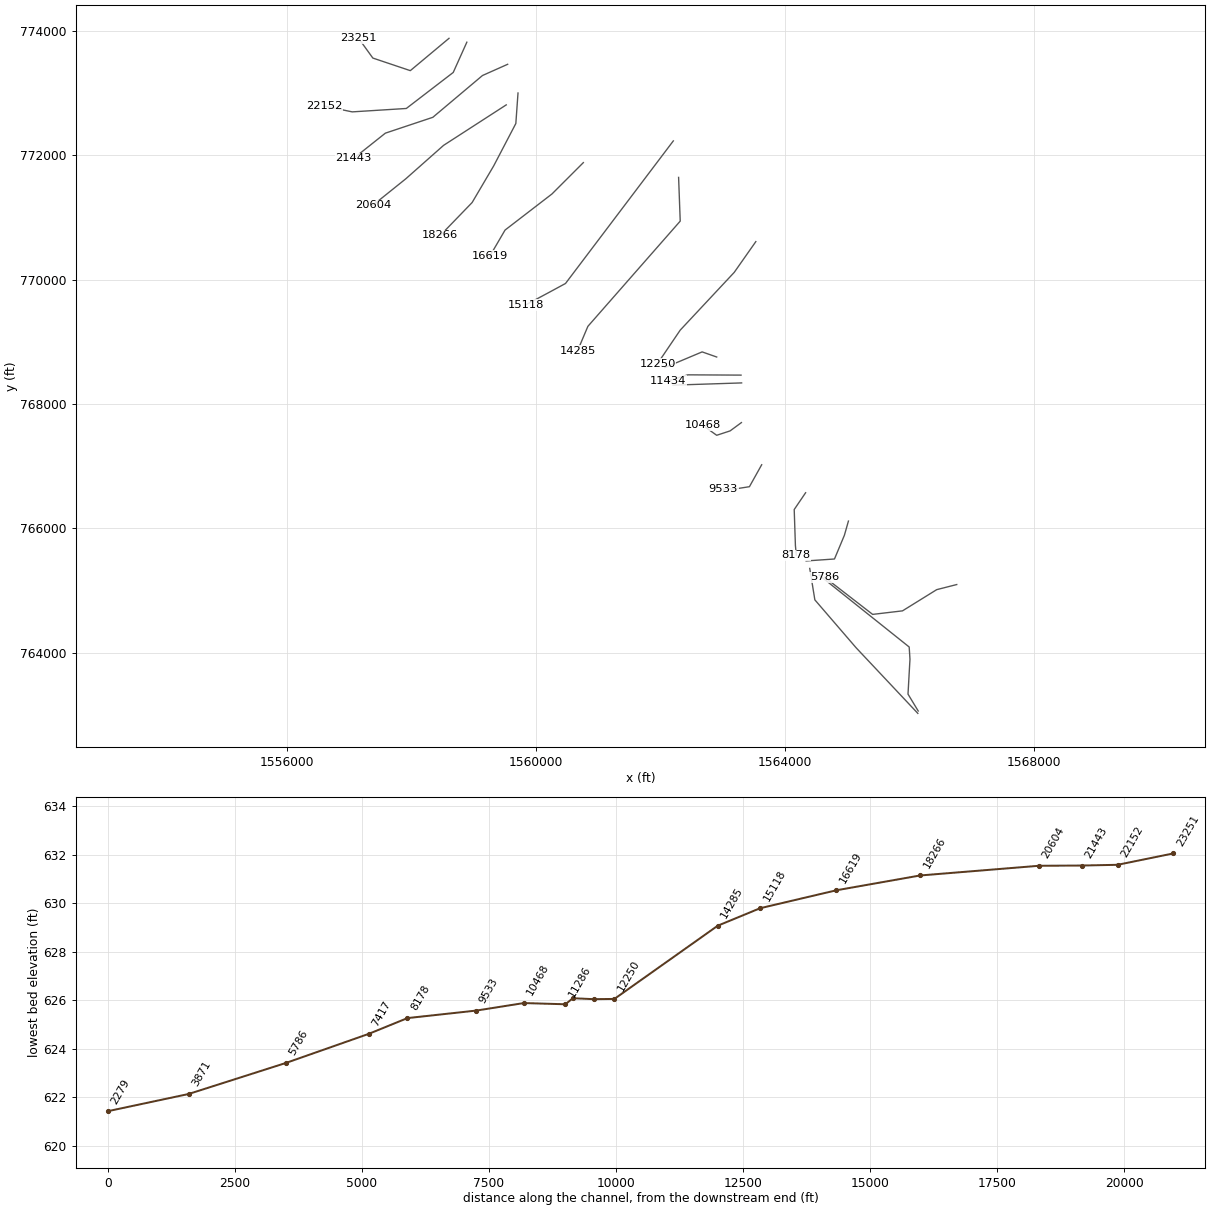
HEC-RAS study Dutchman Creek.prj: Dutchman Creek Limited Detail Study

--- Dutchman Creek.g01 (geometry) --- (continued)

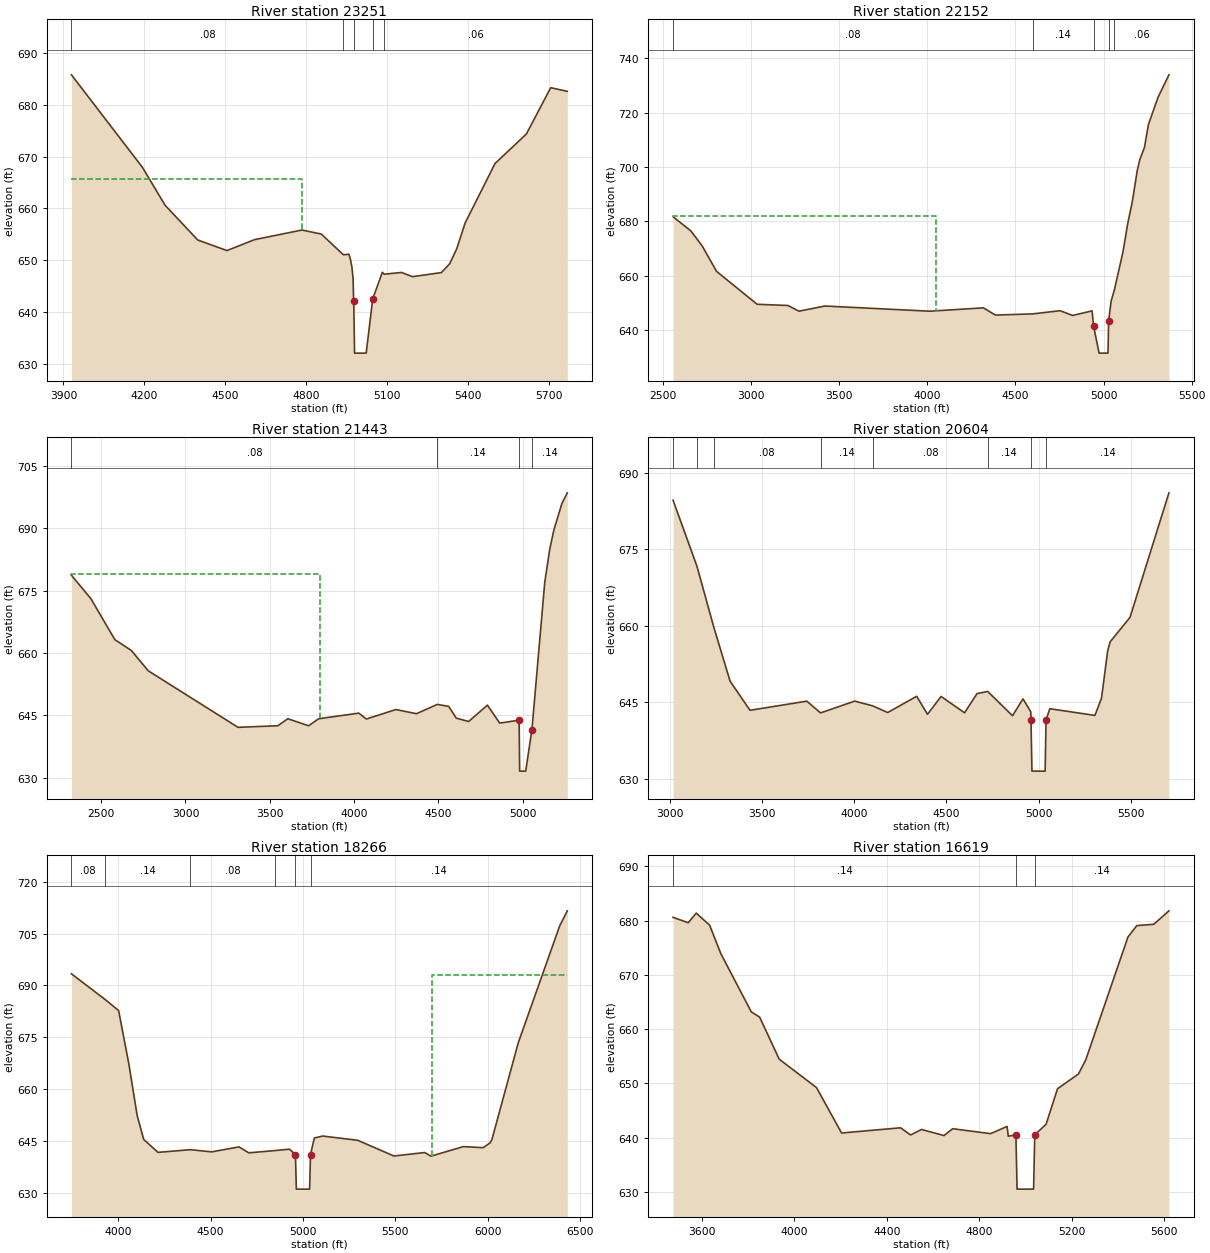
Type RM Length L Ch R = 1,23251,1099,1099,1099
BEGIN DESCRIPTION:
Dutchman Creek 17.0
END DESCRIPTION:
XS GIS Cut Line= 4
      1558598.67       773883.94      1557976.74       773364.20
      1557374.38       773566.71      1557145.88       773883.50
#Sta/Elev= 30
  3929.9  685.81  4193.3  667.90  4276.5  660.63  4397.5  653.91  4505.9  651.86
  4607.9  653.97  4783.6  655.83  4855.4  655.05  4937.1  651.05  4957.6  651.16
  4963.2  650.17  4968.7  648.67  4973.1  646.40  4975.0  642.05  4975.5  642.05
  4978.5  632.05  5021.5  632.05  5045.9  642.55  5081.5  647.67  5088.0  647.30
  5152.5  647.63  5193.0  646.82  5300.0  647.61  5330.6  649.30  5356.8  652.19
  5388.2  657.21  5498.8  668.68  5614.9  674.38  5705.0  683.32  5766.5  682.62
#Mann=5,-1,0
  3929.9    0.08       0  4937.1    0.14       0  4975.5   0.045       0
  5045.9    0.14       0  5088.0    0.06       0
#XS Ineff=2,0
    0.00 4783.10  665.78               0
Permanent Ineff=
       F       F
Bank Sta=4975.5,5045.9
XS Rating Curve= 0
Exp/Cntr=0.3,0.1

Type RM Length L Ch R = 1,22152,709,709,709
BEGIN DESCRIPTION:
Dutchman Creek 16.0
END DESCRIPTION:
XS GIS Cut Line= 5
      1558885.52       773821.86      1558666.81       773335.24
      1557912.34       772755.72      1557043.07       772701.04
      1556594.75       772793.99
#Sta/Elev= 30
  2557.3  681.70  2658.3  676.49  2722.3  671.01  2803.9  661.64  3034.2  649.53
  3208.7  649.09  3271.7  647.00  3419.0  648.89  4013.3  646.99  4318.2  648.22
  4386.4  645.56  4597.8  646.00  4753.2  647.17  4824.7  645.43  4935.1  647.11
  4943.2  641.57  4974.9  631.58  5025.1  631.58  5029.1  643.54  5043.1  650.68
  5062.0  654.94  5110.3  668.79  5136.9  679.09  5163.6  687.36  5190.9  698.52
  5205.5  702.67  5231.9  707.13  5254.7  715.59  5309.0  725.57  5371.0  733.86
#Mann=5,-1,0
  2557.3    0.08       0  4597.8    0.14       0  4943.2   0.045       0
  5029.1    0.14       0  5062.0    0.06       0
#XS Ineff=2,0
    0.00 4050.00  682.00               0
Permanent Ineff=
       F       F
Bank Sta=4943.2,5029.1
XS Rating Curve= 0
Exp/Cntr=0.3,0.1

Type RM Length L Ch R = 1,21443,839,839,839
BEGIN DESCRIPTION:
Dutchman Creek 15.0
END DESCRIPTION:
XS GIS Cut Line= 5
      1559541.54       773466.44      1559136.99       773286.03
      1558338.78       772613.57      1557575.80       772358.81
      1557067.27       771954.07
#Sta/Elev= 30
  2323.8  678.73  2438.8  673.10  2581.4  663.21  2678.7  660.62  2779.7  655.70
  3311.7  642.10  3548.0  642.48  3607.0  644.17  3730.4  642.48  3789.8  644.16
  4028.3  645.52  4072.6  644.10  4248.1  646.38  4370.1  645.38  4493.6  647.62
  4561.3  647.15  4606.0  644.32  4679.6  643.50  4791.0  647.44  4863.9  643.12
  4978.4  643.82  4979.6  641.55  4982.1  631.55  5017.9  631.55  5055.0  641.55
  5131.3  677.13  5160.9  685.06  5184.9  689.60  5233.0  696.05  5264.8  698.58
#Mann=4,-1,0
  2323.8    0.08       0  4493.6    0.14       0  4978.4   0.045       0
  5055.0    0.14       0
#XS Ineff=2,0
    0.00 3800.00  679.00               0
Permanent Ineff=
       F       F
Bank Sta=4978.4,5055
XS Rating Curve= 0
Exp/Cntr=0.3,0.1

Type RM Length L Ch R = 1,20604,2338,2338,2338
BEGIN DESCRIPTION:
Dutchman Creek 14.0
END DESCRIPTION:
XS GIS Cut Line= 4
      1559518.84       772813.66      1558511.87       772162.60
      1557904.24       771624.41      1557374.73       771199.07
#Sta/Elev= 30
  3017.4  684.58  3147.4  671.61  3237.8  659.79  3326.6  649.17  3434.7  643.45
  3742.8  645.24  3817.7  642.94  4002.5  645.25  4101.6  644.31  4181.8  643.01
  4338.8  646.19  4397.7  642.67  4471.5  646.16  4598.8  642.96  4666.3  646.72
  4724.3  647.14  4858.8  642.39  4915.8  645.69  4958.1  643.14  4959.2  641.54
  4964.2  631.54  5035.8  631.54  5040.8  641.54  5061.1  643.76  5306.0  642.45
  5341.7  645.83  5375.2  655.10  5388.6  656.86  5496.3  661.65  5707.4  686.03
#Mann=8,-1,0
  3017.4    0.08       0  3147.4    0.14       0  3237.8    0.08       0
  3817.7    0.14       0  4101.6    0.08       0  4724.3    0.14       0
  4959.2   0.045       0  5040.8    0.14       0
Bank Sta=4959.2,5040.8
XS Rating Curve= 0
Exp/Cntr=0.3,0.1

Type RM Length L Ch R = 1,18266,1647,1647,1647
BEGIN DESCRIPTION:
Dutchman Creek 13.0
END DESCRIPTION:
XS GIS Cut Line= 5
      1559708.05       773004.59      1559673.20       772514.04
      1559317.43       771832.74      1558970.21       771242.46
      1558458.05       770712.94
#Sta/Elev= 30
  3747.8  693.36  3927.7  686.04  4002.8  682.75  4058.0  667.39  4103.5  652.33
  4138.6  645.50  4215.9  641.76  4391.1  642.54  4506.5  641.91  4654.0  643.35
  4706.9  641.63  4848.3  642.28  4926.7  642.69  4959.2  641.14  4964.2  631.14
  5035.8  631.14  5040.8  641.14  5061.5  645.92  5107.0  646.48  5295.7  645.26
  5492.1  640.71  5658.4  641.72  5691.8  640.67  5868.0  643.43  5974.7  643.12
  6012.4  644.53  6021.8  645.45  6164.7  673.49  6388.5  707.21  6429.7  711.57
#Mann=6,-1,0
  3747.8    0.08       0  3927.7    0.14       0  4391.1    0.08       0
  4848.3    0.14       0  4959.2   0.045       0  5040.8    0.14       0
#XS Ineff=2,0
       0                 5700.00    0.00  693.00
Permanent Ineff=
       F       F
Bank Sta=4959.2,5040.8
XS Rating Curve= 0
Exp/Cntr=0.3,0.1

Type RM Length L Ch R = 1,16619,1501,1501,1501
BEGIN DESCRIPTION:
Dutchman Creek 12.0
END DESCRIPTION:
XS GIS Cut Line= 4
      1560758.41       771884.83      1560254.93       771381.35
      1559499.72       770799.75      1559256.67       770383.09
#Sta/Elev= 30
  3474.3  680.60  3540.0  679.61  3574.7  681.38  3632.6  679.16  3681.4  673.90
  3813.1  663.18  3849.3  662.22  3934.0  654.47  4095.5  649.24  4204.2  640.87
  4459.7  641.83  4503.2  640.51  4550.2  641.52  4647.8  640.40  4685.4  641.66
  4849.5  640.75  4921.0  642.08  4926.1  640.28  4959.2  640.53  4964.2  630.53
  5035.8  630.53  5040.8  640.53  5089.9  642.49  5139.5  649.03  5230.1  651.74
  5261.8  654.36  5444.4  676.97  5482.9  679.08  5556.5  679.32  5621.9  681.80
#Mann=3,-1,0
  3474.3    0.14       0  4959.2   0.045       0  5040.8    0.14       0
Bank Sta=4959.2,5040.8
XS Rating Curve= 0
Exp/Cntr=0.3,0.1

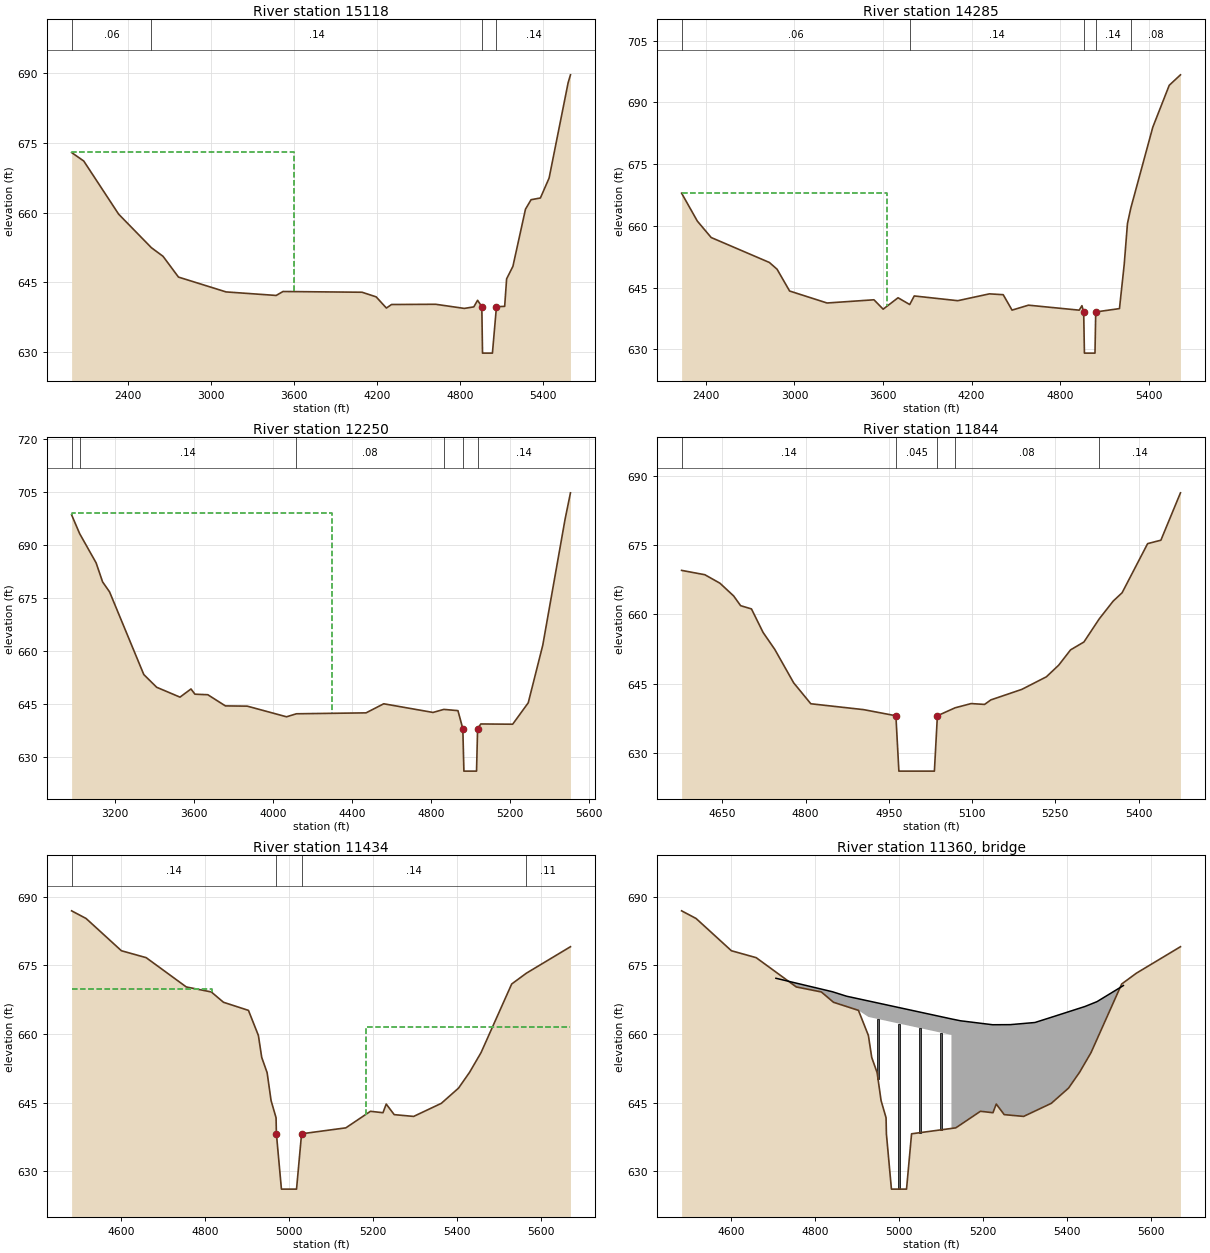
Type RM Length L Ch R = 1,15118,833,833,833
BEGIN DESCRIPTION:
Dutchman Creek 11.0
END DESCRIPTION:
XS GIS Cut Line= 4
      1562204.82       772234.28      1560471.52       769940.52
      1560222.43       769805.60      1559828.90       769594.43
#Sta/Elev= 30
  1994.9  672.95  2082.8  671.12  2334.8  659.69  2571.6  652.47  2655.7  650.62
  2767.2  646.15  3111.2  642.96  3473.1  642.20  3522.5  643.05  4093.7  642.89
  4195.4  641.90  4269.7  639.49  4306.9  640.25  4626.2  640.30  4832.6  639.41
  4901.2  639.74  4928.6  641.16  4959.2  639.79  4964.2  629.79  5035.8  629.79
  5065.0  639.79  5124.3  639.85  5138.4  645.77  5183.9  648.47  5274.8  660.77
  5315.1  662.80  5382.5  663.17  5445.3  667.45  5582.9  687.97  5599.8  689.67
#Mann=4,-1,0
  1994.9    0.06       0  2571.6    0.14       0  4959.2   0.045       0
  5065.0    0.14       0
#XS Ineff=2,0
    0.00 3600.00  673.00               0
Permanent Ineff=
       F       F
Bank Sta=4959.2,5065
XS Rating Curve= 0
Exp/Cntr=0.3,0.1

Type RM Length L Ch R = 1,14285,2035,2035,2035
BEGIN DESCRIPTION:
Dutchman Creek 10.0
END DESCRIPTION:
XS GIS Cut Line= 4
      1562289.65       771646.96      1562315.69       770943.85
      1560831.32       769251.14      1560666.38       768860.49
#Sta/Elev= 30
  2235.8  667.93  2342.4  661.15  2436.1  657.16  2830.2  651.10  2882.3  649.46
  2967.4  644.16  3221.0  641.25  3538.7  642.03  3601.0  639.75  3701.8  642.52
  3780.9  640.88  3811.5  642.96  4106.6  641.81  4320.5  643.47  4414.0  643.27
  4474.1  639.52  4585.1  640.72  4928.9  639.51  4947.4  640.60  4959.2  639.07
  4964.2  629.07  5035.8  629.07  5040.8  639.07  5201.6  639.89  5233.7  650.60
  5255.8  660.57  5278.6  664.33  5427.3  683.96  5538.6  694.14  5614.8  696.69
#Mann=5,-1,0
  2235.8    0.06       0  3780.9    0.14       0  4959.2   0.045       0
  5040.8    0.14       0  5278.6    0.08       0
#XS Ineff=2,0
    0.00 3625.00  668.00               0
Permanent Ineff=
       F       F
Bank Sta=4959.2,5040.8
XS Rating Curve= 0
Exp/Cntr=0.3,0.1

Type RM Length L Ch R = 1,12250,406,406,406
BEGIN DESCRIPTION:
Dutchman Creek 9.0
END DESCRIPTION:
XS GIS Cut Line= 4
      1563530.97       770613.99      1563183.75       770119.20
      1562315.69       769190.38      1561951.13       768652.21
#Sta/Elev= 30
  2981.8  698.54  3022.5  693.23  3105.8  684.97  3138.7  679.58  3174.0  676.75
  3347.3  653.37  3412.5  649.77  3530.5  646.98  3586.3  649.29  3606.2  647.81
  3671.4  647.66  3760.5  644.50  3871.3  644.43  4070.0  641.42  4120.0  642.27
  4472.6  642.53  4562.2  645.10  4811.6  642.65  4866.3  643.51  4937.9  643.16
  4962.6  638.05  4968.0  626.05  5032.0  626.05  5037.4  638.05  5053.6  639.39
  5215.0  639.32  5293.8  645.38  5367.3  661.66  5480.3  697.31  5507.6  704.77
#Mann=6,-1,0
  2981.8    0.08       0  3022.5    0.14       0  4120.0    0.08       0
  4866.3    0.14       0  4962.6   0.045       0  5037.4    0.14       0
#XS Ineff=2,0
    0.00 4300.00  699.00               0
Permanent Ineff=
       F       F
Bank Sta=4962.6,5037.4
XS Rating Curve= 0
Exp/Cntr=0.3,0.1

Type RM Length L Ch R = 1,11844,410,410,410
BEGIN DESCRIPTION:
Dutchman Creek 8.0
END DESCRIPTION:
XS GIS Cut Line= 3
      1562901.78       768757.99      1562667.97       768840.14
      1562067.73       768587.40
#Sta/Elev= 30
  4576.4  669.55  4618.3  668.61  4645.5  666.77  4670.2  664.01  4682.8  661.90
  4702.3  661.20  4723.2  656.11  4744.4  652.41  4778.4  645.17  4809.3  640.64
  4904.3  639.37  4962.6  638.04  4968.0  626.04  5032.0  626.04  5037.4  638.04
  5069.2  639.76  5098.2  640.68  5122.4  640.50  5133.8  641.48  5189.6  643.76
  5233.8  646.48  5256.0  649.00  5277.4  652.32  5301.5  654.03  5329.1  659.04
  5354.2  662.89  5370.3  664.70  5416.3  675.35  5440.2  676.09  5475.5  686.36
#Mann=5,-1,0
  4576.4    0.14       0  4962.6   0.045       0  5037.4    0.14       0
  5069.2    0.08       0  5329.1    0.14       0
Bank Sta=4962.6,5037.4
XS Rating Curve= 0
Exp/Cntr=0.5,0.3

Type RM Length L Ch R = 1,11434,148,148,148
BEGIN DESCRIPTION:
NC 801 (DC) us
END DESCRIPTION:
XS GIS Cut Line= 3
      1563293.49       768466.64      1562437.59       768471.13
      1562119.43       768372.54
#Sta/Elev= 30
  4481.9  686.94  4516.5  685.26  4600.6  678.21  4659.6  676.70  4755.3  670.29
  4814.9  669.20  4843.9  666.94  4903.4  665.17  4927.1  659.68  4935.0  654.89
  4947.9  651.55  4957.3  645.45  4969.2  641.68  4970.0  638.18  4982.0  626.08
  5018.0  626.08  5030.0  638.18  5135.5  639.48  5194.2  643.10  5224.0  642.79
  5231.8  644.68  5250.8  642.37  5297.1  641.98  5363.1  644.84  5404.1  648.17
  5430.5  651.64  5457.8  655.94  5530.8  670.94  5565.8  673.30  5670.9  679.09
#Mann=4,-1,0
  4481.9    0.14       0  4970.0   0.045       0  5030.0    0.14       0
  5565.8    0.11       0
#XS Ineff=2,0
    0.00 4817.50  669.84 5182.50    0.00  661.61
Permanent Ineff=
       F       F
Bank Sta=4970,5030
XS Rating Curve= 0
Exp/Cntr=0.5,0.3

Type RM Length L Ch R =3,11360,,,
BEGIN DESCRIPTION:
NC 801 (DC) tor
Structure ID: LDS_DC_01
Approximate Survey Structure
END DESCRIPTION:
Bridge Culvert--1,0,-1,-1,0
Deck Dist Width WeirC Skew NumUp NumDn MinLoCord MaxHiCord MaxSubmerge Is_Ogee
57.5,33,3,,14,14,,,0.95,0,1,1,,,
  4706.7  4841.6  4875.0  4875.0  5125.0  5125.0  5146.3  5223.1  5265.3  5324.0
  5369.6  5443.5  5471.9  5534.9
  672.19  669.24  668.27  668.27  663.30  663.30  662.90  662.03  662.05  662.52
  663.85  666.03  667.08  670.60
  606.08  606.08  606.08  664.77  659.80  606.08  606.08  606.08  606.08  606.08
  606.08  606.08  606.08  606.08
  4706.7  4841.6  4875.0  4875.0  5125.0  5125.0  5146.3  5223.1  5265.3  5324.0
  5369.6  5443.5  5471.9  5534.9
  672.19  669.24  668.27  668.27  663.30  663.30  662.90  662.03  662.05  662.52
  663.85  666.03  667.08  670.60
  606.08  606.08  606.08  664.77  659.80  606.08  606.08  606.08  606.08  606.08
  606.08  606.08  606.08  606.08
Pier Skew, UpSta & Num, DnSta & Num=,4900,2,4900,2,0,0,0,0,0
       3       3
  665.20  667.00
       3       3
  655.46  665.00
Pier Skew, UpSta & Num, DnSta & Num=,4950,2,4950,2,0,0,0,0,0
       3       3
  650.26  666.50
       3       3
  643.89  666.20
Pier Skew, UpSta & Num, DnSta & Num=,5000,2,5000,2,0,0,0,0,0
       3       3
  626.08  662.48
       3       3
  625.83  662.48
Pier Skew, UpSta & Num, DnSta & Num=,5050,2,5050,2,0,0,0,0,0
       3       3
  638.06  662.48
       3       3
  637.97  662.48
Pier Skew, UpSta & Num, DnSta & Num=,5100,2,5100,2,0,0,0,0,0
       3       3
  638.82  662.48
       3       3
  639.51  662.48
Abutment Skew #Up #Dn=,2,2
  4875.0  4912.0
  664.77  653.65
  4875.0  4912.0
  664.77  653.65
Abutment Skew #Up #Dn=,2,2
  5088.0  5125.0
  639.53  659.80
  5088.0  5125.0
  639.53  659.80
BR Coef=1,1,0,1.25,0,,,0.8,0,2,0,
WSPro=,,,, 1 ,,,, 0 ,,,, 0 ,,,,-1 ,-1 ,-1 , 0 , 0 , 0 , 0 , 0
BC Design=,,0,,0,,,,,,

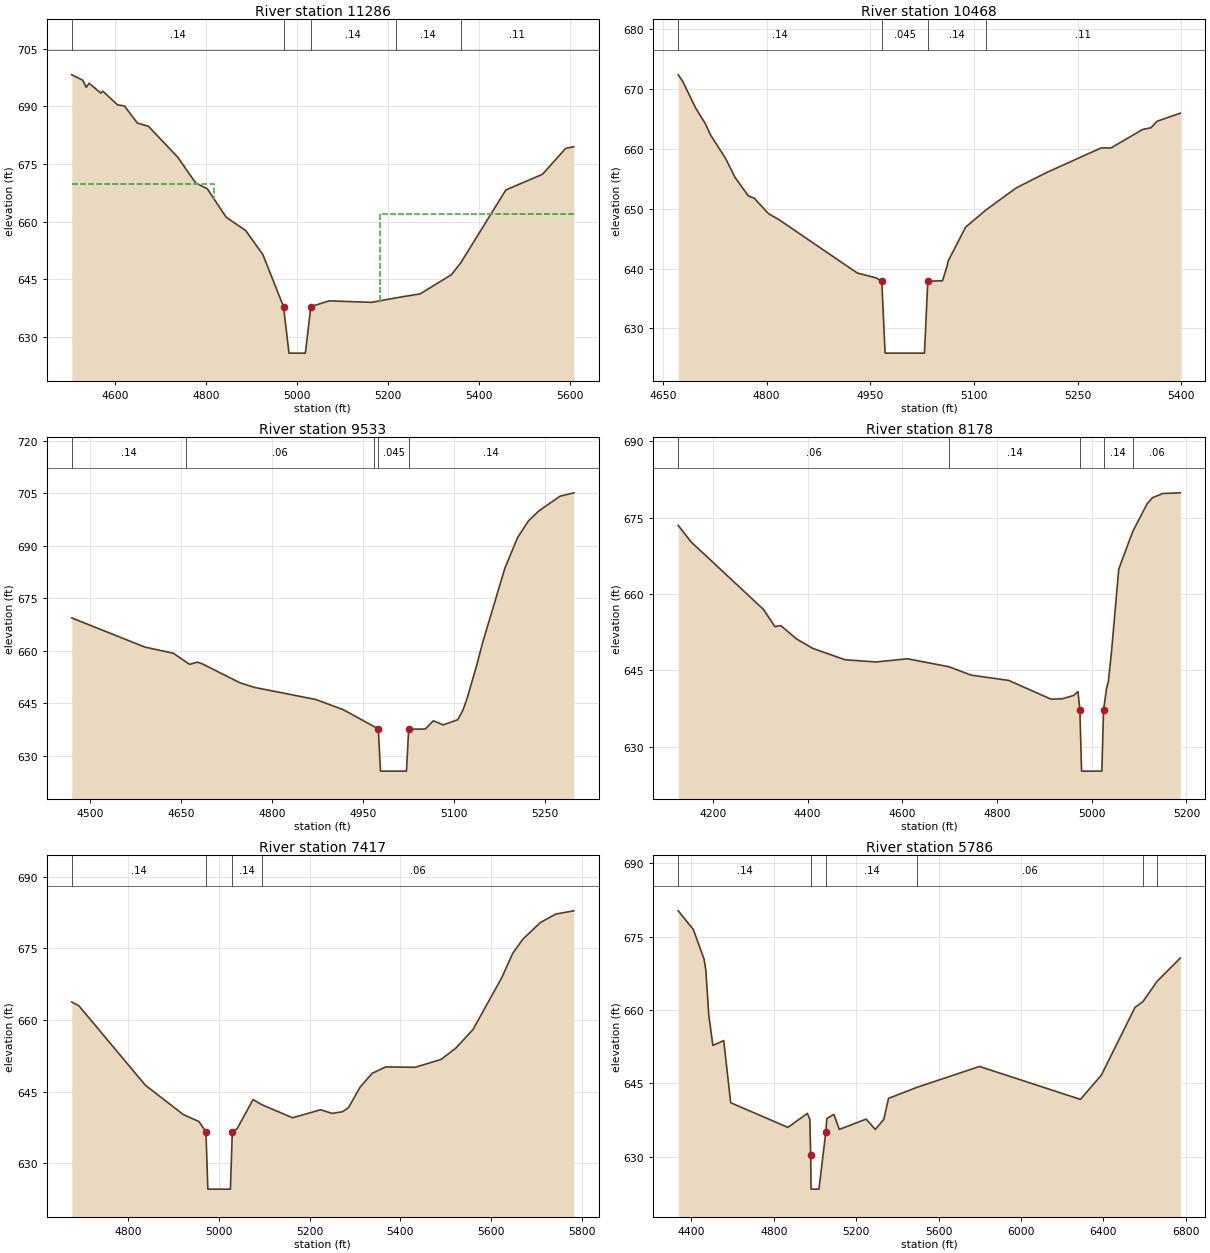
Type RM Length L Ch R = 1,11286,818,818,818
BEGIN DESCRIPTION:
NC 801 (DC) ds
END DESCRIPTION:
XS GIS Cut Line= 3
      1563302.45       768341.17      1562616.84       768318.76
      1562200.03       768305.32
#Sta/Elev= 30
  4504.8  698.20  4528.7  696.82  4536.6  694.96  4542.8  696.01  4568.8  693.45
  4573.2  693.94  4605.4  690.38  4620.4  690.12  4648.9  685.66  4673.3  684.81
  4737.4  676.82  4777.2  670.06  4802.7  668.55  4844.1  661.16  4886.9  657.71
  4924.5  651.48  4970.0  637.93  4982.0  625.83  5018.0  625.83  5030.0  637.93
  5070.3  639.42  5163.7  639.04  5216.2  640.19  5270.0  641.24  5338.6  646.19
  5359.4  649.32  5458.4  668.26  5538.9  672.34  5589.7  679.06  5607.8  679.51
#Mann=5,-1,0
  4504.8    0.14       0  4970.0   0.045       0  5030.0    0.14       0
  5216.2    0.14       0  5359.4    0.11       0
#XS Ineff=2,0
    0.00 4817.50  669.84 5182.50    0.00  661.90
Permanent Ineff=
       F       F
Bank Sta=4970,5030
XS Rating Curve= 0
Exp/Cntr=0.5,0.3

Type RM Length L Ch R = 1,10468,935,935,935
BEGIN DESCRIPTION:
Dutchman Creek 7.0
END DESCRIPTION:
XS GIS Cut Line= 4
      1563299.46       767703.08      1563117.46       767569.37
      1562902.02       767498.80      1562679.18       767658.50
#Sta/Elev= 30
  4672.1  672.32  4678.4  671.27  4697.4  666.76  4711.3  664.18  4719.0  662.26
  4740.4  658.41  4754.2  655.23  4773.5  652.12  4782.4  651.71  4802.6  649.16
  4817.7  648.17  4931.1  639.26  4958.6  638.43  4966.7  637.88  4971.5  625.88
  5028.5  625.88  5033.3  637.88  5054.6  637.96  5061.4  640.46  5062.6  641.21
  5088.0  646.90  5117.8  649.80  5161.2  653.44  5204.6  655.98  5284.1  660.12
  5298.4  660.12  5344.4  663.21  5356.4  663.49  5365.3  664.58  5398.8  665.92
#Mann=4,-1,0
  4672.1    0.14       0  4966.7   0.045       0  5033.3    0.14       0
  5117.8    0.11       0
Bank Sta=4966.7,5033.3
XS Rating Curve= 0
Exp/Cntr=0.3,0.1

Type RM Length L Ch R = 1,9533,1355,1355,1355
BEGIN DESCRIPTION:
Dutchman Creek 6.0
END DESCRIPTION:
XS GIS Cut Line= 4
      1563625.37       767025.09      1563428.25       766671.80
      1563207.77       766637.29      1563008.43       766633.40
#Sta/Elev= 30
  4470.0  669.38  4590.5  661.04  4637.5  659.27  4658.5  656.75  4664.1  656.11
  4677.0  656.73  4685.4  656.22  4746.8  650.85  4771.0  649.51  4872.1  646.05
  4917.3  643.13  4967.9  638.33  4975.0  637.57  4978.6  625.57  5021.4  625.57
  5025.0  637.57  5052.3  637.60  5065.7  639.97  5081.9  638.80  5105.9  640.28
  5114.7  643.14  5121.4  646.44  5137.0  655.80  5147.1  662.47  5183.5  683.62
  5204.6  692.42  5222.4  697.15  5239.5  699.99  5274.5  704.19  5297.1  705.15
#Mann=5,-1,0
  4470.0    0.14       0  4658.5    0.06       0  4967.9    0.14       0
  4975.0   0.045       0  5025.0    0.14       0
Bank Sta=4975,5025
XS Rating Curve= 0
Exp/Cntr=0.3,0.1

Type RM Length L Ch R = 1,8178,761,761,761
BEGIN DESCRIPTION:
Dutchman Creek 5.0
END DESCRIPTION:
XS GIS Cut Line= 4
      1564331.36       766574.59      1564148.12       766304.55
      1564167.41       765725.88      1564181.87       765571.59
#Sta/Elev= 30
  4126.8  673.46  4153.9  670.23  4306.6  657.00  4331.0  653.61  4343.5  653.81
  4376.3  651.21  4410.9  649.34  4478.8  647.11  4544.3  646.67  4611.0  647.30
  4698.8  645.73  4745.5  644.09  4824.5  643.06  4914.3  639.37  4938.3  639.46
  4961.9  640.11  4971.0  640.86  4975.0  637.26  4978.6  625.26  5021.4  625.26
  5025.0  637.26  5031.3  641.48  5035.3  642.92  5041.8  648.68  5057.1  664.89
  5086.8  672.30  5116.8  677.67  5128.5  678.90  5150.0  679.72  5187.1  679.85
#Mann=5,-1,0
  4126.8    0.06       0  4698.8    0.14       0  4975.0   0.045       0
  5025.0    0.14       0  5086.8    0.06       0
Bank Sta=4975,5025
XS Rating Curve= 0
Exp/Cntr=0.3,0.1

Type RM Length L Ch R = 1,7417,1631,1631,1631
BEGIN DESCRIPTION:
Dutchman Creek 4.0
END DESCRIPTION:
XS GIS Cut Line= 4
      1565019.74       766118.86      1564954.65       765889.84
      1564795.51       765508.88      1564339.84       765477.53
#Sta/Elev= 30
  4674.9  663.75  4690.4  662.99  4837.2  646.36  4920.8  640.22  4955.5  638.75
  4970.9  636.61  4975.1  624.61  5024.9  624.61  5029.1  636.61  5039.7  637.25
  5074.8  643.34  5094.0  642.29  5162.0  639.53  5224.0  641.22  5249.1  640.45
  5272.1  640.80  5285.2  641.62  5310.7  645.91  5337.9  648.86  5367.3  650.17
  5432.4  650.10  5489.5  651.74  5522.5  654.13  5560.2  658.01  5624.0  668.92
  5647.7  673.94  5670.3  676.93  5709.0  680.40  5743.0  682.16  5782.6  682.83
#Mann=4,-1,0
  4674.9    0.14       0  4970.9   0.045       0  5029.1    0.14       0
  5094.0    0.06       0
Bank Sta=4970.9,5029.1
XS Rating Curve= 0
Exp/Cntr=0.3,0.1

Type RM Length L Ch R = 1,5786,1915,1915,1915
BEGIN DESCRIPTION:
Dutchman Creek 3.0
END DESCRIPTION:
XS GIS Cut Line= 5
      1566760.88       765097.88      1566438.66       765015.75
      1565888.98       764674.57      1565408.80       764617.70
      1564638.01       765214.75
#Sta/Elev= 30
  4335.9  680.25  4409.1  676.45  4461.2  670.39  4469.8  668.18  4484.3  658.93
  4504.2  652.76  4556.8  653.75  4590.6  641.06  4868.3  636.02  4962.9  638.88
  4974.9  637.64  4979.1  630.41  4980.8  623.41  5019.2  623.41  5052.8  635.15
  5057.3  637.82  5091.7  638.69  5118.1  635.60  5248.1  637.71  5293.0  635.61
  5333.9  637.66  5357.1  641.95  5497.1  644.23  5798.9  648.46  6289.0  641.74
  6390.5  646.69  6553.9  660.53  6592.1  661.69  6661.1  665.85  6773.9  670.61
#Mann=6,-1,0
  4335.9    0.14       0  4979.1   0.045       0  5052.8    0.14       0
  5497.1    0.06       0  6592.1    0.14       0  6661.1    0.06       0
Bank Sta=4979.1,5052.8
XS Rating Curve= 0
Exp/Cntr=0.3,0.1

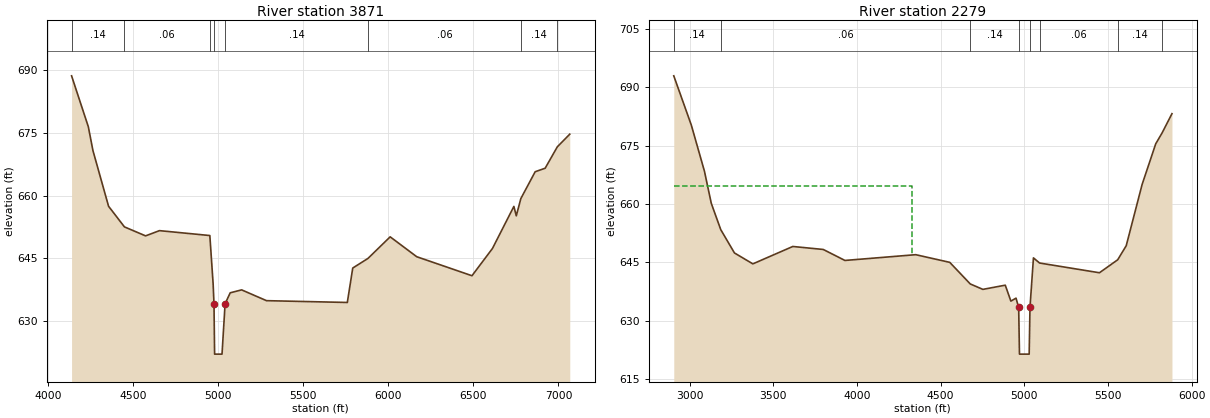
Type RM Length L Ch R = 1,3871,1592,1592,1592
BEGIN DESCRIPTION:
Dutchman Creek 2.0
END DESCRIPTION:
XS GIS Cut Line= 5
      1566141.69       763063.46      1565977.43       763335.12
      1566009.02       763897.43      1565996.39       764093.30
      1564549.55       765249.50
#Sta/Elev= 30
  4137.3  688.66  4235.8  676.49  4263.1  670.76  4354.8  657.48  4448.0  652.55
  4572.4  650.40  4654.1  651.65  4950.2  650.48  4969.6  638.90  4974.6  634.13
  4978.2  622.13  5021.8  622.13  5039.9  634.17  5070.0  636.79  5137.2  637.49
  5283.3  634.91  5758.5  634.48  5790.4  642.71  5879.7  645.00  6010.4  650.17
  6166.4  645.42  6491.3  640.87  6611.7  647.38  6737.7  657.44  6751.9  655.19
  6778.7  659.32  6862.9  665.73  6921.6  666.57  6993.2  671.69  7066.3  674.71
#Mann=8,-1,0
  4137.3    0.14       0  4448.0    0.06       0  4950.2    0.14       0
  4974.6   0.045       0  5039.9    0.14       0  5879.7    0.06       0
  6778.7    0.14       0  6993.2    0.06       0
Bank Sta=4974.6,5039.9
XS Rating Curve= 0
Exp/Cntr=0.3,0.1

Type RM Length L Ch R = 1,2279,0,0,0
BEGIN DESCRIPTION:
Dutchman Creek 1.0
END DESCRIPTION:
XS GIS Cut Line= 4
      1566135.38       763025.53      1565143.43       764080.66
      1564480.03       764851.48      1564397.88       765356.96
#Sta/Elev= 30
  2905.0  692.90  3010.0  680.23  3088.5  668.37  3129.2  660.15  3185.7  653.40
  3267.6  647.41  3377.6  644.60  3616.4  649.07  3798.4  648.30  3928.0  645.48
  4351.0  646.96  4554.4  644.99  4677.0  639.44  4752.3  638.05  4886.1  639.13
  4919.6  635.04  4950.4  635.80  4966.2  633.42  4971.0  621.42  5029.0  621.42
  5033.8  633.42  5054.5  646.14  5091.2  644.82  5448.9  642.32  5558.0  645.65
  5609.0  649.27  5704.0  665.01  5785.3  675.44  5823.8  678.27  5882.3  683.18
#Mann=8,-1,0
  2905.0    0.14       0  3185.7    0.06       0  4677.0    0.14       0
  4966.2   0.045       0  5033.8    0.14       0  5091.2    0.06       0
  5558.0    0.14       0  5823.8    0.06       0
#XS Ineff=2,0
    0.00 4327.70  664.52               0
Permanent Ineff=
       F       F
Bank Sta=4966.2,5033.8
XS Rating Curve= 0
Exp/Cntr=0.3,0.1

Chan Stop Cuts=-1