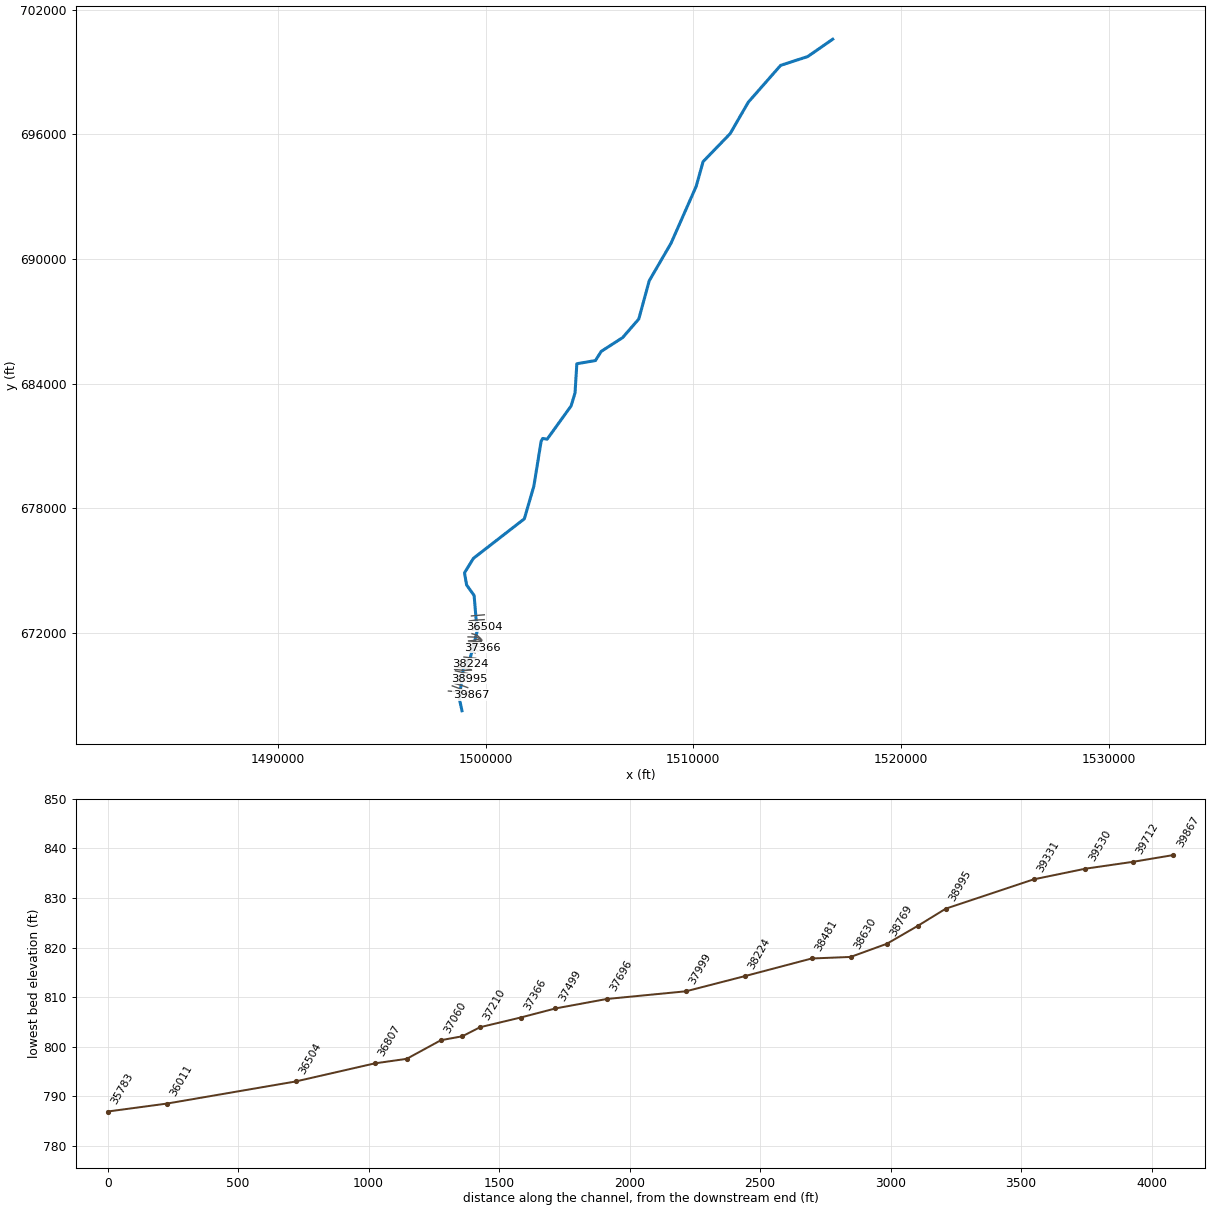
--- Kerr Creek.prj (project) ---

Proj Title=.Kerr Creek Limited Detail Study
Current Plan=p01
Default Exp/Contr=0.3,0.1
English Units
Geom File=g01
Flow File=f01
Plan File=p01
Y Axis Title=Elevation
X Axis Title(PF)=Main Channel Distance
X Axis Title(XS)=Station
BEGIN DESCRIPTION:
Kerr Creek
END DESCRIPTION:
DSS Export Rating Curves= 0
DSS Export Rating Curve Sorted= 0
DSS Export Volume Flow Curves= 0
DXF OffsetX= 0
DXF OffsetY= 0
DXF ScaleX= 1
DXF ScaleY= 10

--- Kerr Creek.p01 (plan) ---

Plan Title=Floodway Run
Program Version=3.12
Short Identifier=Floodway
Geom File=g01
Flow File=f01
Subcritical Flow
K Sum by GR= 0
Std Step Tol= 0.01
Critical Tol= 0.01
Num of Std Step Trials= 20
Max Error Tol= 0.3
Flow Tol Ratio= 0.001
Split Flow NTrial= 30
Split Flow Tol= 0.02
Split Flow Ratio= 0.02
Log Output Level= 0
Friction Slope Method= 1
Unsteady Friction Slope Method= 2
Unsteady Bridges Friction Slope Method= 1
Parabolic Critical Depth
Global Vel Dist= 0 , 0 , 0
Global Log Level= 0
CheckData=True
Encroach Param=-1 ,10,10, 2
Encroach River=Kerr Creek
Encroach Reach=Reach-1
Encroach Node=39867
       1 4958.81    5010
Encroach Node=39712
       1 4983.14    5012
Encroach Node=39530
       1 4949.12    5012
Encroach Node=39331
       1    4992    5030
Encroach Node=38995
       1    4890    5051
Encroach Node=38887
       1  4860.2  5054.2
Encroach Node=38769
       1    4862    5022
Encroach Node=38630
       1    4988 5019.65
Encroach Node=38481
       1    4994    5011
Encroach Node=38224
       1    4996    5015
Encroach Node=37999
       1  4996.5    5012
Encroach Node=37696
       1    4980    5010
Encroach Node=37499
       1    4992    5008
Encroach Node=37366
       1    4995    5012
Encroach Node=37210
       1    4987    5018
Encroach Node=37142
       1    4984    5016
Encroach Node=37060
       1    4987    5019
Encroach Node=36929
       1    4990    5007
Encroach Node=36807
       1    4990    5018
Encroach Node=36504
       1    4988 5016.88
Encroach Node=36011
       1    4988    5012
Encroach Node=35783
       1    4994 5015.72
Encroach Node=35335
       1    4988    5012
Encroach Node=35000
       1    4995    5010
Encroach Node=34518
       1    4988    5011
Encroach Node=34175
       1 4984.03    5012
Encroach Node=33856
       1    4988 5017.44
Encroach Node=33480
       1    4970    5035
Encroach Node=33116
       1    4930    5050
Encroach Node=32503
       1    4915    5025
Encroach Node=32128
       1    4950    5050
Encroach Node=32025
       1    4958    5043
Encroach Node=31500
       1 4969.25 5068.93
Encroach Node=31013
       1    4970    5025
Encroach Node=30511
       1 4935.46    5023
Encroach Node=30004
       1 4928.44 5019.84
Encroach Node=29516
       1 4985.76 5135.56
Encroach Node=29013
       1  4984.1 5070.38
Encroach Node=28499
       1 4983.88 5103.39
Encroach Node=28014
       1    4960    5040
Encroach Node=27501
       1 4890.39 5042.72
Encroach Node=27003
       1 4935.42 5064.04
Encroach Node=26502
       1 4964.68 5097.57
Encroach Node=26275
       1  4982.5 5062.61
Encroach Node=26015
       1    4992    5035
Encroach Node=25700
       1    4941    5013
Encroach Node=25543
       1    4955    5043
Encroach Node=25215
       1    4976    5027
Encroach Node=25111
       1  4986.8  5013.2
Encroach Node=25041
       1    4990    5035
Encroach Node=24315
       1    4983    5022
Encroach Node=24001
       1 4976.87    5075
Encroach Node=23493
       1  4981.8 5075.14
Encroach Node=22993
       1  4981.8    5029
Encroach Node=22629
       1  4981.8 5054.67
Encroach Node=21999
       1  4981.8    5035
Encroach Node=21515
       1    4965    5065
Encroach Node=20996
       1 4946.19 5098.02
Encroach Node=20342
       1    4960    5035
Encroach Node=19998
       1    4950    5050
Encroach Node=19449
       1    4950    5045
Encroach Node=19335
       1    4975    5025
Encroach Node=18999
       1    4987    5030
Encroach Node=18490
       1    4975    5050
Encroach Node=18242
       1    4929    5080
Encroach Node=17793
       1    4840  5019.4
Encroach Node=17515
       1    4945    5065
Encroach Node=17000
       1 4900.48    5099
Encroach Node=16497
       1    4930    5104
Encroach Node=16177
       1 4958.28    5050
Encroach Node=15814
       1  4980.6    5045
Encroach Node=15498
       1    4920    5050
Encroach Node=15333
       1 4817.61 5069.49
Encroach Node=14994
       1    4802    5100
Encroach Node=14289
       1 4831.53    5020
Encroach Node=13998
       1 4844.98 5036.67
Encroach Node=13497
       1 4881.05  5191.5
Encroach Node=13307
       1 4928.72 5054.88
Encroach Node=13111
       1 4918.72 5064.88
Encroach Node=12726
       1    4840 5105.59
Encroach Node=12212
       1    4960    5060
Encroach Node=11764
       1 4876.59 5083.77
Encroach Node=11495
       1 4835.16    5020
Encroach Node=11137
       1 4808.14    5020
Encroach Node=10795
       1    4906    5094
Encroach Node=10627
       1 4870.28 5115.28
Encroach Node=10420
       1 4884.56 5066.13
Encroach Node=10000
       1 4845.78 5173.34
Encroach Node=9629
       1 4929.62    5100
Encroach Node=9137
       1  4880.7 5119.98
Encroach Node=8814
       1    4925    5055
Encroach Node=8700
       1    4860    5060
Encroach Node=8504
       1    4790    5230
Encroach Node=8264
       1    4880    5120
Encroach Node=7995
       1 4867.22 5063.21
Encroach Node=7519
       1  4778.1 5094.39
Encroach Node=6901
       1  4978.7 5185.91
Encroach Node=6226
       1 4947.81 5078.06
Encroach Node=5748
       1 4834.26 5089.57
Encroach Node=5330
       1 4811.34  5021.3
Encroach Node=5000
       1 4718.37 5065.64
Encroach Node=4493
       1 4807.31  5217.3
Encroach Node=4003
       1    4850    5050
Encroach Node=3674
       1    4942    5042
Encroach Node=3499
       1    4910    5050
Encroach Node=2815
       1    4750  5021.3
Encroach Node=2348
       1 4822.95  5021.3
Encroach Node=2024
       1 4753.55  5021.3
Encroach Node=1511
       1  4820.2 5223.53
Encroach Node=898
       1 4780.19  5021.3
Encroach Node=745
       1 4834.89  5021.3
BEGIN DESCRIPTION:
Floodway Run
END DESCRIPTION:
Computation Interval=1HOUR
Output Interval=1HOUR
Run HTab= 0
Run UNet= 0
Run PostProcess= 0
UNET Theta= 1
UNET Theta Warmup= 1
UNET ZTol= 0.02
UNET ZSATol= 0.05
UNET MxIter= 20
UNET MaxInSteps= 0
UNET DtIC= 0
UNET DtMin= 0
UNET MaxCRTS= 20
UNET WFStab= 2
UNET SFStab= 1
UNET WFX= 1
UNET SFX= 1
UNET DSS MLevel= 4
UNET DZMax Abort= 100
UNET Convert EG Bridges=-1
UNET Use Existing IB Tables=-1
UNET Froude Reduction=False
UNET Froude Limit= 1
UNET Froude Power= 10
Instantaneous Interval=1HOUR
Write IC File= 0
Echo Input=False
Echo Output=False
Write Detailed= 0
Detailed Automatic Start=False, 10

--- Kerr Creek.f01 (steady flow) ---

Flow Title=Floodway
Number of Profiles=2
Profile Names=100-year,100-FW
River Rch & RM= Kerr Creek,Reach-1,39867
     488     488
River Rch & RM= Kerr Creek,Reach-1,36504
     651     651
River Rch & RM= Kerr Creek,Reach-1,33856
     906     906
River Rch & RM= Kerr Creek,Reach-1,32503
    1202    1202
River Rch & RM= Kerr Creek,Reach-1,29013
    1823    1823
River Rch & RM= Kerr Creek,Reach-1,27003
    2230    2230
River Rch & RM= Kerr Creek,Reach-1,24315
    2486    2486
River Rch & RM= Kerr Creek,Reach-1,20996
    2713    2713
River Rch & RM= Kerr Creek,Reach-1,18490
    2919    2919
River Rch & RM= Kerr Creek,Reach-1,14289
    3123    3123
River Rch & RM= Kerr Creek,Reach-1,10000
    3314    3314
River Rch & RM= Kerr Creek,Reach-1,6901
    3509    3509
Boundary for River Rch & Prof#=Kerr Creek,Reach-1,1
Up Type=0
Dn Type=3
Dn Slope=0.0017
Boundary for River Rch & Prof#=Kerr Creek,Reach-1,2
Up Type=0
Dn Type=3
Dn Slope=0.0017

--- Kerr Creek.g01 (geometry) ---

Geom Title=Existing Conditions

River Reach=Kerr Creek,Reach-1
Reach XY= 30
      1498864.65       668249.24      1498730.48       668854.55
      1498936.63       670326.88      1499262.38       670794.63
      1499593.63       672064.13      1499448.88       673795.75
      1499087.00       674303.81      1498985.63       674889.50
      1499414.88       675585.50      1501866.75       677488.63
      1502325.00       679062.88      1502675.38       681224.69
      1502750.25       681356.44      1502965.88       681323.50
      1504118.50       682922.31      1504307.13       683548.06
      1504394.00       684952.25      1505289.13       685106.44
      1505567.63       685546.56      1506600.50       686212.69
      1507376.00       687104.94      1507879.00       688946.25
      1508929.88       690754.63      1510139.50       693489.63
      1510471.75       694679.75      1511777.13       696030.06
      1512648.50       697542.00      1514205.38       699314.50
      1515510.75       699739.63      1516712.60       700573.39

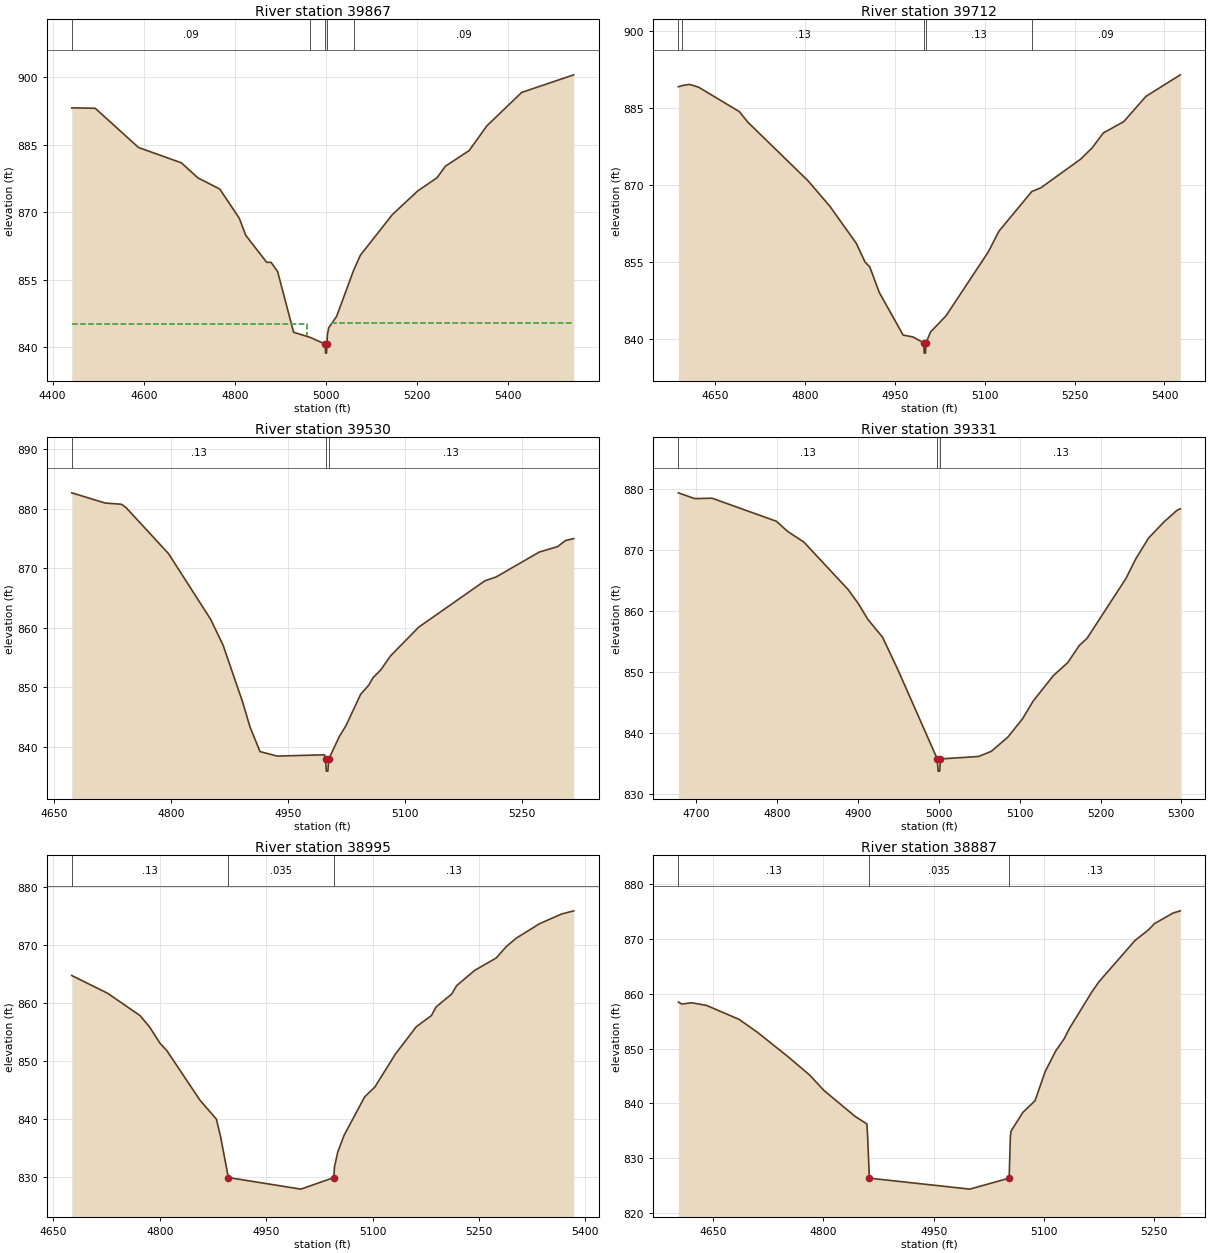
Type RM Length L Ch R = 1,39867,155,155,155
BEGIN DESCRIPTION:
Dam KC_11 (Kerr) ds
END DESCRIPTION:
XS GIS Cut Line= 4
      1498209.59       669199.00      1498714.32       669158.18
      1498768.13       669150.76      1499289.51       669007.89
#Sta/Elev= 30
  4442.1  893.15  4493.6  893.06  4588.5  884.35  4682.7  880.94  4718.8  877.60
  4766.8  875.12  4809.7  868.63  4823.7  864.86  4869.7  858.85  4879.4  858.83
  4893.7  856.80  4928.8  843.31  4965.7  842.15  4998.0  840.67  4999.0  838.67
  5001.0  838.67  5002.0  840.67  5002.8  842.64  5005.8  844.29  5023.2  846.84
  5060.5  857.06  5075.3  860.42  5145.2  869.41  5200.6  874.65  5243.6  877.64
  5261.8  880.19  5314.0  883.67  5352.8  889.15  5429.2  896.58  5543.4  900.49
#Mann=5,-1,0
  4442.1    0.09       0  4965.7    0.13       0  4998.0    0.05       0
  5002.0    0.13       0  5060.5    0.09       0
#XS Ineff=2,0
    0.00 4958.80  845.17 5012.00    0.00  845.34
Permanent Ineff=
       F       F
Bank Sta=4998,5002
XS Rating Curve= 0
Exp/Cntr=0.3,0.1

Type RM Length L Ch R = 1,39712,182,182,182
BEGIN DESCRIPTION:
Kerr Creek 84.0
END DESCRIPTION:
XS GIS Cut Line= 3
      1498396.60       669447.08      1498781.22       669304.58
      1499176.67       669141.29
#Sta/Elev= 30
  4588.5  889.22  4594.5  889.44  4606.8  889.68  4622.3  889.13  4690.2  884.38
  4704.7  882.29  4805.2  870.87  4841.8  865.87  4885.6  858.69  4900.2  855.04
  4908.0  854.12  4923.9  849.14  4963.7  840.82  4980.3  840.45  4998.0  839.30
  4999.0  837.30  5001.0  837.30  5002.0  839.30  5009.4  841.40  5035.4  844.58
  5105.9  857.02  5123.6  861.05  5178.5  868.79  5193.9  869.54  5260.0  875.10
  5279.0  877.27  5298.1  880.22  5332.1  882.42  5369.2  887.35  5426.5  891.54
#Mann=5,-1,0
  4588.5    0.09       0  4594.5    0.13       0  4998.0    0.05       0
  5002.0    0.13       0  5178.5    0.09       0
Bank Sta=4998,5002
XS Rating Curve= 0
Exp/Cntr=0.3,0.1

Type RM Length L Ch R = 1,39530,199,199,199
BEGIN DESCRIPTION:
Kerr Creek 83.0
END DESCRIPTION:
XS GIS Cut Line= 3
      1498527.68       669559.01      1498840.56       669472.34
      1499140.80       669362.39
#Sta/Elev= 30
  4672.2  882.68  4715.1  880.96  4736.0  880.76  4741.9  880.20  4796.5  872.45
  4850.5  861.43  4866.5  857.07  4891.6  847.51  4901.0  843.35  4913.9  839.20
  4935.9  838.45  4996.7  838.66  4998.0  837.92  4999.0  835.92  5001.0  835.92
  5002.0  837.92  5015.7  841.74  5024.1  843.53  5043.1  848.84  5053.5  850.37
  5058.8  851.59  5069.0  852.95  5081.4  855.28  5117.6  860.11  5202.7  867.91
  5216.9  868.54  5272.6  872.74  5295.9  873.64  5306.0  874.66  5316.6  875.00
#Mann=3,-1,0
  4672.2    0.13       0  4998.0    0.05       0  5002.0    0.13       0
Bank Sta=4998,5002
XS Rating Curve= 0
Exp/Cntr=0.3,0.1

Type RM Length L Ch R = 1,39331,336,336,336
BEGIN DESCRIPTION:
Kerr Creek 82.0
END DESCRIPTION:
XS GIS Cut Line= 3
      1498518.29       669665.49      1498838.44       669647.82
      1499135.79       669690.30
#Sta/Elev= 30
  4677.7  879.35  4698.0  878.40  4719.4  878.47  4799.0  874.69  4812.9  873.03
  4833.1  871.27  4887.9  863.48  4900.1  861.25  4912.2  858.61  4930.3  855.70
  4949.3  850.37  4998.0  835.76  4999.0  833.76  5001.0  833.76  5002.0  835.76
  5049.2  836.16  5064.8  837.00  5085.1  839.30  5103.5  842.33  5116.8  845.27
  5141.8  849.43  5159.4  851.53  5173.8  854.36  5183.3  855.51  5231.4  865.31
  5243.5  868.51  5259.4  871.94  5278.7  874.61  5294.8  876.51  5298.7  876.73
#Mann=3,-1,0
  4677.7    0.13       0  4998.0    0.05       0  5002.0    0.13       0
Bank Sta=4998,5002
XS Rating Curve= 0
Exp/Cntr=0.3,0.1

Type RM Length L Ch R = 1,38995,108,108,108
BEGIN DESCRIPTION:
Kerr Creek 81.0
END DESCRIPTION:
XS GIS Cut Line= 5
      1498652.37       669816.96      1498813.07       669979.77
      1498903.98       669975.54      1498958.96       669969.20
      1499240.16       669791.60
#Sta/Elev= 30
  4676.0  864.72  4726.6  861.65  4772.2  857.81  4785.8  855.83  4800.4  853.03
  4810.1  851.75  4856.6  843.23  4879.9  839.94  4885.8  836.91  4896.8  829.86
  4999.0  827.86  5045.6  829.86  5046.3  831.66  5051.1  834.29  5059.9  837.14
  5089.0  843.79  5103.3  845.47  5132.2  851.15  5161.7  855.88  5183.0  857.80
  5189.7  859.30  5211.7  861.53  5218.6  862.97  5244.1  865.61  5274.5  867.75
  5288.7  869.72  5302.4  871.14  5335.4  873.65  5366.6  875.33  5383.7  875.88
#Mann=3,-1,0
  4676.0    0.13       0  4896.8   0.035       0  5045.6    0.13       0
Bank Sta=4896.8,5045.6
XS Rating Curve= 0
Exp/Cntr=0.3,0.1

Type RM Length L Ch R = 1,38887,118,118,118
BEGIN DESCRIPTION:
Kerr Creek 80.0
END DESCRIPTION:
XS GIS Cut Line= 3
      1498547.94       670170.53      1498932.84       670080.14
      1499215.65       670030.57
#Sta/Elev= 30
  4602.8  858.48  4607.8  858.13  4620.8  858.36  4641.1  857.88  4685.4  855.33
  4710.5  852.96  4752.8  848.43  4781.7  845.13  4800.6  842.39  4843.0  837.65
  4859.2  836.25  4860.2  833.86  4862.5  826.37  4999.0  824.37  5052.6  826.37
  5054.2  833.96  5055.2  834.97  5071.1  838.35  5087.7  840.48  5101.7  845.85
  5116.0  849.60  5127.5  851.82  5134.2  853.60  5164.5  860.23  5174.4  862.15
  5223.6  869.71  5242.2  871.68  5250.1  872.79  5275.4  874.73  5285.3  875.13
#Mann=3,-1,0
  4602.8    0.13       0  4862.5   0.035       0  5052.6    0.13       0
Bank Sta=4862.5,5052.6
XS Rating Curve= 0
Exp/Cntr=0.5,0.3

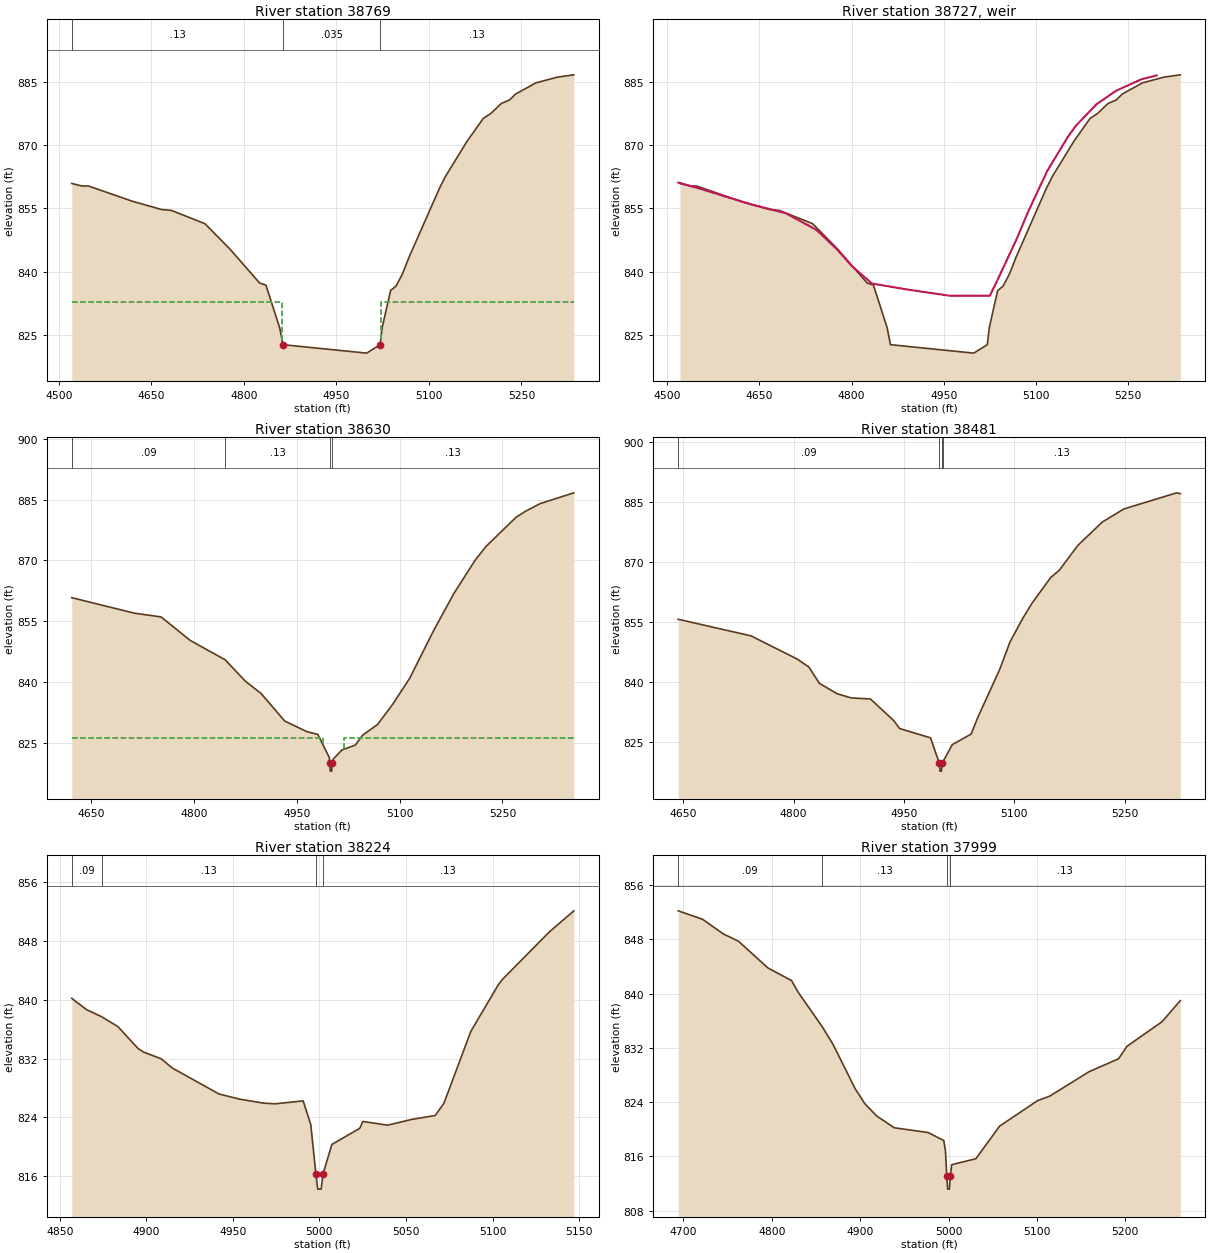
Type RM Length L Ch R = 1,38769,139,139,139
BEGIN DESCRIPTION:
Dam KC_10 (Kerr) us
END DESCRIPTION:
XS GIS Cut Line= 3
      1498508.48       670244.00      1498983.95       670187.25
      1499318.70       670208.87
#Sta/Elev= 30
  4520.7  860.91  4536.5  860.33  4548.0  860.30  4618.2  856.74  4666.2  854.75
  4682.3  854.54  4736.7  851.39  4777.4  845.36  4825.4  837.36  4835.6  836.86
  4857.9  826.77  4863.3  822.77  4999.0  820.77  5020.9  822.77  5024.1  826.79
  5037.8  835.59  5046.4  836.59  5056.9  839.47  5067.6  843.43  5117.1  859.78
  5127.2  862.68  5161.9  870.91  5188.2  876.31  5200.0  877.43  5217.5  879.84
  5230.7  880.66  5240.8  882.09  5273.4  884.70  5307.8  886.05  5335.0  886.61
#Mann=3,-1,0
  4520.7    0.13       0  4863.3   0.035       0  5020.9    0.13       0
#XS Ineff=2,0
    0.00 4862.00  832.79 5022.00    0.00  832.97
Permanent Ineff=
       F       F
Bank Sta=4863.3,5020.9
XS Rating Curve= 0
Exp/Cntr=0.5,0.3

Type RM Length L Ch R =5,38727,,,
BEGIN DESCRIPTION:
Dam KC_10 TOR (Kerr)
Structure ID: KC_10
Approximate Survey Structure
END DESCRIPTION:
#Inline Weir SE= 22
  4517.9  861.13  4553.6  859.67  4590.4  858.01  4637.2  855.94  4692.8  853.88
  4742.8  849.92  4775.7  845.43  4800.2  841.42  4833.0  837.24  4888.0  835.88
  4959.3  834.35  5025.0  834.34  5034.7  837.21  5068.1  847.59  5087.7  854.32
  5118.0  863.75  5152.1  871.97  5164.8  874.51  5197.9  879.57  5230.3  882.83
  5271.3  885.54  5296.7  886.47
IW Dist,WD,Coef,Skew,MaxSub,Min_El,Is_Ogee,SpillHt,DesHd
25,34,3,,0.95,,0,,,1,1

Type RM Length L Ch R = 1,38630,149,149,149
BEGIN DESCRIPTION:
Dam KC_10 (Kerr) ds
END DESCRIPTION:
XS GIS Cut Line= 3
      1498565.82       670366.31      1498936.32       670292.97
      1499285.73       670233.02
#Sta/Elev= 30
  4622.0  860.84  4713.1  857.03  4752.3  856.09  4794.8  850.30  4845.7  845.54
  4875.0  840.29  4898.4  837.19  4932.5  830.46  4965.1  827.82  4980.8  827.16
  4997.7  821.42  4998.0  820.11  4999.0  818.11  5001.0  818.11  5002.0  820.11
  5003.5  821.10  5015.9  823.31  5035.5  824.53  5046.0  826.94  5067.8  829.59
  5089.3  834.40  5114.9  841.01  5149.6  852.70  5179.4  861.91  5210.3  870.08
  5226.4  873.52  5270.1  880.67  5282.9  882.05  5305.0  884.01  5354.2  886.67
#Mann=4,-1,0
  4622.0    0.09       0  4845.7    0.13       0  4998.0    0.05       0
  5002.0    0.13       0
#XS Ineff=2,0
    0.00 4988.00  826.38 5019.70    0.00  826.32
Permanent Ineff=
       F       F
Bank Sta=4998,5002
XS Rating Curve= 0
Exp/Cntr=0.5,0.3

Type RM Length L Ch R = 1,38481,257,257,257
BEGIN DESCRIPTION:
Kerr Creek 79.0
END DESCRIPTION:
XS GIS Cut Line= 3
      1498728.76       670613.69      1499017.39       670403.77
      1499297.28       670237.59
#Sta/Elev= 30
  4643.2  855.76  4742.0  851.62  4804.8  845.83  4820.7  843.83  4835.1  839.74
  4859.0  837.16  4878.6  836.09  4904.4  835.84  4936.3  830.40  4943.9  828.46
  4986.1  826.12  4998.0  819.80  4999.0  817.80  5001.0  817.80  5002.0  819.80
  5002.6  820.01  5015.7  824.42  5041.3  827.07  5050.5  831.28  5080.4  843.35
  5094.1  850.07  5111.6  856.04  5124.2  859.82  5149.3  866.16  5161.2  868.04
  5186.5  874.26  5219.6  880.07  5248.7  883.32  5320.6  887.37  5325.6  887.16
#Mann=4,-1,0
  4643.2    0.09       0  4998.0    0.05       0  5002.0    0.09       0
  5002.6    0.13       0
Bank Sta=4998,5002
XS Rating Curve= 0
Exp/Cntr=0.3,0.1

Type RM Length L Ch R = 1,38224,225,225,225
BEGIN DESCRIPTION:
Kerr Creek 78.5
END DESCRIPTION:
XS GIS Cut Line= 2
      1499041.02       670703.13      1499265.04       670518.81
#Sta/Elev= 30
  4856.9  840.22  4865.4  838.69  4874.1  837.72  4883.5  836.38  4895.2  833.39
  4898.4  832.90  4908.6  831.98  4914.9  830.74  4941.9  827.20  4953.6  826.50
  4967.9  825.94  4974.4  825.85  4990.6  826.25  4995.0  823.03  4998.0  816.23
  4999.0  814.23  5001.0  814.23  5002.0  816.23  5007.2  820.32  5023.3  822.51
  5025.1  823.45  5039.4  822.94  5053.2  823.72  5066.9  824.26  5071.9  825.91
  5087.5  835.73  5103.4  842.08  5105.7  842.79  5132.8  849.26  5147.0  852.14
#Mann=4,-1,0
  4856.9    0.09       0  4874.1    0.13       0  4998.0    0.05       0
  5002.0    0.13       0
Bank Sta=4998,5002
XS Rating Curve= 0
Exp/Cntr=0.3,0.1

Type RM Length L Ch R = 1,37999,303,303,303
BEGIN DESCRIPTION:
Kerr Creek 78.0
END DESCRIPTION:
XS GIS Cut Line= 3
      1498960.27       670835.28      1499260.55       670800.30
      1499525.03       670775.00
#Sta/Elev= 30
  4694.2  852.18  4721.7  850.94  4745.2  848.78  4762.3  847.71  4795.7  843.76
  4822.4  841.91  4829.8  840.20  4857.0  835.13  4869.3  832.51  4894.5  825.94
  4905.3  823.77  4918.5  821.98  4938.6  820.22  4976.8  819.52  4994.6  818.35
  4996.5  816.84  4998.0  813.18  4999.0  811.18  5001.0  811.18  5002.0  813.18
  5003.6  814.78  5030.9  815.66  5057.8  820.46  5100.6  824.21  5114.3  824.87
  5159.0  828.48  5192.3  830.38  5201.9  832.23  5241.6  835.85  5262.2  838.95
#Mann=4,-1,0
  4694.2    0.09       0  4857.0    0.13       0  4998.0    0.05       0
  5002.0    0.13       0
Bank Sta=4998,5002
XS Rating Curve= 0
Exp/Cntr=0.3,0.1

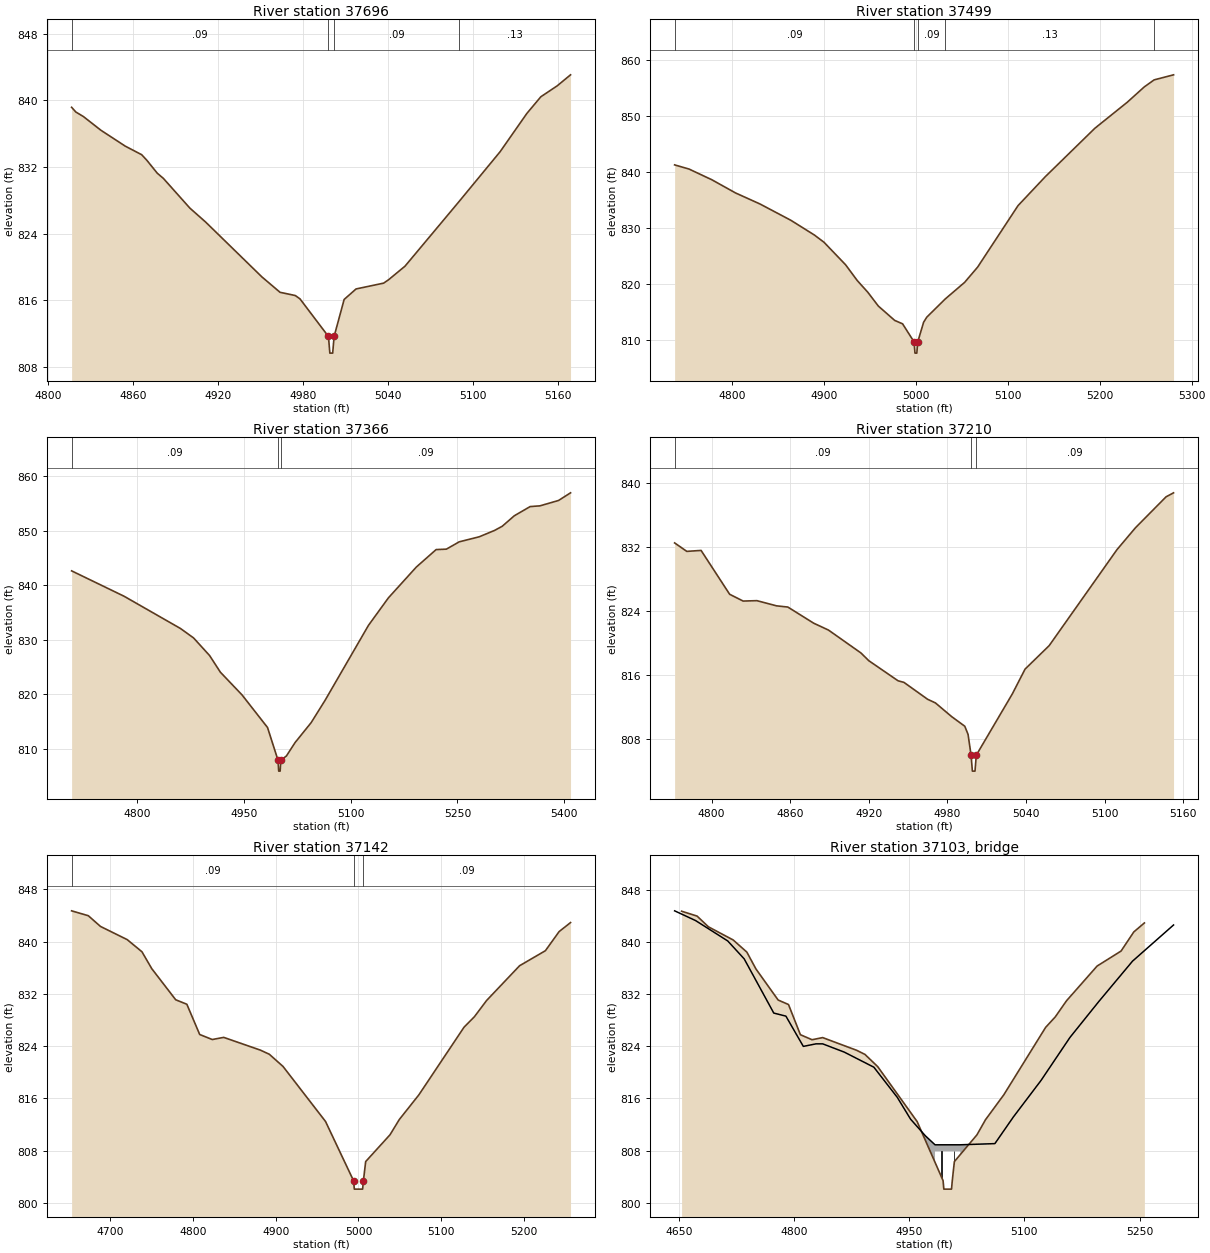
Type RM Length L Ch R = 1,37696,197,197,197
BEGIN DESCRIPTION:
Kerr Creek 77.5
END DESCRIPTION:
XS GIS Cut Line= 3
      1499162.93       671128.70      1499296.20       671100.35
      1499503.15       671037.98
#Sta/Elev= 30
  4816.6  839.17  4819.6  838.60  4824.9  838.06  4837.3  836.41  4854.4  834.51
  4866.1  833.47  4869.8  832.79  4877.1  831.25  4881.4  830.63  4900.1  827.06
  4911.2  825.39  4951.0  818.79  4963.8  816.94  4974.6  816.55  4977.9  816.15
  4998.0  811.63  4999.0  809.63  5001.0  809.63  5002.0  811.63  5009.1  816.08
  5017.5  817.34  5037.0  818.04  5040.5  818.45  5052.1  820.08  5090.0  827.79
  5119.3  833.84  5138.1  838.42  5148.0  840.43  5159.6  841.75  5169.0  843.07
#Mann=4,-1,0
  4816.6    0.09       0  4998.0    0.05       0  5002.0    0.09       0
  5090.0    0.13       0
Bank Sta=4998,5002
XS Rating Curve= 0
Exp/Cntr=0.3,0.1

Type RM Length L Ch R = 1,37499,133,133,133
BEGIN DESCRIPTION:
Kerr Creek 77.0
END DESCRIPTION:
XS GIS Cut Line= 3
      1499161.43       671360.68      1499409.25       671270.30
      1499639.59       671112.85
#Sta/Elev= 30
  4737.5  841.25  4753.3  840.50  4778.0  838.60  4803.8  836.25  4830.2  834.30
  4864.0  831.38  4889.7  828.74  4900.0  827.47  4923.5  823.46  4936.2  820.65
  4947.7  818.56  4959.1  816.11  4976.9  813.55  4985.5  812.94  4998.0  809.72
  4999.0  807.72  5001.0  807.72  5002.0  809.72  5008.4  813.22  5011.8  814.12
  5032.0  817.38  5053.0  820.32  5067.2  823.05  5111.1  833.99  5140.8  839.15
  5194.7  847.77  5229.9  852.40  5248.4  855.13  5259.2  856.39  5280.3  857.29
#Mann=5,-1,0
  4737.5    0.09       0  4998.0    0.05       0  5002.0    0.09       0
  5032.0    0.13       0  5259.2    0.09       0
Bank Sta=4998,5002
XS Rating Curve= 0
Exp/Cntr=0.3,0.1

Type RM Length L Ch R = 1,37366,156,156,156
BEGIN DESCRIPTION:
Kerr Creek 76.0
END DESCRIPTION:
XS GIS Cut Line= 3
      1499170.37       671449.86      1499455.82       671392.77
      1499853.28       671293.40
#Sta/Elev= 30
  4708.1  842.62  4781.7  837.97  4861.0  832.05  4879.4  830.32  4901.9  827.09
  4917.1  824.03  4947.6  819.85  4983.3  813.89  4998.0  807.89  4999.0  805.89
  5001.0  805.89  5002.0  807.89  5009.8  808.67  5022.0  811.13  5044.6  814.79
  5064.1  818.87  5125.1  832.63  5153.1  837.67  5192.3  843.32  5220.1  846.52
  5234.5  846.60  5252.5  847.94  5280.7  848.87  5302.1  850.03  5313.0  850.80
  5329.9  852.72  5352.2  854.41  5365.9  854.54  5392.1  855.53  5408.9  856.93
#Mann=3,-1,0
  4708.1    0.09       0  4998.0    0.05       0  5002.0    0.09       0
Bank Sta=4998,5002
XS Rating Curve= 0
Exp/Cntr=0.3,0.1

Type RM Length L Ch R = 1,37210,68,68,68
BEGIN DESCRIPTION:
Kerr Creek 75.5
END DESCRIPTION:
XS GIS Cut Line= 3
      1499307.51       671534.15      1499503.17       671531.31
      1499681.80       671483.11
#Sta/Elev= 30
  4771.8  832.50  4781.1  831.44  4792.0  831.56  4813.8  826.07  4824.1  825.22
  4834.6  825.27  4849.6  824.62  4858.2  824.47  4877.9  822.45  4889.2  821.59
  4914.0  818.72  4920.0  817.75  4942.3  815.24  4946.8  815.04  4964.8  812.93
  4970.8  812.47  4983.3  810.74  4993.2  809.55  4995.7  808.53  4998.0  805.93
  4999.0  803.93  5001.0  803.93  5002.0  805.93  5029.5  813.60  5039.2  816.70
  5057.6  819.64  5109.3  831.65  5123.4  834.39  5146.8  838.27  5152.5  838.77
#Mann=3,-1,0
  4771.8    0.09       0  4998.0    0.05       0  5002.0    0.09       0
Bank Sta=4998,5002
XS Rating Curve= 0
Exp/Cntr=0.5,0.3

Type RM Length L Ch R = 1,37142,82,82,82
BEGIN DESCRIPTION:
Upright Avenue (Kerr) us
END DESCRIPTION:
XS GIS Cut Line= 5
      1499198.94       671549.66      1499512.64       671584.09
      1499542.76       671589.26      1499564.58       671591.01
      1499798.91       671573.70
#Sta/Elev= 30
  4653.3  844.72  4673.5  843.97  4688.2  842.33  4720.5  840.31  4738.3  838.45
  4750.2  835.86  4779.1  831.10  4792.6  830.41  4808.1  825.78  4823.3  825.01
  4837.1  825.34  4881.4  823.39  4892.2  822.76  4908.8  820.89  4960.2  812.46
  4994.0  803.40  4995.0  802.10  5005.0  802.10  5006.0  803.40  5008.7  806.32
  5038.1  810.42  5049.3  812.75  5073.0  816.54  5127.6  826.90  5140.1  828.50
  5154.8  830.98  5194.7  836.31  5225.9  838.61  5242.5  841.54  5256.3  842.92
#Mann=3,-1,0
  4653.3    0.09       0  4994.0    0.05       0  5006.0    0.09       0
#XS Ineff=2,0
    0.00 4953.60  808.90 5046.40    0.00  808.90
Permanent Ineff=
       F       F
Bank Sta=4994,5006
XS Rating Curve= 0
Exp/Cntr=0.5,0.3

Type RM Length L Ch R =3,37103,,,
BEGIN DESCRIPTION:
Upright Avenue TOR (Kerr)
Structure ID: LDS_KC_09
Approximate Survey Structure
END DESCRIPTION:
Bridge Culvert--1,0,-1,-1,0
Deck Dist Width WeirC Skew NumUp NumDn MinLoCord MaxHiCord MaxSubmerge Is_Ogee
34.5,9,3,,25,25,,,,0,1,1,,,
  4644.2  4671.6  4713.4  4734.8  4773.4  4789.2  4811.9  4828.4  4837.1  4865.3
  4903.8  4934.3  4951.7  4971.0  4983.5  4983.5  5016.5  5016.5  5061.5  5085.6
  5121.7  5159.3  5196.9  5240.9  5294.3
  844.78  843.28  840.16  837.42  829.10  828.63  823.99  824.38  824.38  823.11
  820.80  816.18  812.82  810.27  808.90  808.90  808.90  808.90  809.08  813.17
  818.78  825.36  830.87  837.07  842.61
  782.10  782.10  782.10  782.10  782.10  782.10  782.10  782.10  782.10  782.10
  782.10  782.10  782.10  782.10  782.10  807.90  807.90  782.10  782.10  782.10
  782.10  782.10  782.10  782.10  782.10
  4644.2  4671.6  4713.4  4734.8  4773.4  4789.2  4811.9  4828.4  4837.1  4865.3
  4903.8  4934.3  4951.7  4971.0  4983.5  4983.5  5016.5  5016.5  5061.5  5085.6
  5121.7  5159.3  5196.9  5240.9  5294.3
  844.78  843.28  840.16  837.42  829.10  828.63  823.99  824.38  824.38  823.11
  820.80  816.18  812.82  810.27  808.90  808.90  808.90  808.90  809.08  813.17
  818.78  825.36  830.87  837.07  842.61
  782.10  782.10  782.10  782.10  782.10  782.10  782.10  782.10  782.10  782.10
  782.10  782.10  782.10  782.10  782.10  807.90  807.90  782.10  782.10  782.10
  782.10  782.10  782.10  782.10  782.10
Pier Skew, UpSta & Num, DnSta & Num=,4991.8,2,4991.8,2,0,0,0,0,0
       1       1
  804.00  807.90
       1       1
  803.00  807.90
Pier Skew, UpSta & Num, DnSta & Num=,5008.3,2,5008.3,2,0,0,0,0,0
       1       1
  805.50  807.90
       1       1
  803.00  807.90
BR Coef=1,1,0,1.25,0,,,0.8,0,2,0,
WSPro=,,,, 1 ,,,, 0 ,,,, 0 ,,,,-1 ,-1 ,-1 , 0 , 0 , 0 , 0 , 0
BC Design=,,0,,0,,,,,,

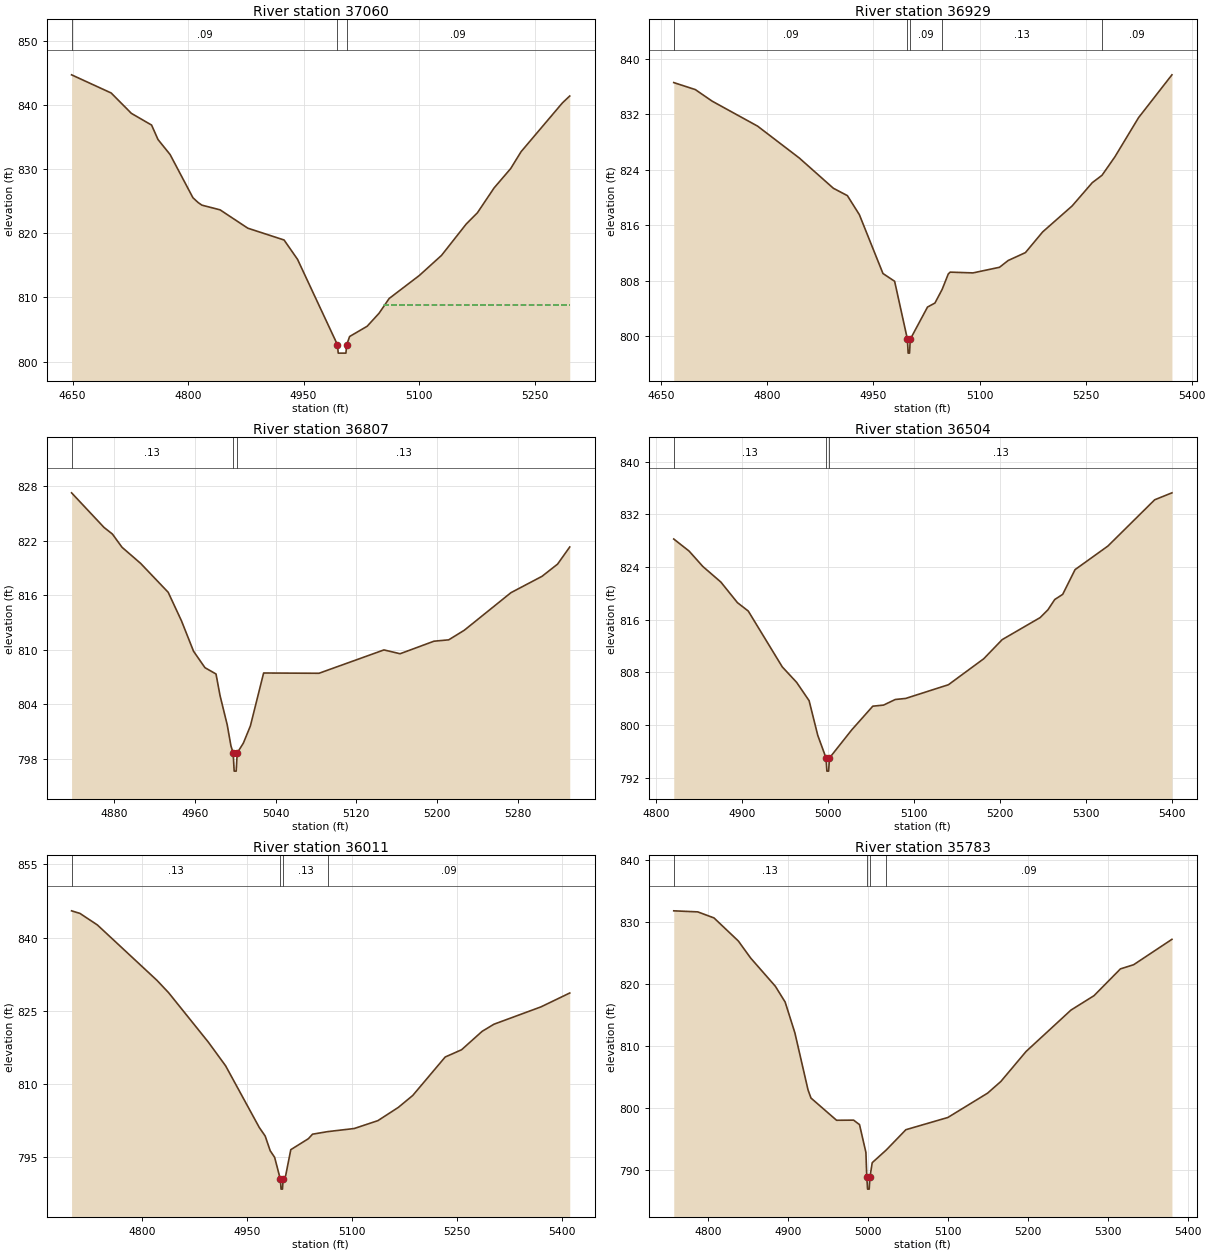
Type RM Length L Ch R = 1,37060,131,131,131
BEGIN DESCRIPTION:
Upright Avenue (Kerr) ds
END DESCRIPTION:
XS GIS Cut Line= 5
      1499180.33       671612.18      1499458.73       671635.87
      1499525.87       671669.74      1499578.16       671694.17
      1499800.50       671619.70
#Sta/Elev= 30
  4648.8  844.68  4700.2  841.85  4726.5  838.67  4752.7  836.85  4761.0  834.60
  4776.7  832.26  4806.4  825.52  4813.1  824.78  4818.0  824.37  4841.6  823.64
  4877.6  820.78  4924.7  818.94  4942.2  815.92  4994.0  802.61  4995.0  801.31
  5005.0  801.31  5006.0  802.61  5009.8  803.90  5032.6  805.50  5048.0  807.52
  5061.1  809.82  5100.4  813.42  5129.1  816.54  5161.2  821.43  5175.7  823.18
  5197.4  827.06  5218.9  830.07  5232.4  832.70  5286.1  840.31  5295.6  841.38
#Mann=3,-1,0
  4648.8    0.09       0  4994.0    0.05       0  5006.0    0.09       0
#XS Ineff=2,0
       0                 5054.10    0.00  808.86
Permanent Ineff=
       F       F
Bank Sta=4994,5006
XS Rating Curve= 0
Exp/Cntr=0.5,0.3

Type RM Length L Ch R = 1,36929,122,122,122
BEGIN DESCRIPTION:
Kerr Creek 75.0
END DESCRIPTION:
XS GIS Cut Line= 4
      1499155.56       671805.06      1499483.31       671794.49
      1499593.25       671788.15      1499821.63       671650.70
#Sta/Elev= 30
  4667.5  836.60  4698.0  835.59  4721.8  833.92  4786.0  830.32  4845.1  825.71
  4893.2  821.35  4913.1  820.28  4930.0  817.54  4963.4  809.04  4979.9  807.92
  4998.0  799.55  4999.0  797.55  5001.0  797.55  5002.0  799.55  5026.4  804.20
  5036.9  804.78  5047.1  806.75  5055.8  808.98  5058.5  809.24  5090.7  809.13
  5128.2  809.94  5140.5  810.92  5164.9  812.06  5189.3  815.05  5230.9  818.79
  5259.4  822.15  5273.2  823.22  5291.4  825.88  5324.9  831.54  5372.1  837.72
#Mann=5,-1,0
  4667.5    0.09       0  4998.0    0.05       0  5002.0    0.09       0
  5047.1    0.13       0  5273.2    0.09       0
Bank Sta=4998,5002
XS Rating Curve= 0
Exp/Cntr=0.3,0.1

Type RM Length L Ch R = 1,36807,303,303,303
BEGIN DESCRIPTION:
Kerr Creek 74.5
END DESCRIPTION:
XS GIS Cut Line= 3
      1499347.23       671959.44      1499582.56       671891.39
      1499766.88       671724.08
#Sta/Elev= 30
  4837.8  827.27  4869.9  823.47  4878.3  822.73  4887.8  821.28  4906.3  819.50
  4933.6  816.32  4946.8  813.17  4958.7  809.84  4970.0  808.03  4981.0  807.33
  4985.0  804.95  4992.1  801.74  4995.8  799.42  4998.0  798.64  4999.0  796.64
  5001.0  796.64  5002.0  798.64  5008.1  799.72  5015.1  801.62  5028.2  807.44
  5083.1  807.41  5147.5  809.98  5163.5  809.56  5197.1  810.94  5211.7  811.09
  5227.2  812.15  5273.4  816.28  5304.2  818.08  5319.6  819.42  5331.7  821.31
#Mann=3,-1,0
  4837.8    0.13       0  4998.0    0.05       0  5002.0    0.13       0
Bank Sta=4998,5002
XS Rating Curve= 0
Exp/Cntr=0.3,0.1

Type RM Length L Ch R = 1,36504,493,493,493
BEGIN DESCRIPTION:
Kerr Creek 74.0
END DESCRIPTION:
XS GIS Cut Line= 3
      1499375.02       672125.01      1499552.11       672168.31
      1499928.23       672296.60
#Sta/Elev= 30
  4820.8  828.27  4838.7  826.43  4854.6  824.10  4875.6  821.73  4894.9  818.60
  4907.5  817.32  4947.1  808.83  4963.8  806.48  4978.3  803.70  4988.4  798.42
  4998.0  794.99  4999.0  792.99  5001.0  792.99  5002.0  794.99  5027.9  799.26
  5052.4  802.86  5065.0  803.03  5078.6  803.88  5090.7  804.04  5140.4  806.12
  5181.5  810.07  5203.0  812.98  5247.2  816.33  5256.2  817.51  5264.1  819.07
  5273.4  819.86  5287.8  823.62  5326.0  827.20  5380.4  834.23  5400.5  835.29
#Mann=3,-1,0
  4820.8    0.13       0  4998.0    0.05       0  5002.0    0.13       0
Bank Sta=4998,5002
XS Rating Curve= 0
Exp/Cntr=0.3,0.1

Type RM Length L Ch R = 1,36011,228,228,228
BEGIN DESCRIPTION:
Kerr Creek 73.0
END DESCRIPTION:
XS GIS Cut Line= 3
      1499224.98       672575.00      1499525.87       672612.07
      1499934.04       672635.40
#Sta/Elev= 30
  4699.6  845.46  4711.6  844.93  4736.5  842.57  4821.7  831.23  4838.3  828.71
  4894.9  818.63  4919.7  813.77  4967.8  801.16  4976.3  799.39  4983.5  796.38
  4989.8  795.04  4998.0  790.53  4999.0  788.53  5001.0  788.53  5002.0  790.53
  5005.5  791.23  5012.9  796.60  5038.0  798.84  5044.0  799.77  5065.5  800.29
  5103.6  800.93  5137.4  802.54  5166.6  805.25  5187.2  807.69  5233.6  815.56
  5257.0  817.04  5286.3  820.80  5303.2  822.26  5370.6  825.82  5411.6  828.65
#Mann=4,-1,0
  4699.6    0.13       0  4998.0    0.05       0  5002.0    0.13       0
  5065.5    0.09       0
Bank Sta=4998,5002
XS Rating Curve= 0
Exp/Cntr=0.3,0.1

Type RM Length L Ch R = 1,35783,448,448,448
BEGIN DESCRIPTION:
Kerr Creek 72.0
END DESCRIPTION:
XS GIS Cut Line= 3
      1499319.52       672813.36      1499561.18       672835.32
      1499940.09       672868.27
#Sta/Elev= 30
  4756.6  831.74  4786.6  831.57  4806.9  830.60  4837.3  826.89  4852.8  824.13
  4883.6  819.60  4895.9  817.05  4908.1  812.08  4924.5  802.91  4928.2  801.59
  4960.2  798.01  4981.5  798.03  4988.9  797.31  4996.9  792.83  4998.0  788.92
  4999.0  786.92  5001.0  786.92  5002.0  788.92  5004.8  791.18  5022.4  793.23
  5046.9  796.49  5099.4  798.46  5149.1  802.38  5165.6  804.25  5197.2  809.09
  5253.3  815.75  5282.2  818.08  5315.2  822.39  5331.7  823.06  5379.6  827.15
#Mann=4,-1,0
  4756.6    0.13       0  4998.0    0.05       0  5002.0    0.13       0
  5022.4    0.09       0
Bank Sta=4998,5002
XS Rating Curve= 0
Exp/Cntr=0.3,0.1