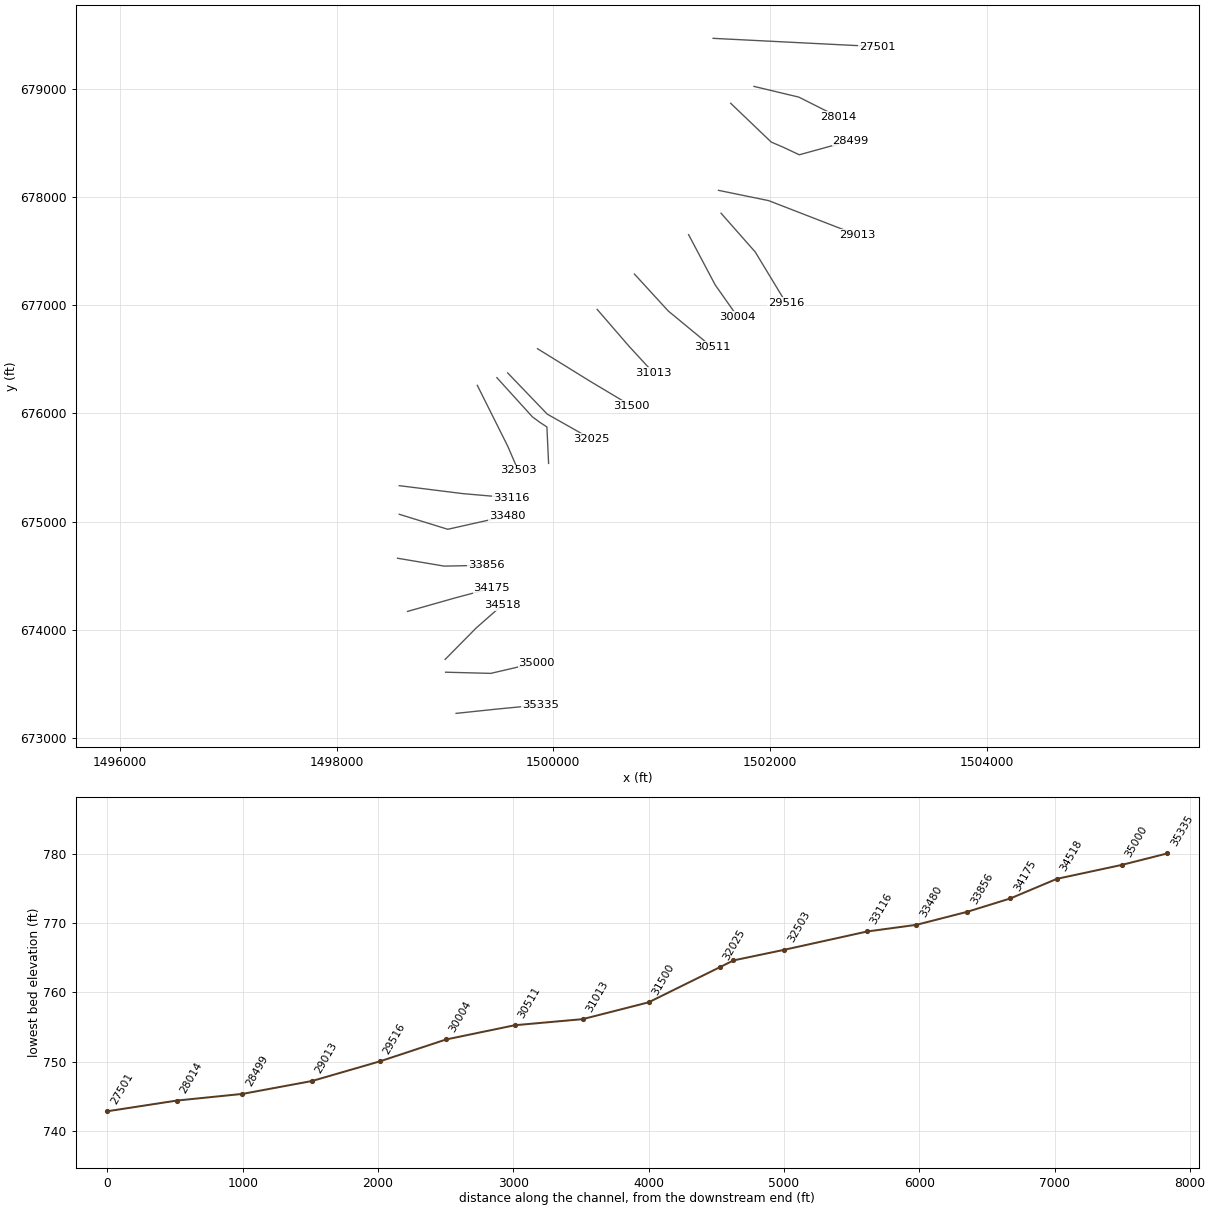
HEC-RAS study Kerr Creek.prj: .Kerr Creek Limited Detail Study

--- Kerr Creek.g01 (geometry) --- (continued)

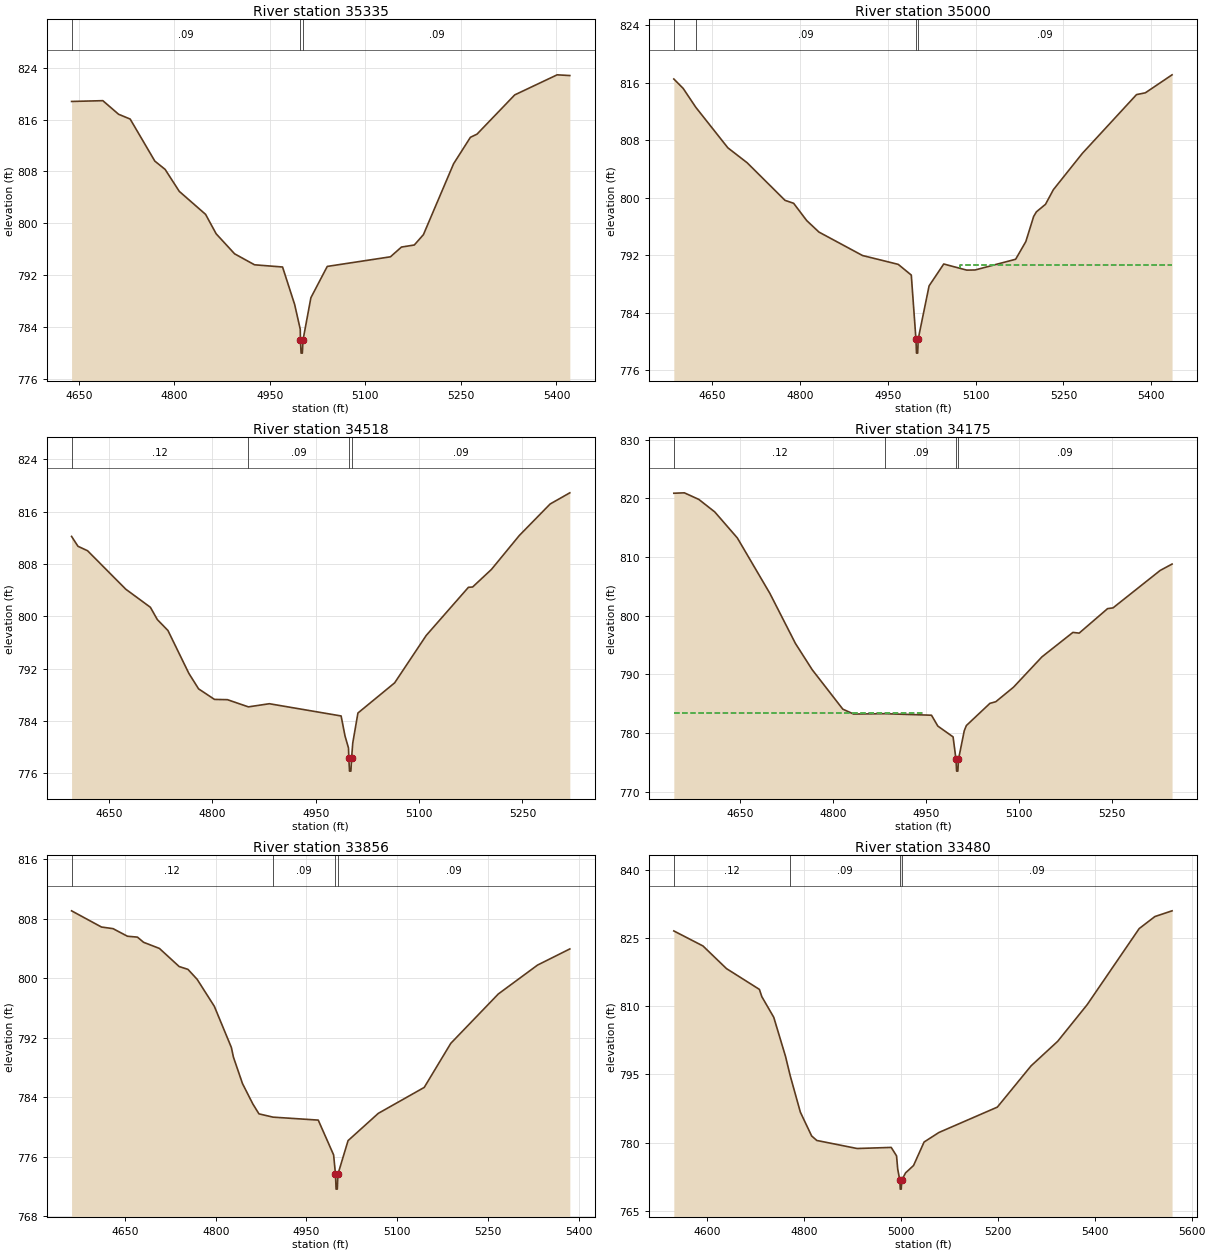
Type RM Length L Ch R = 1,35335,335,335,335
BEGIN DESCRIPTION:
Kerr Creek 71.0
END DESCRIPTION:
XS GIS Cut Line= 3
      1499103.12       673227.27      1499461.73       673265.17
      1499881.54       673305.99
#Sta/Elev= 30
  4638.6  818.78  4687.7  818.90  4712.4  816.81  4730.6  816.07  4769.4  809.59
  4785.5  808.32  4807.7  804.94  4849.1  801.39  4865.6  798.41  4894.6  795.32
  4925.9  793.63  4969.9  793.29  4988.9  787.52  4997.7  783.71  4998.0  782.03
  4999.0  780.03  5001.0  780.03  5002.0  782.03  5014.4  788.56  5040.1  793.38
  5139.3  794.86  5156.6  796.36  5176.8  796.68  5191.1  798.27  5238.5  809.19
  5264.9  813.26  5275.3  813.75  5334.5  819.79  5401.1  822.88  5421.0  822.77
#Mann=3,-1,0
  4638.6    0.09       0  4998.0   0.048       0  5002.0    0.09       0
Bank Sta=4998,5002
XS Rating Curve= 0
Exp/Cntr=0.3,0.1

Type RM Length L Ch R = 1,35000,482,482,482
BEGIN DESCRIPTION:
Kerr Creek 70.0
END DESCRIPTION:
XS GIS Cut Line= 3
      1499006.27       673607.83      1499422.66       673596.97
      1499845.67       673695.20
#Sta/Elev= 30
  4584.6  816.49  4600.6  815.18  4622.1  812.56  4676.9  806.92  4709.9  804.84
  4774.5  799.62  4789.2  799.21  4811.5  796.81  4832.4  795.21  4906.8  791.95
  4967.8  790.72  4990.1  789.23  4998.0  780.38  4999.0  778.38  5001.0  778.38
  5002.0  780.38  5020.5  787.73  5045.5  790.77  5084.8  789.92  5099.1  789.94
  5168.3  791.43  5185.7  793.89  5199.0  797.37  5203.7  798.02  5219.3  799.07
  5232.7  801.10  5282.2  806.15  5374.7  814.32  5389.8  814.57  5435.4  817.07
#Mann=4,-1,0
  4584.6    0.12       0  4622.1    0.09       0  4998.0   0.048       0
  5002.0    0.09       0
#XS Ineff=2,0
       0                 5073.00    0.00  790.70
Permanent Ineff=
       F       F
Bank Sta=4998,5002
XS Rating Curve= 0
Exp/Cntr=0.3,0.1

Type RM Length L Ch R = 1,34518,343,343,343
BEGIN DESCRIPTION:
Kerr Creek 69.0
END DESCRIPTION:
XS GIS Cut Line= 3
      1499001.95       673726.10      1499288.54       674016.82
      1499525.02       674225.02
#Sta/Elev= 30
  4595.5  812.23  4604.8  810.72  4618.7  810.04  4674.2  804.16  4709.9  801.40
  4720.0  799.52  4735.4  797.85  4765.8  791.29  4779.9  788.93  4803.0  787.32
  4821.7  787.28  4852.2  786.18  4882.6  786.66  4986.8  784.79  4992.4  781.76
  4997.5  779.89  4998.0  778.36  4999.0  776.36  5001.0  776.36  5002.0  778.36
  5003.7  780.66  5011.2  785.24  5064.5  789.85  5110.3  797.09  5171.6  804.45
  5177.7  804.50  5204.9  807.17  5245.5  812.37  5290.2  817.18  5318.8  818.89
#Mann=4,-1,0
  4595.5    0.12       0  4852.2    0.09       0  4998.0   0.048       0
  5002.0    0.09       0
Bank Sta=4998,5002
XS Rating Curve= 0
Exp/Cntr=0.3,0.1

Type RM Length L Ch R = 1,34175,319,319,319
BEGIN DESCRIPTION:
Kerr Creek 68.0
END DESCRIPTION:
XS GIS Cut Line= 3
      1498655.05       674169.76      1499099.89       674296.08
      1499429.35       674383.93
#Sta/Elev= 30
  4543.0  820.86  4560.0  820.93  4583.3  819.81  4609.0  817.68  4645.4  813.25
  4697.9  803.80  4739.1  795.28  4766.2  790.80  4815.5  784.09  4832.9  783.26
  4883.6  783.32  4958.5  783.06  4968.7  781.21  4993.3  779.37  4998.0  775.54
  4999.0  773.54  5001.0  773.54  5002.0  775.54  5011.3  780.41  5014.7  781.30
  5052.7  785.08  5062.2  785.36  5090.8  787.84  5136.5  792.99  5186.5  797.16
  5196.6  797.04  5242.4  801.21  5251.2  801.34  5327.2  807.71  5346.4  808.80
#Mann=4,-1,0
  4543.0    0.12       0  4883.6    0.09       0  4998.0   0.048       0
  5002.0    0.09       0
#XS Ineff=2,0
    0.00 4945.50  783.43               0
Permanent Ineff=
       F       F
Bank Sta=4998,5002
XS Rating Curve= 0
Exp/Cntr=0.3,0.1

Type RM Length L Ch R = 1,33856,376,376,376
BEGIN DESCRIPTION:
Kerr Creek 67.0
END DESCRIPTION:
XS GIS Cut Line= 3
      1498562.58       674661.17      1498994.06       674588.29
      1499380.09       674596.30
#Sta/Elev= 30
  4561.7  809.07  4611.1  806.89  4630.3  806.67  4654.0  805.65  4670.6  805.53
  4680.8  804.83  4706.9  804.01  4739.6  801.57  4754.1  801.19  4769.3  799.85
  4797.7  796.22  4825.9  790.67  4829.3  789.37  4844.3  785.81  4861.4  783.07
  4871.5  781.74  4894.7  781.30  4969.5  780.90  4994.9  776.22  4998.0  773.61
  4999.0  771.61  5001.0  771.61  5002.0  773.61  5018.8  778.14  5068.8  781.81
  5144.7  785.30  5188.6  791.23  5267.2  797.88  5332.1  801.77  5385.4  803.94
#Mann=4,-1,0
  4561.7    0.12       0  4894.7    0.09       0  4998.0   0.048       0
  5002.0    0.09       0
Bank Sta=4998,5002
XS Rating Curve= 0
Exp/Cntr=0.3,0.1

Type RM Length L Ch R = 1,33480,364,364,364
BEGIN DESCRIPTION:
Kerr Creek 66.0
END DESCRIPTION:
XS GIS Cut Line= 3
      1498578.19       675067.45      1499026.14       674928.83
      1499571.35       675051.29
#Sta/Elev= 30
  4531.9  826.62  4592.0  823.31  4640.5  818.32  4708.4  813.74  4713.4  812.14
  4738.0  807.60  4762.2  799.01  4772.0  794.70  4792.9  786.69  4816.2  781.44
  4826.9  780.45  4910.1  778.68  4980.3  778.92  4991.3  777.06  4993.7  774.16
  4998.0  771.73  4999.0  769.73  5001.0  769.73  5002.0  771.73  5010.0  773.32
  5026.4  774.94  5048.1  780.11  5078.7  782.21  5199.2  787.80  5268.7  796.88
  5323.6  802.29  5384.4  810.36  5491.8  827.14  5524.2  829.79  5559.6  831.05
#Mann=4,-1,0
  4531.9    0.12       0  4772.0    0.09       0  4998.0   0.048       0
  5002.0    0.09       0
Bank Sta=4998,5002
XS Rating Curve= 0
Exp/Cntr=0.3,0.1

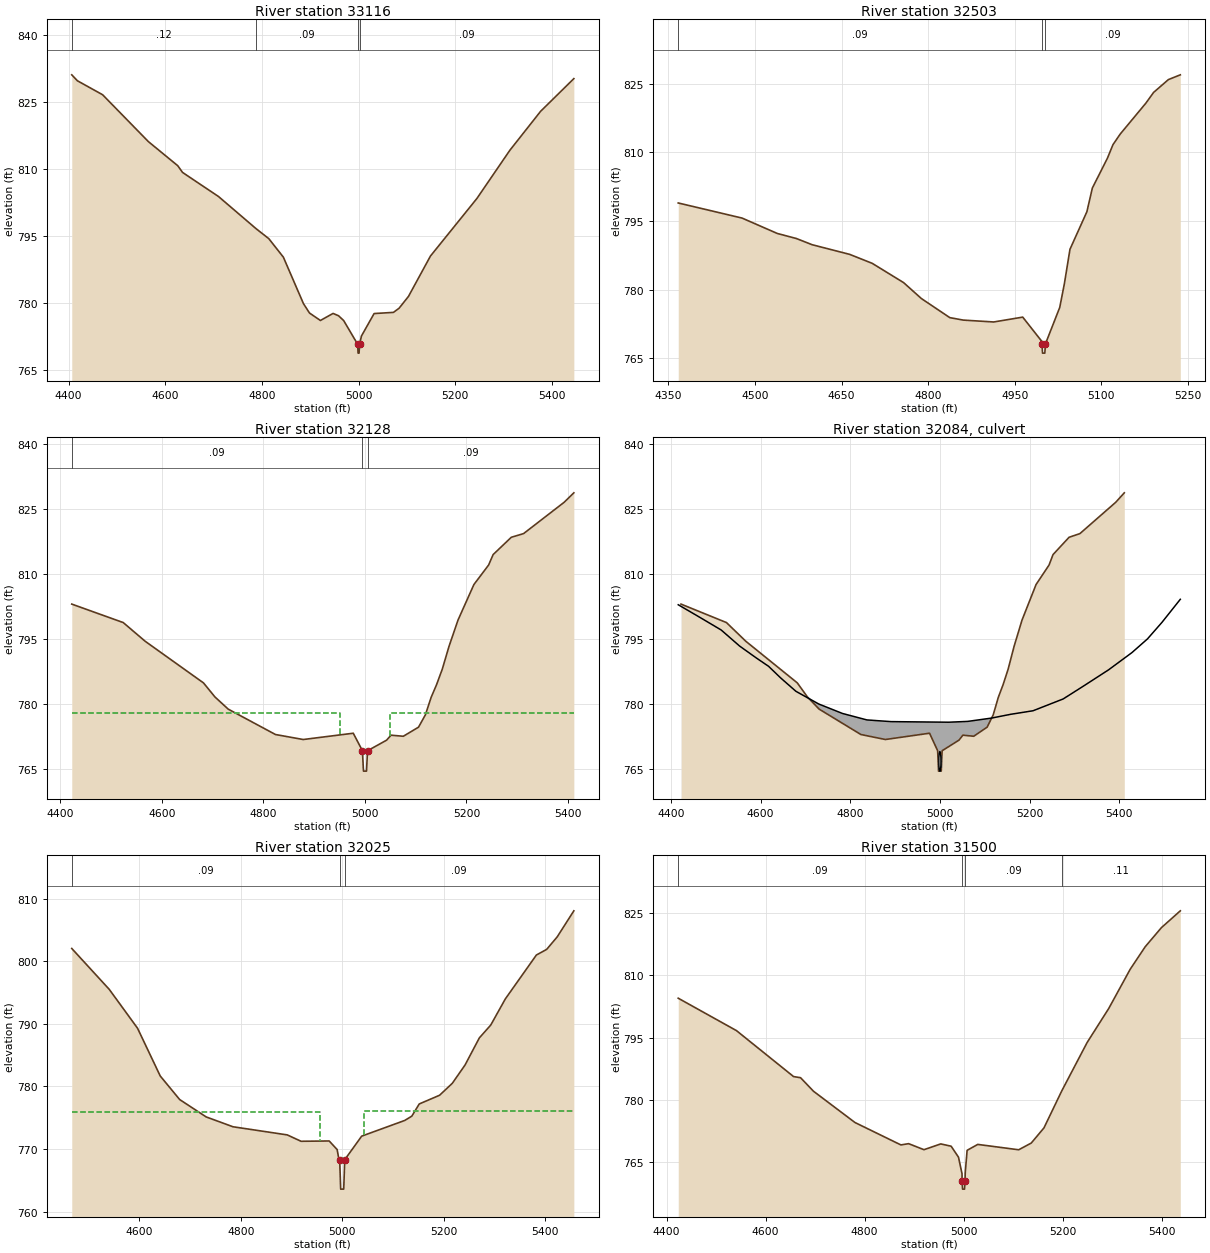
Type RM Length L Ch R = 1,33116,613,613,613
BEGIN DESCRIPTION:
Kerr Creek 65.0
END DESCRIPTION:
XS GIS Cut Line= 3
      1498578.21       675332.03      1499166.09       675258.30
      1499611.03       675219.70
#Sta/Elev= 30
  4406.4  831.01  4418.1  829.68  4470.3  826.55  4564.9  816.08  4625.8  810.68
  4635.7  809.18  4710.0  803.80  4787.9  796.60  4814.2  794.37  4844.3  790.24
  4885.9  779.84  4898.4  777.74  4921.0  776.07  4947.2  777.65  4958.5  777.13
  4969.1  776.06  4998.0  770.77  4999.0  768.77  5001.0  768.77  5002.0  770.77
  5005.9  772.59  5032.1  777.62  5072.1  777.88  5083.8  778.81  5103.3  781.46
  5148.8  790.49  5244.7  803.33  5313.1  814.14  5376.8  822.86  5445.5  830.16
#Mann=4,-1,0
  4406.4    0.12       0  4787.9    0.09       0  4998.0   0.048       0
  5002.0    0.09       0
Bank Sta=4998,5002
XS Rating Curve= 0
Exp/Cntr=0.3,0.1

Type RM Length L Ch R = 1,32503,375,375,375
BEGIN DESCRIPTION:
Kerr Creek 64.0
END DESCRIPTION:
XS GIS Cut Line= 3
      1499298.99       676258.71      1499580.10       675695.64
      1499674.99       675475.02
#Sta/Elev= 30
  4367.1  798.95  4477.6  795.65  4538.8  792.28  4571.5  791.19  4599.2  789.82
  4663.9  787.72  4703.0  785.76  4757.3  781.55  4788.2  778.06  4837.4  773.89
  4860.7  773.35  4913.5  772.94  4963.7  774.00  4996.4  768.76  4997.0  768.13
  4998.0  766.13  5002.0  766.13  5003.0  768.13  5027.8  776.12  5035.8  781.28
  5045.5  788.82  5074.8  797.03  5084.3  802.22  5110.4  808.74  5120.0  811.70
  5132.5  814.01  5177.1  820.79  5190.3  823.11  5216.0  825.92  5236.6  826.96
#Mann=3,-1,0
  4367.1    0.09       0  4997.0   0.048       0  5003.0    0.09       0
Bank Sta=4997,5003
XS Rating Curve= 0
Exp/Cntr=0.5,0.3

Type RM Length L Ch R = 1,32128,103,103,103
BEGIN DESCRIPTION:
Corriher Springs Road (Kerr) us
END DESCRIPTION:
XS GIS Cut Line= 5
      1499479.32       676330.18      1499806.94       675968.24
      1499880.41       675914.31      1499941.11       675874.63
      1499956.71       675537.64
#Sta/Elev= 30
  4422.3  803.12  4523.7  798.86  4566.9  794.55  4681.8  784.95  4704.3  781.72
  4730.5  778.90  4823.7  773.04  4878.4  771.89  4976.9  773.34  4995.0  769.30
  4997.0  764.60  5003.0  764.60  5005.0  769.30  5042.6  771.74  5051.3  772.89
  5075.5  772.64  5105.5  774.74  5119.0  777.58  5130.3  781.60  5141.0  784.53
  5152.3  788.12  5165.6  793.39  5183.3  799.44  5214.6  807.63  5243.6  812.13
  5252.5  814.54  5288.3  818.53  5312.5  819.38  5392.3  826.59  5411.5  828.78
#Mann=3,-1,0
  4422.3    0.09       0  4995.0   0.048       0  5005.0    0.09       0
#XS Ineff=2,0
    0.00 4950.00  778.00 5050.00    0.00  778.00
Permanent Ineff=
       F       F
Bank Sta=4995,5005
XS Rating Curve= 0
Exp/Cntr=0.5,0.3

Type RM Length L Ch R =2,32084,,,
BEGIN DESCRIPTION:
Corriher Springs Road TOR (Kerr)
Structure ID: LDS_KC_07
Approximate Survey Structure
END DESCRIPTION:
Bridge Culvert--1,0,-1,-1,0
Deck Dist Width WeirC Skew NumUp NumDn MinLoCord MaxHiCord MaxSubmerge Is_Ogee
26.5,35,3,,24,24,,,,0,1,1,,,
  4416.1  4459.6  4511.9  4553.1  4590.7  4617.6  4644.7  4678.8  4729.9  4782.6
  4837.1  4890.6  5019.7  5062.1  5114.9  5158.8  5207.8  5275.0  5317.6  5376.0
  5428.5  5463.2  5495.5  5536.5
  802.97  800.35  797.15  793.44  790.67  788.78  786.09  783.00  780.07  777.90
  776.41  776.02  775.88  776.07  776.83  777.72  778.52  781.24  784.03  787.93
  791.93  795.09  798.90  804.23
  740.80  740.80  740.80  740.80  740.80  740.80  740.80  740.80  740.80  740.80
  740.80  740.80  740.80  740.80  740.80  740.80  740.80  740.80  740.80  740.80
  740.80  740.80  740.80  740.80
  4416.1  4459.6  4511.9  4553.1  4590.7  4617.6  4644.7  4678.8  4729.9  4782.6
  4837.1  4890.6  5019.7  5062.1  5114.9  5158.8  5207.8  5275.0  5317.6  5376.0
  5428.5  5463.2  5495.5  5536.5
  802.97  800.35  797.15  793.44  790.67  788.78  786.09  783.00  780.07  777.90
  776.41  776.02  775.88  776.07  776.83  777.72  778.52  781.24  784.03  787.93
  791.93  795.09  798.90  804.23
  740.62  740.62  740.62  740.62  740.62  740.62  740.62  740.62  740.62  740.62
  740.62  740.62  740.62  740.62  740.62  740.62  740.62  740.62  740.62  740.62
  740.62  740.62  740.62  740.62
Culvert=1,4.5,,35,0.012,0.2,1,1,3,764.6,5000,763.6,5000,Culvert #1,0,26.5
Culvert Bottom n=0.012
Culvert Bottom Depth=0
Culvert Depth Blocked=0
BC Design=,,0,,0,,,,,,

Type RM Length L Ch R = 1,32025,525,525,525
BEGIN DESCRIPTION:
Corriher Springs (Kerr) ds
END DESCRIPTION:
XS GIS Cut Line= 3
      1499579.18       676373.85      1499944.56       675993.04
      1500346.77       675765.41
#Sta/Elev= 30
  4466.8  802.03  4540.7  795.50  4596.5  789.29  4641.2  781.67  4679.6  777.90
  4731.8  775.13  4784.6  773.56  4891.6  772.26  4918.9  771.24  4974.3  771.29
  4990.0  769.92  4994.5  767.91  4995.0  768.30  4997.0  763.60  5003.0  763.60
  5005.0  768.30  5038.4  772.06  5123.4  774.57  5137.3  775.26  5151.9  777.20
  5192.0  778.59  5217.1  780.50  5242.2  783.42  5270.4  787.75  5292.8  789.79
  5321.6  793.97  5382.8  800.98  5403.1  801.88  5423.9  803.88  5456.7  808.04
#Mann=3,-1,0
  4466.8    0.09       0  4995.0   0.048       0  5005.0    0.09       0
#XS Ineff=2,0
    0.00 4956.30  775.95 5043.80    0.00  776.03
Permanent Ineff=
       F       F
Bank Sta=4995,5005
XS Rating Curve= 0
Exp/Cntr=0.5,0.3

Type RM Length L Ch R = 1,31500,487,487,487
BEGIN DESCRIPTION:
Kerr Creek 63.0
END DESCRIPTION:
XS GIS Cut Line= 3
      1499854.32       676597.92      1500341.08       676296.26
      1500720.10       676069.54
#Sta/Elev= 30
  4423.6  804.45  4541.1  796.67  4656.6  785.61  4670.7  785.34  4696.8  782.09
  4780.7  774.56  4873.4  769.18  4889.0  769.48  4920.1  768.03  4953.9  769.42
  4974.9  768.87  4989.8  766.23  4996.9  762.26  4997.0  760.55  4998.0  758.55
  5002.0  758.55  5003.0  760.55  5003.4  762.47  5007.2  767.88  5028.7  769.30
  5111.4  768.01  5136.8  769.63  5162.5  773.28  5198.3  782.14  5249.7  793.81
  5293.3  801.98  5336.7  811.42  5367.0  816.83  5399.6  821.40  5437.9  825.46
#Mann=4,-1,0
  4423.6    0.09       0  4997.0   0.048       0  5003.0    0.09       0
  5198.3    0.11       0
Bank Sta=4997,5003
XS Rating Curve= 0
Exp/Cntr=0.3,0.1

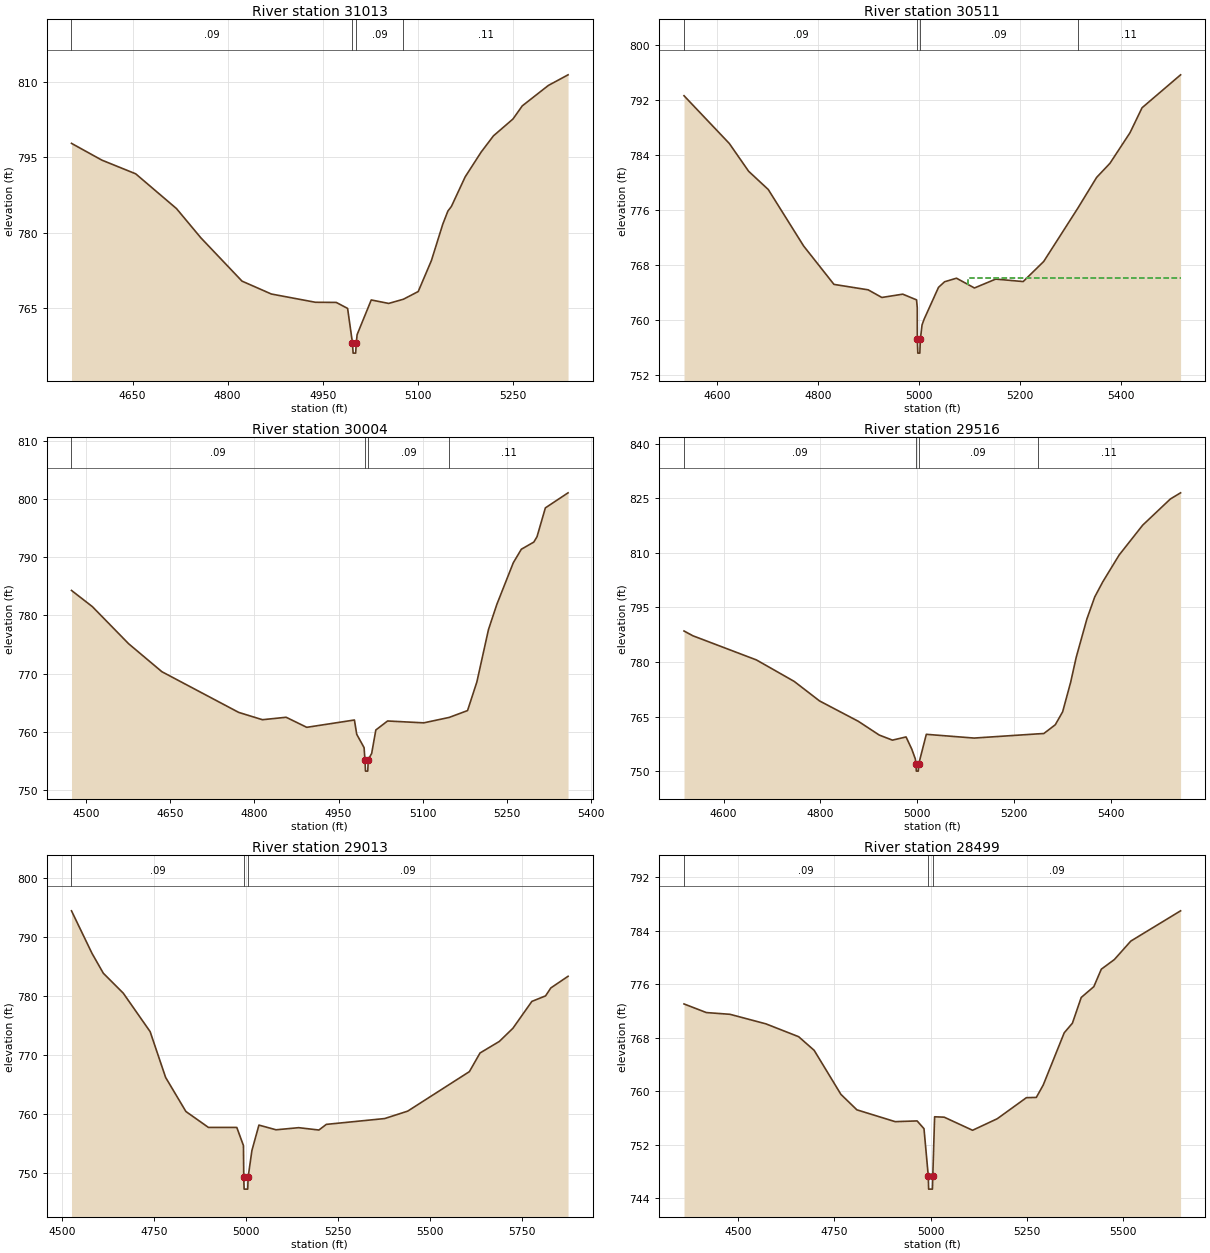
Type RM Length L Ch R = 1,31013,502,502,502
BEGIN DESCRIPTION:
Kerr Creek 62.0
END DESCRIPTION:
XS GIS Cut Line= 3
      1500405.25       676961.00      1500699.71       676619.90
      1500925.01       676374.98
#Sta/Elev= 30
  4553.7  797.79  4601.6  794.46  4655.0  791.74  4719.4  784.83  4757.8  779.03
  4822.7  770.43  4869.0  767.87  4938.5  766.23  4971.4  766.20  4989.3  765.01
  4997.0  758.13  4998.0  756.13  5002.0  756.13  5003.0  758.13  5004.3  759.80
  5026.6  766.69  5054.1  766.00  5077.3  766.83  5100.7  768.36  5121.5  774.51
  5139.4  781.72  5147.5  784.34  5153.0  785.25  5174.8  791.14  5200.1  796.08
  5219.4  799.28  5250.2  802.63  5264.9  805.24  5306.0  809.29  5337.1  811.40
#Mann=4,-1,0
  4553.7    0.09       0  4997.0   0.048       0  5003.0    0.09       0
  5077.3    0.11       0
Bank Sta=4997,5003
XS Rating Curve= 0
Exp/Cntr=0.3,0.1

Type RM Length L Ch R = 1,30511,507,507,507
BEGIN DESCRIPTION:
Kerr Creek 61.0
END DESCRIPTION:
XS GIS Cut Line= 3
      1500749.26       677287.59      1501061.24       676946.45
      1501463.62       676614.05
#Sta/Elev= 30
  4534.6  792.66  4624.4  785.72  4662.7  781.68  4701.6  779.03  4771.7  770.82
  4831.8  765.24  4899.6  764.45  4926.7  763.34  4968.1  763.82  4995.5  762.99
  4996.9  761.84  4997.0  757.25  4998.0  755.25  5002.0  755.25  5003.0  757.25
  5006.4  759.36  5010.6  760.20  5039.0  764.81  5051.0  765.62  5074.6  766.14
  5110.2  764.72  5152.4  766.01  5206.8  765.65  5247.5  768.57  5314.9  776.29
  5352.4  780.79  5378.8  782.84  5418.6  787.29  5442.4  790.91  5518.8  795.70
#Mann=4,-1,0
  4534.6    0.09       0  4997.0   0.048       0  5003.0    0.09       0
  5314.9    0.11       0
#XS Ineff=2,0
       0                 5098.00    0.00  766.13
Permanent Ineff=
       F       F
Bank Sta=4997,5003
XS Rating Curve= 0
Exp/Cntr=0.3,0.1

Type RM Length L Ch R = 1,30004,488,488,488
BEGIN DESCRIPTION:
Kerr Creek 60.0
END DESCRIPTION:
XS GIS Cut Line= 3
      1501249.03       677652.00      1501493.92       677188.44
      1501700.92       676893.99
#Sta/Elev= 30
  4474.5  784.30  4511.7  781.51  4576.3  775.12  4635.5  770.31  4772.2  763.31
  4814.5  762.05  4856.7  762.47  4893.4  760.74  4978.3  762.00  4982.4  759.54
  4995.5  757.24  4997.0  755.20  4998.0  753.20  5002.0  753.20  5003.0  755.20
  5009.0  756.24  5016.4  760.28  5037.3  761.83  5101.8  761.51  5146.9  762.44
  5179.7  763.62  5196.3  768.54  5217.0  777.57  5231.9  781.90  5261.2  789.07
  5275.5  791.39  5297.7  792.62  5303.4  793.54  5318.3  798.51  5358.7  801.10
#Mann=4,-1,0
  4474.5    0.09       0  4997.0   0.048       0  5003.0    0.09       0
  5146.9    0.11       0
Bank Sta=4997,5003
XS Rating Curve= 0
Exp/Cntr=0.3,0.1

Type RM Length L Ch R = 1,29516,503,503,503
BEGIN DESCRIPTION:
Kerr Creek 59.0
END DESCRIPTION:
XS GIS Cut Line= 3
      1501548.60       677850.04      1501864.21       677491.67
      1502147.68       677023.19
#Sta/Elev= 30
  4518.4  788.54  4536.8  787.22  4667.9  780.59  4745.8  774.70  4798.2  769.33
  4878.3  763.73  4921.4  759.96  4948.7  758.56  4976.8  759.44  4988.6  756.08
  4995.9  753.41  4997.0  752.05  4998.0  750.05  5002.0  750.05  5003.0  752.05
  5018.6  760.16  5117.2  759.13  5248.2  760.28  5261.2  760.38  5284.8  762.78
  5300.0  766.34  5316.5  774.43  5328.0  781.30  5350.1  791.85  5366.3  797.90
  5383.0  802.07  5416.7  809.42  5465.2  817.60  5522.5  824.81  5543.5  826.49
#Mann=4,-1,0
  4518.4    0.09       0  4997.0   0.048       0  5003.0    0.09       0
  5248.2    0.11       0
Bank Sta=4997,5003
XS Rating Curve= 0
Exp/Cntr=0.3,0.1

Type RM Length L Ch R = 1,29013,514,514,514
BEGIN DESCRIPTION:
Kerr Creek 58.0
END DESCRIPTION:
XS GIS Cut Line= 3
      1501524.96       678061.55      1501986.67       677966.92
      1502804.17       677649.70
#Sta/Elev= 30
  4526.4  794.49  4582.2  787.25  4612.8  783.89  4667.0  780.50  4739.9  773.97
  4782.0  766.18  4837.0  760.40  4898.3  757.69  4975.2  757.69  4993.3  754.61
  4994.1  749.21  4995.1  747.21  5004.9  747.21  5005.9  749.21  5016.2  753.76
  5035.3  758.09  5081.8  757.29  5143.2  757.65  5198.1  757.25  5218.3  758.21
  5376.7  759.20  5439.2  760.46  5606.7  767.17  5635.6  770.34  5688.0  772.30
  5724.9  774.54  5776.3  779.10  5813.5  780.04  5827.8  781.39  5874.6  783.37
#Mann=3,-1,0
  4526.4    0.09       0  4994.1   0.048       0  5005.9    0.09       0
Bank Sta=4994.1,5005.9
XS Rating Curve= 0
Exp/Cntr=0.3,0.1

Type RM Length L Ch R = 1,28499,485,485,485
BEGIN DESCRIPTION:
Kerr Creek 57.0
END DESCRIPTION:
XS GIS Cut Line= 5
      1501637.27       678866.54      1502011.66       678507.75
      1502123.70       678459.66      1502270.64       678390.32
      1502740.88       678520.19
#Sta/Elev= 30
  4359.2  773.07  4417.3  771.78  4478.7  771.52  4572.1  770.09  4657.1  768.17
  4697.6  766.12  4767.1  759.53  4808.6  757.22  4908.1  755.45  4965.1  755.56
  4983.0  754.40  4994.1  747.35  4995.1  745.35  5004.9  745.35  5005.9  747.35
  5010.6  756.18  5035.5  756.12  5109.3  754.16  5173.5  755.89  5249.2  759.04
  5275.0  759.08  5293.0  760.94  5347.5  768.75  5368.8  770.19  5391.7  774.04
  5424.5  775.66  5443.9  778.27  5477.9  779.72  5520.6  782.48  5650.0  787.01
#Mann=3,-1,0
  4359.2    0.09       0  4994.1   0.048       0  5005.9    0.09       0
Bank Sta=4994.1,5005.9
XS Rating Curve= 0
Exp/Cntr=0.3,0.1

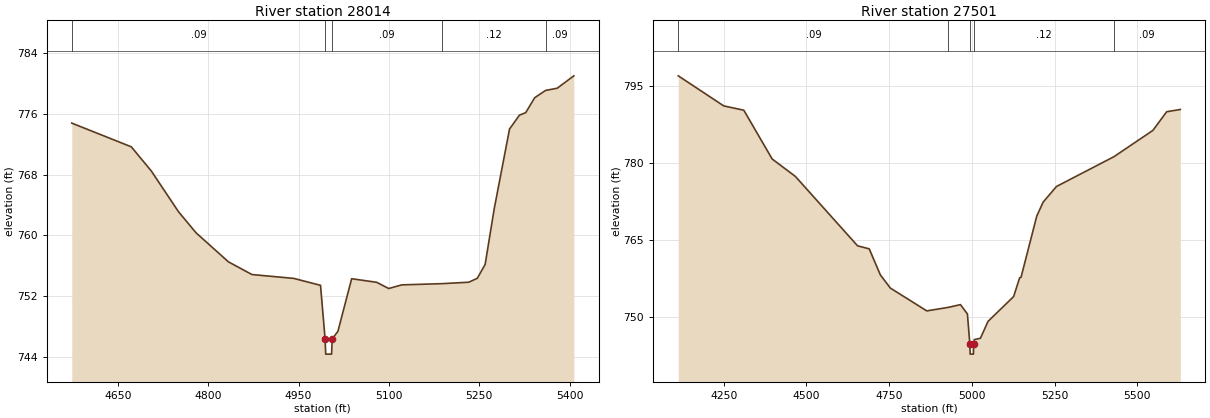
Type RM Length L Ch R = 1,28014,513,513,513
BEGIN DESCRIPTION:
Kerr Creek 56.0
END DESCRIPTION:
XS GIS Cut Line= 3
      1501852.55       679022.37      1502266.57       678923.24
      1502630.98       678739.58
#Sta/Elev= 30
  4573.4  774.78  4672.3  771.66  4705.6  768.47  4750.5  763.14  4779.8  760.35
  4833.6  756.53  4872.6  754.86  4942.2  754.35  4986.5  753.44  4994.1  746.39
  4995.1  744.39  5004.9  744.39  5005.9  746.39  5015.4  747.39  5038.2  754.31
  5079.7  753.84  5099.8  753.02  5121.4  753.50  5188.1  753.66  5232.8  753.85
  5246.9  754.37  5259.9  756.19  5274.9  763.48  5300.4  774.00  5316.8  775.82
  5327.3  776.16  5342.2  778.12  5360.3  779.08  5379.6  779.37  5407.2  781.00
#Mann=5,-1,0
  4573.4    0.09       0  4994.1   0.048       0  5005.9    0.09       0
  5188.1    0.12       0  5360.3    0.09       0
Bank Sta=4994.1,5005.9
XS Rating Curve= 0
Exp/Cntr=0.3,0.1

Type RM Length L Ch R = 1,27501,498,498,498
BEGIN DESCRIPTION:
Kerr Creek 55.0
END DESCRIPTION:
XS GIS Cut Line= 3
      1501475.19       679466.63      1502359.87       679421.82
      1502990.66       679390.25
#Sta/Elev= 30
  4112.8  796.99  4250.4  791.14  4311.0  790.30  4396.7  780.81  4467.0  777.41
  4654.8  763.92  4690.1  763.33  4723.6  758.27  4753.9  755.70  4864.0  751.26
  4929.4  751.95  4965.8  752.48  4986.8  750.66  4994.1  744.85  4995.1  742.85
  5004.9  742.85  5005.9  744.85  5007.4  745.67  5026.1  745.94  5049.1  749.22
  5126.5  754.05  5144.7  757.71  5148.8  757.79  5196.4  769.71  5215.7  772.42
  5255.9  775.46  5429.7  781.26  5547.3  786.37  5589.1  790.01  5630.2  790.44
#Mann=5,-1,0
  4112.8    0.09       0  4929.4    0.12       0  4994.1   0.048       0
  5005.9    0.12       0  5429.7    0.09       0
Bank Sta=4994.1,5005.9
XS Rating Curve= 0
Exp/Cntr=0.3,0.1