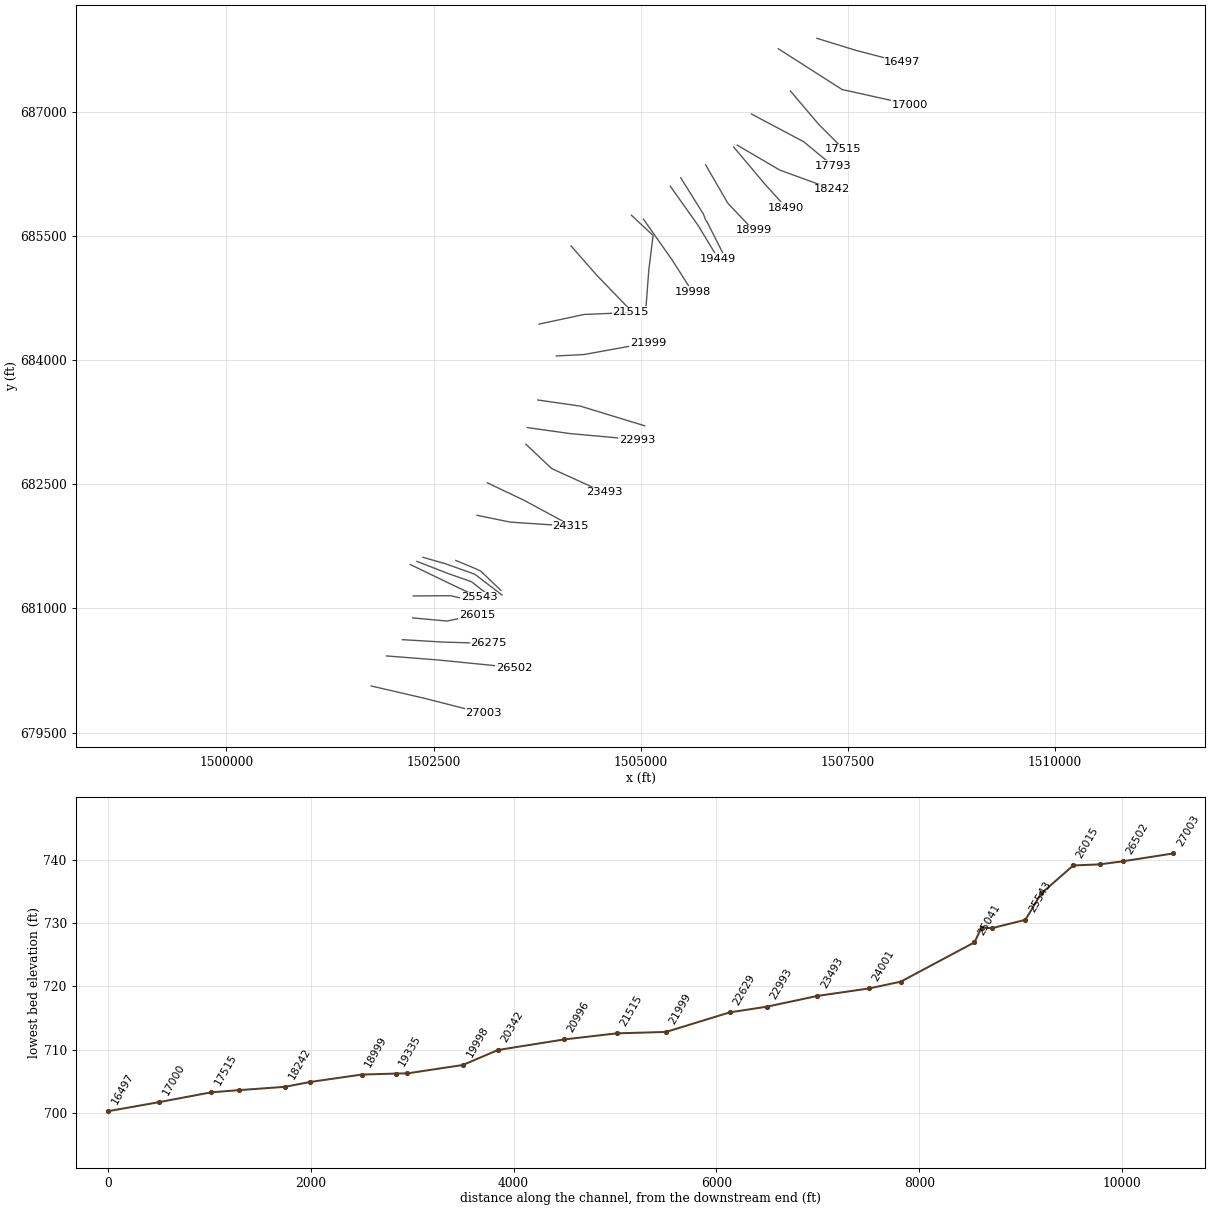
HEC-RAS study Kerr Creek.prj: .Kerr Creek Limited Detail Study

--- Kerr Creek.g01 (geometry) --- (continued)

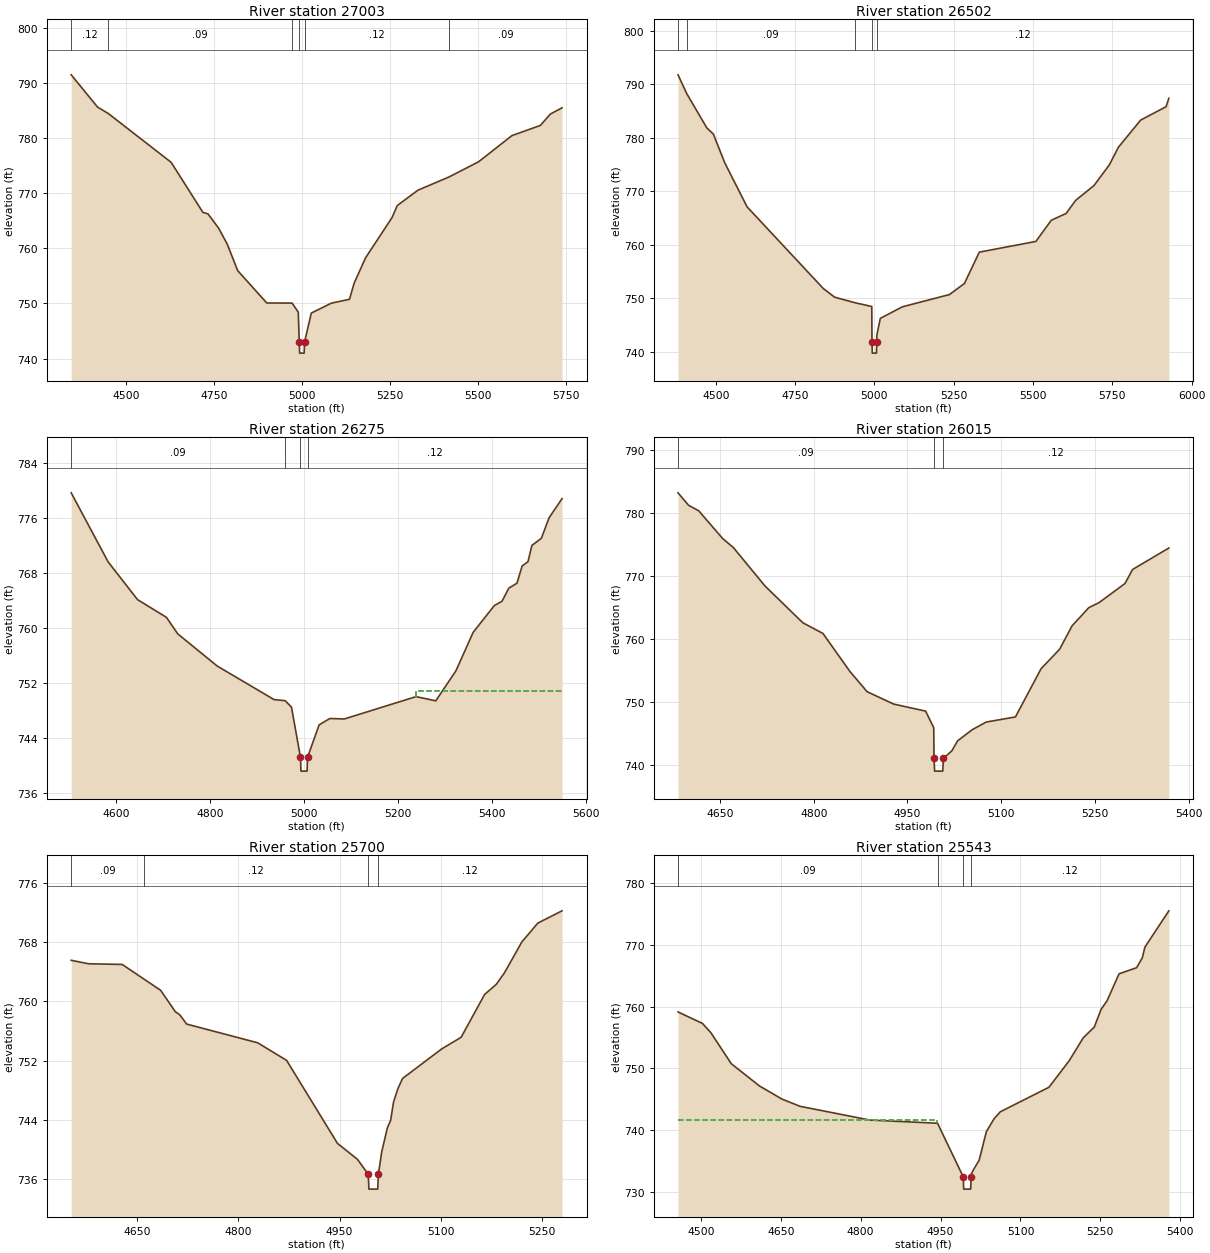
Type RM Length L Ch R = 1,27003,501,501,501
BEGIN DESCRIPTION:
Kerr Creek 54.0
END DESCRIPTION:
XS GIS Cut Line= 3
      1501747.49       680063.33      1502389.02       679914.56
      1503103.39       679732.31
#Sta/Elev= 30
  4343.9  791.43  4418.9  785.58  4449.3  784.42  4628.1  775.57  4718.3  766.51
  4732.9  766.22  4763.1  763.64  4787.7  760.74  4817.3  755.94  4900.1  750.07
  4972.2  750.05  4989.7  748.39  4992.5  742.98  4993.5  740.98  5006.5  740.98
  5007.5  742.98  5026.7  748.24  5083.8  750.04  5135.3  750.74  5148.6  753.67
  5181.0  758.26  5256.4  765.56  5271.2  767.74  5330.1  770.52  5419.6  772.95
  5502.8  775.68  5597.2  780.41  5678.2  782.26  5706.6  784.32  5739.7  785.45
#Mann=6,-1,0
  4343.9    0.12       0  4449.3    0.09       0  4972.2    0.12       0
  4992.5   0.048       0  5007.5    0.12       0  5419.6    0.09       0
Bank Sta=4992.5,5007.5
XS Rating Curve= 0
Exp/Cntr=0.3,0.1

Type RM Length L Ch R = 1,26502,227,227,227
BEGIN DESCRIPTION:
Kerr Creek 53.0
END DESCRIPTION:
XS GIS Cut Line= 3
      1501932.05       680426.17      1502546.47       680378.14
      1503472.52       680286.13
#Sta/Elev= 30
  4381.2  791.76  4408.6  788.25  4472.1  781.82  4492.4  780.70  4528.6  775.29
  4598.8  767.08  4839.0  751.81  4874.7  750.19  4939.1  749.15  4991.8  748.45
  4992.5  741.73  4993.5  739.73  5006.5  739.73  5007.5  741.73  5007.6  743.05
  5018.7  746.23  5088.3  748.39  5236.6  750.68  5283.7  752.74  5330.8  758.61
  5509.0  760.61  5557.5  764.57  5604.3  765.84  5634.4  768.29  5692.0  771.05
  5740.6  774.93  5769.1  778.22  5839.4  783.31  5919.3  785.80  5928.1  787.38
#Mann=5,-1,0
  4381.2    0.12       0  4408.6    0.09       0  4939.1    0.12       0
  4992.5   0.048       0  5007.5    0.12       0
Bank Sta=4992.5,5007.5
XS Rating Curve= 0
Exp/Cntr=0.3,0.1

Type RM Length L Ch R = 1,26275,260,260,260
BEGIN DESCRIPTION:
Kerr Creek 52.0
END DESCRIPTION:
XS GIS Cut Line= 3
      1502123.07       680622.73      1502614.73       680593.62
      1503167.87       680577.44
#Sta/Elev= 30
  4503.9  779.71  4582.6  769.67  4645.3  764.18  4706.8  761.61  4731.0  759.20
  4815.0  754.53  4936.2  749.65  4959.8  749.49  4973.3  748.56  4992.5  741.25
  4993.5  739.25  5006.5  739.25  5007.5  741.25  5032.2  745.98  5055.0  746.90
  5085.7  746.83  5238.7  750.08  5280.8  749.47  5323.7  753.83  5360.5  759.43
  5405.7  763.33  5421.9  763.94  5436.5  765.86  5453.8  766.57  5464.8  769.07
  5477.3  769.70  5485.6  772.06  5505.8  773.10  5522.3  776.09  5549.8  778.86
#Mann=4,-1,0
  4503.9    0.09       0  4959.8    0.12       0  4992.5   0.048       0
  5007.5    0.12       0
#XS Ineff=2,0
       0                 5238.70    0.00  750.83
Permanent Ineff=
       F       F
Bank Sta=4992.5,5007.5
XS Rating Curve= 0
Exp/Cntr=0.3,0.1

Type RM Length L Ch R = 1,26015,315,315,315
BEGIN DESCRIPTION:
Kerr Creek 51.0
END DESCRIPTION:
XS GIS Cut Line= 3
      1502249.09       680885.46      1502663.09       680847.56
      1503024.97       680924.99
#Sta/Elev= 30
  4582.7  783.15  4599.5  781.18  4615.9  780.30  4653.9  775.94  4671.3  774.48
  4722.1  768.38  4782.4  762.58  4814.7  760.88  4857.9  754.86  4885.4  751.66
  4927.8  749.70  4979.1  748.58  4992.1  745.95  4992.5  741.08  4993.5  739.08
  5006.5  739.08  5007.5  741.08  5021.2  742.31  5030.2  743.87  5053.7  745.64
  5076.0  746.85  5122.9  747.66  5163.9  755.29  5193.7  758.39  5213.5  762.08
  5240.3  764.96  5256.7  765.76  5298.3  768.79  5310.4  771.01  5368.5  774.41
#Mann=3,-1,0
  4582.7    0.09       0  4992.5   0.048       0  5007.5    0.12       0
Bank Sta=4992.5,5007.5
XS Rating Curve= 0
Exp/Cntr=0.3,0.1

Type RM Length L Ch R = 1,25700,157,157,157
BEGIN DESCRIPTION:
Kerr Creek 50.0
END DESCRIPTION:
XS GIS Cut Line= 3
      1502254.89       681150.79      1502703.91       681153.70
      1502975.05       681092.48
#Sta/Elev= 30
  4552.5  765.53  4578.1  765.06  4628.1  764.97  4660.8  762.96  4684.9  761.49
  4706.8  758.59  4713.2  758.19  4723.5  756.93  4828.8  754.40  4871.6  752.03
  4946.9  740.84  4976.5  738.69  4992.5  736.67  4993.5  734.67  5006.5  734.67
  5007.5  736.67  5012.4  739.67  5020.8  742.93  5025.6  743.93  5030.0  746.43
  5036.5  748.24  5043.4  749.60  5101.5  753.59  5130.1  755.15  5164.9  760.93
  5182.0  762.27  5194.3  763.85  5220.0  768.00  5243.6  770.54  5279.5  772.20
#Mann=4,-1,0
  4552.5    0.09       0  4660.8    0.12       0  4992.5   0.048       0
  5007.5    0.12       0
Bank Sta=4992.5,5007.5
XS Rating Curve= 0
Exp/Cntr=0.3,0.1

Type RM Length L Ch R = 1,25543,328,328,328
BEGIN DESCRIPTION:
Kerr Creek 49.0
END DESCRIPTION:
XS GIS Cut Line= 3
      1502217.57       681531.26      1502707.07       681294.58
      1503048.65       681133.21
#Sta/Elev= 30
  4457.1  759.12  4502.9  757.27  4518.7  755.78  4557.0  750.77  4609.6  747.19
  4652.2  745.05  4686.3  743.88  4817.5  741.66  4944.3  741.15  4992.5  732.51
  4993.5  730.51  5006.5  730.51  5007.5  732.51  5007.6  732.91  5011.4  733.59
  5022.4  735.17  5036.0  739.79  5050.2  741.84  5062.0  742.99  5153.5  746.96
  5191.8  751.28  5217.8  754.94  5238.6  756.68  5251.5  759.56  5262.5  760.91
  5285.1  765.28  5317.9  766.26  5328.7  767.85  5333.6  769.58  5378.6  775.45
#Mann=4,-1,0
  4457.1    0.09       0  4944.3    0.12       0  4992.5   0.048       0
  5007.5    0.12       0
#XS Ineff=2,0
    0.00 4942.60  741.68               0
Permanent Ineff=
       F       F
Bank Sta=4992.5,5007.5
XS Rating Curve= 0
Exp/Cntr=0.5,0.3

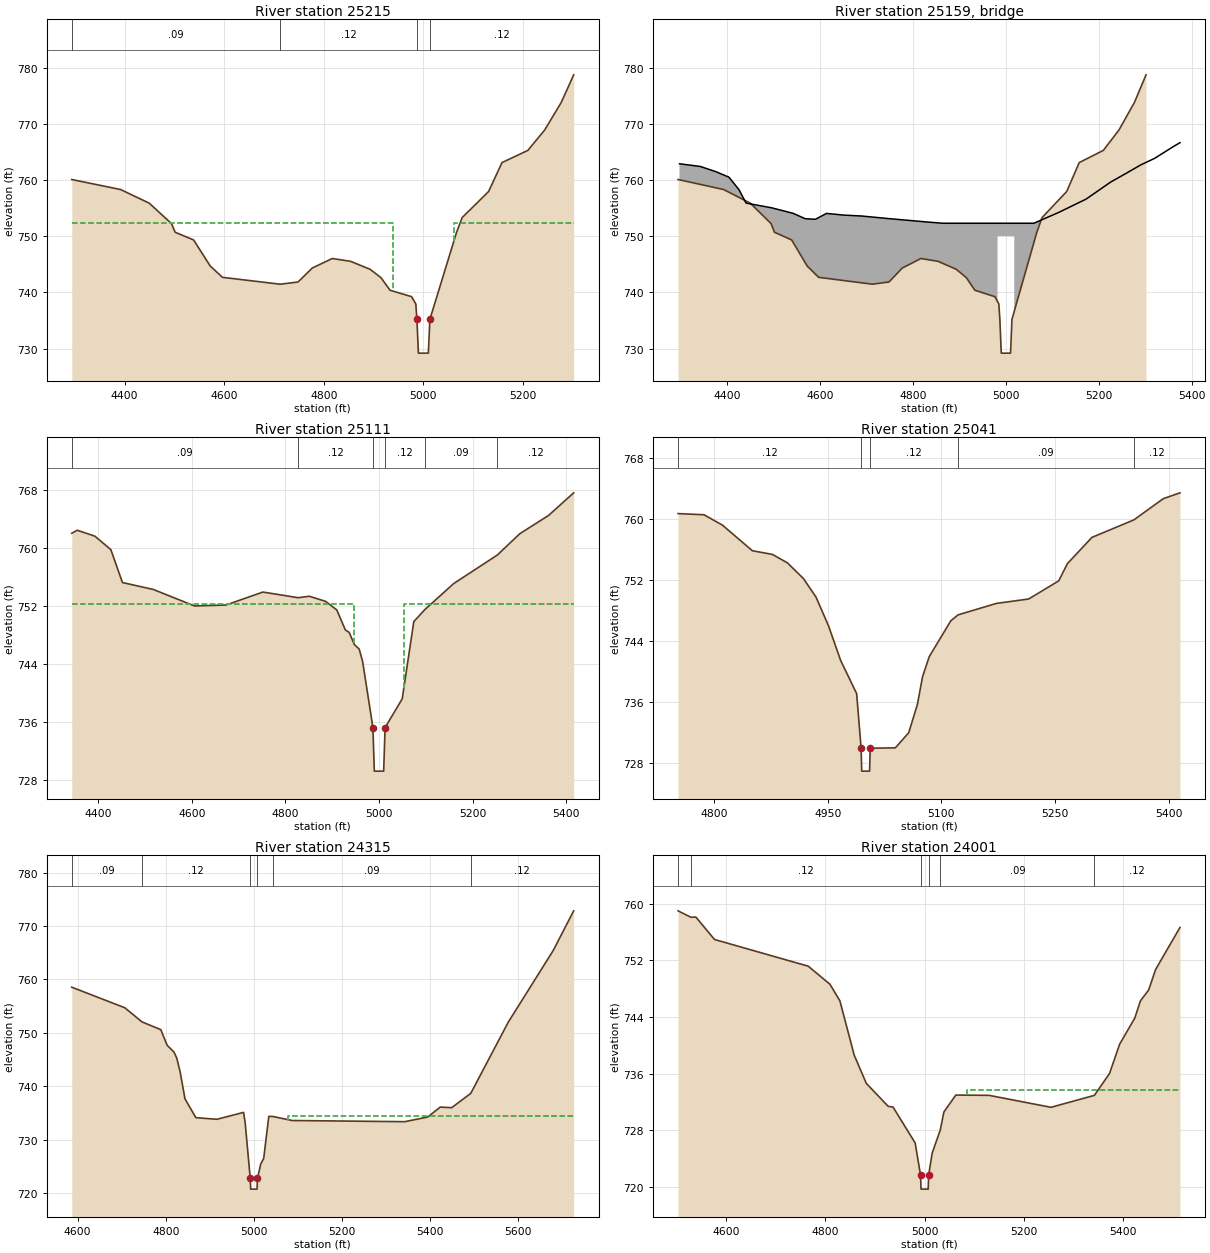
Type RM Length L Ch R = 1,25215,104,104,104
BEGIN DESCRIPTION:
Bradshaw Road (Kerr) us
END DESCRIPTION:
XS GIS Cut Line= 4
      1502299.95       681568.02      1502668.14       681424.49
      1502957.57       681322.81      1503198.57       681134.31
#Sta/Elev= 30
  4293.9  760.08  4391.9  758.30  4449.5  755.87  4494.2  752.24  4501.5  750.70
  4538.6  749.33  4572.0  744.69  4596.6  742.68  4712.4  741.46  4748.3  741.85
  4776.8  744.33  4817.1  746.03  4853.8  745.53  4893.0  744.11  4914.9  742.62
  4933.0  740.39  4976.3  739.24  4984.8  737.94  4987.0  735.20  4990.0  729.20
  5010.0  729.20  5013.0  735.20  5066.5  750.65  5077.9  753.31  5131.0  757.95
  5157.9  763.09  5209.8  765.26  5243.5  768.88  5276.8  773.78  5301.8  778.70
#Mann=4,-1,0
  4293.9    0.09       0  4712.4    0.12       0  4987.0   0.048       0
  5013.0    0.12       0
#XS Ineff=2,0
    0.00 4939.00  752.30 5061.00    0.00  752.34
Permanent Ineff=
       F       F
Bank Sta=4987,5013
XS Rating Curve= 0
Exp/Cntr=0.5,0.3

Type RM Length L Ch R =3,25159,,,
BEGIN DESCRIPTION:
Bradshaw Road TOR (Kerr)
Structure ID: LDS_KC_06
Approximate Survey Structure
END DESCRIPTION:
Bridge Culvert--1,0,-1,-1,0
Deck Dist Width WeirC Skew NumUp NumDn MinLoCord MaxHiCord MaxSubmerge Is_Ogee
43,26,3,,29,29,,,,0,1,1,,,
  4297.0  4341.9  4374.8  4403.6  4425.4  4440.3  4495.9  4541.6  4567.7  4589.5
  4613.7  4651.0  4689.0  4748.4  4832.2  4864.2  4982.0  4982.0  5018.0  5018.0
  5060.2  5113.8  5172.8  5225.9  5257.0  5291.2  5320.5  5358.9  5374.9
  762.88  762.40  761.49  760.49  758.24  755.89  755.04  754.07  753.11  753.00
  754.05  753.75  753.59  753.12  752.51  752.30  752.30  752.30  752.30  752.30
  752.30  754.23  756.60  759.64  761.09  762.71  763.85  765.85  766.63
  709.54  709.54  709.54  709.54  709.54  709.54  709.54  709.54  709.54  709.54
  709.54  709.54  709.54  709.54  709.54  709.54  709.54  750.00  750.00  709.54
  709.54  709.54  709.54  709.54  709.54  709.54  709.54  709.54  709.54
  4297.0  4341.9  4374.8  4403.6  4425.4  4440.3  4495.9  4541.6  4567.7  4589.5
  4613.7  4651.0  4689.0  4748.4  4832.2  4864.2  4982.0  4982.0  5018.0  5018.0
  5060.2  5113.8  5172.8  5225.9  5257.0  5291.2  5320.5  5358.9  5374.9
  762.88  762.40  761.49  760.49  758.24  755.89  755.04  754.07  753.11  753.00
  754.05  753.75  753.59  753.12  752.51  752.30  752.30  752.30  752.30  752.30
  752.30  754.23  756.60  759.64  761.09  762.71  763.85  765.85  766.63
  709.54  709.54  709.54  709.54  709.54  709.54  709.54  709.54  709.54  709.54
  709.54  709.54  709.54  709.54  709.54  709.54  709.54  750.00  750.00  709.54
  709.54  709.54  709.54  709.54  709.54  709.54  709.54  709.54  709.54
BR Coef=1,1,0,1.25,0,,,0.8,0,2,0,
WSPro=,,,, 1 ,,,, 0 ,,,, 0 ,,,,-1 ,-1 ,-1 , 0 , 0 , 0 , 0 , 0
BC Design=,,0,,0,,,,,,

Type RM Length L Ch R = 1,25111,70,70,70
BEGIN DESCRIPTION:
Bradshaw Road (Kerr) ds
END DESCRIPTION:
XS GIS Cut Line= 4
      1502371.92       681617.60      1502644.18       681539.56
      1502998.39       681413.19      1503326.52       681162.07
#Sta/Elev= 30
  4343.5  762.08  4355.3  762.50  4392.8  761.69  4427.0  759.83  4451.8  755.29
  4517.6  754.34  4605.9  752.06  4672.9  752.19  4751.9  753.98  4827.2  753.20
  4851.1  753.40  4885.7  752.70  4909.9  751.51  4928.0  748.77  4936.3  748.41
  4947.2  746.76  4957.7  746.12  4965.1  744.38  4987.0  735.29  4990.0  729.29
  5010.0  729.29  5013.0  735.29  5049.6  739.25  5074.4  749.91  5098.0  751.56
  5159.6  755.15  5252.8  759.08  5301.0  762.03  5362.3  764.54  5416.0  767.66
#Mann=6,-1,0
  4343.5    0.09       0  4827.2    0.12       0  4987.0   0.048       0
  5013.0    0.12       0  5098.0    0.09       0  5252.8    0.12       0
#XS Ineff=2,0
    0.00 4947.00  752.30 5053.00    0.00  752.30
Permanent Ineff=
       F       F
Bank Sta=4987,5013
XS Rating Curve= 0
Exp/Cntr=0.5,0.3

Type RM Length L Ch R = 1,25041,726,726,726
BEGIN DESCRIPTION:
Kerr Creek 48.0
END DESCRIPTION:
XS GIS Cut Line= 4
      1502768.89       681579.71      1502994.87       681485.56
      1503070.18       681450.59      1503312.28       681219.25
#Sta/Elev= 30
  4752.3  760.68  4786.5  760.53  4810.8  759.18  4850.4  755.82  4877.1  755.33
  4896.8  754.22  4917.8  752.18  4934.5  749.74  4950.9  746.00  4967.0  741.45
  4988.1  737.11  4994.0  729.96  4994.8  726.96  5005.2  726.96  5006.0  729.96
  5039.2  730.01  5056.9  731.99  5068.4  735.73  5075.0  739.27  5083.9  741.94
  5112.4  746.64  5122.0  747.42  5172.6  748.92  5215.3  749.50  5254.9  751.87
  5266.4  754.13  5298.7  757.56  5354.2  759.86  5392.9  762.63  5415.0  763.40
#Mann=5,-1,0
  4752.3    0.12       0  4994.0   0.048       0  5006.0    0.12       0
  5122.0    0.09       0  5354.2    0.12       0
Bank Sta=4994,5006
XS Rating Curve= 0
Exp/Cntr=0.3,0.1

Type RM Length L Ch R = 1,24315,314,314,314
BEGIN DESCRIPTION:
Kerr Creek 47.0
END DESCRIPTION:
XS GIS Cut Line= 3
      1503025.01       682125.00      1503426.05       682042.54
      1504153.90       681994.01
#Sta/Elev= 30
  4586.8  758.55  4707.2  754.70  4746.1  752.06  4788.9  750.60  4803.3  747.67
  4818.6  746.42  4825.0  745.30  4832.7  742.72  4843.7  737.66  4868.4  734.13
  4916.3  733.83  4976.6  735.12  4980.3  733.18  4991.8  722.76  4992.8  720.76
  5007.2  720.76  5008.2  722.76  5015.7  725.47  5022.3  726.49  5033.9  734.37
  5043.3  734.35  5086.7  733.60  5342.3  733.38  5394.4  734.25  5423.0  736.11
  5448.9  736.00  5492.2  738.68  5577.1  751.98  5679.6  765.46  5725.7  772.84
#Mann=6,-1,0
  4586.8    0.09       0  4746.1    0.12       0  4991.8   0.048       0
  5008.2    0.12       0  5043.3    0.09       0  5492.2    0.12       0
#XS Ineff=2,0
       0                 5077.50    0.00  734.50
Permanent Ineff=
       F       F
Bank Sta=4991.8,5008.2
XS Rating Curve= 0
Exp/Cntr=0.3,0.1

Type RM Length L Ch R = 1,24001,508,508,508
BEGIN DESCRIPTION:
Kerr Creek 46.0
END DESCRIPTION:
XS GIS Cut Line= 3
      1503150.56       682516.84      1503600.18       682302.46
      1504052.29       682058.18
#Sta/Elev= 30
  4502.9  759.01  4528.9  758.10  4538.8  758.13  4576.4  754.96  4765.3  751.19
  4809.1  748.64  4829.2  746.30  4858.0  738.63  4882.4  734.64  4926.5  731.39
  4936.3  731.29  4981.0  726.21  4991.8  721.69  4992.8  719.69  5007.2  719.69
  5008.2  721.69  5015.2  724.76  5031.6  728.04  5038.9  730.59  5062.9  732.98
  5129.9  732.94  5254.9  731.25  5342.4  732.94  5372.9  736.03  5393.2  740.16
  5423.8  743.86  5435.2  746.29  5451.8  747.83  5465.7  750.71  5514.9  756.66
#Mann=6,-1,0
  4502.9    0.09       0  4528.9    0.12       0  4991.8   0.048       0
  5008.2    0.12       0  5031.6    0.09       0  5342.4    0.12       0
#XS Ineff=2,0
       0                 5085.00    0.00  733.67
Permanent Ineff=
       F       F
Bank Sta=4991.8,5008.2
XS Rating Curve= 0
Exp/Cntr=0.3,0.1

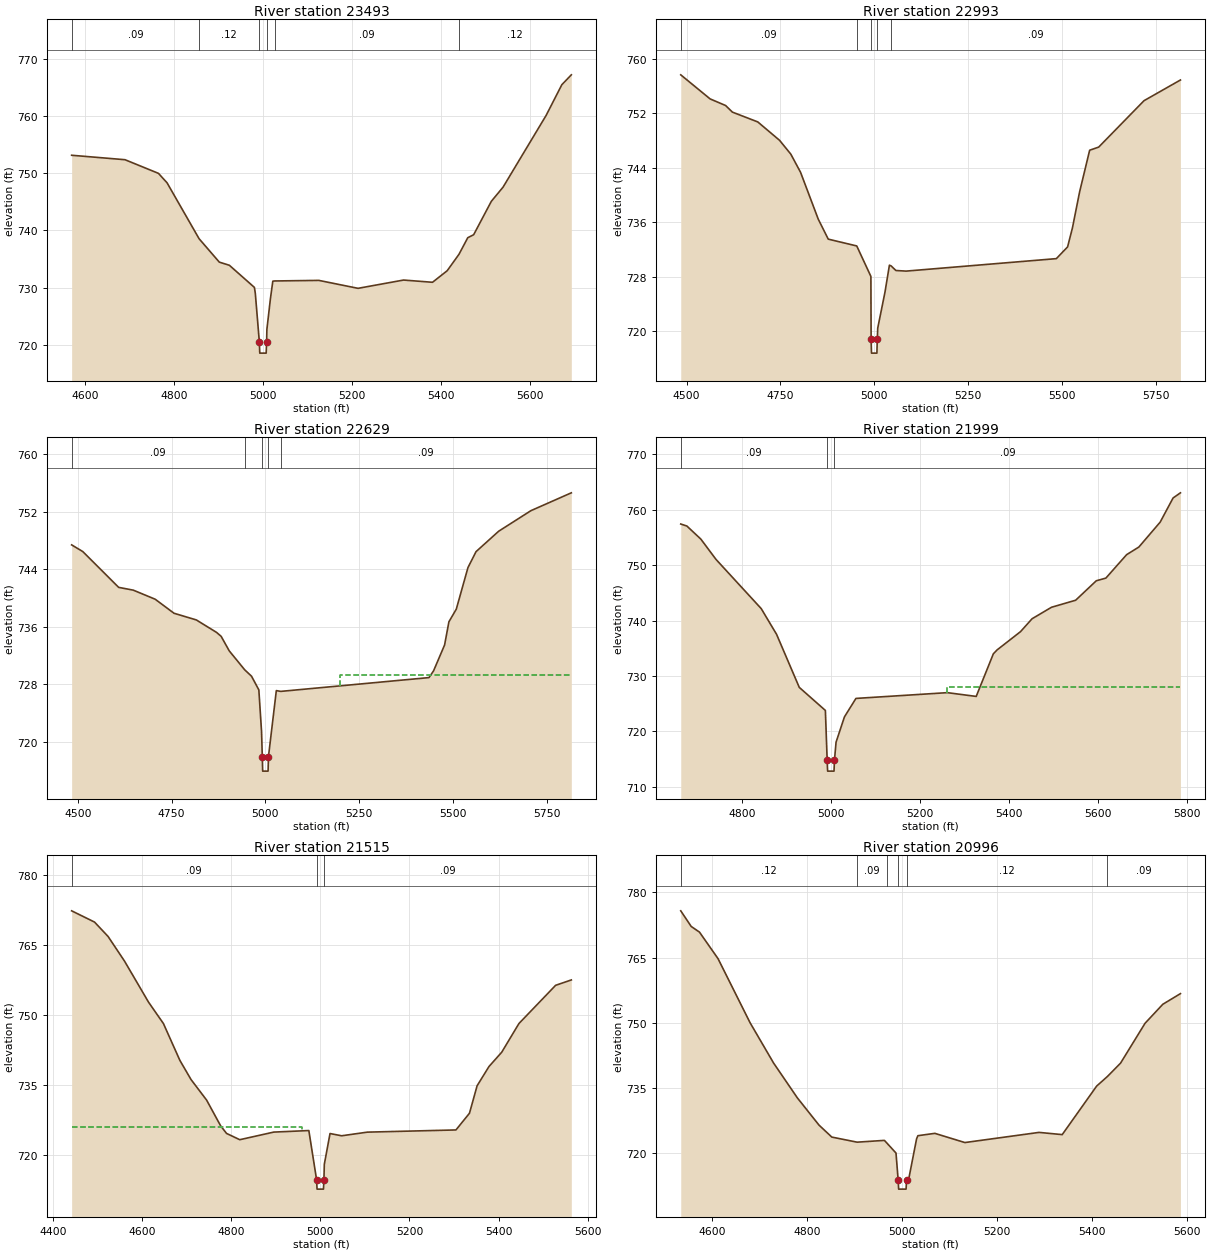
Type RM Length L Ch R = 1,23493,500,500,500
BEGIN DESCRIPTION:
Kerr Creek 45.0
END DESCRIPTION:
XS GIS Cut Line= 3
      1503614.76       682983.54      1503926.73       682689.07
      1504557.75       682401.40
#Sta/Elev= 30
  4570.2  753.17  4690.1  752.39  4765.2  750.00  4784.5  748.35  4856.4  738.56
  4901.9  734.45  4924.5  733.90  4980.8  730.02  4982.8  728.98  4991.8  720.51
  4992.8  718.51  5007.2  718.51  5008.2  720.51  5008.8  722.67  5016.8  728.08
  5022.1  731.11  5026.0  731.15  5125.5  731.25  5213.6  729.86  5315.8  731.31
  5380.9  730.92  5413.8  732.94  5440.4  735.83  5460.1  738.73  5473.3  739.25
  5513.0  745.10  5539.3  747.58  5636.1  760.15  5671.4  765.53  5692.7  767.26
#Mann=6,-1,0
  4570.2    0.09       0  4856.4    0.12       0  4991.8   0.048       0
  5008.2    0.12       0  5026.0    0.09       0  5440.4    0.12       0
Bank Sta=4991.8,5008.2
XS Rating Curve= 0
Exp/Cntr=0.3,0.1

Type RM Length L Ch R = 1,22993,364,364,364
BEGIN DESCRIPTION:
Kerr Creek 44.0
END DESCRIPTION:
XS GIS Cut Line= 3
      1503632.20       683184.73      1504148.31       683111.84
      1504955.90       683038.95
#Sta/Elev= 30
  4484.3  757.63  4562.5  754.10  4603.8  753.13  4622.0  752.16  4689.7  750.72
  4747.8  748.02  4777.8  745.99  4803.7  743.33  4850.8  736.47  4877.5  733.53
  4953.5  732.53  4991.2  728.06  4991.8  718.81  4992.8  716.81  5007.2  716.81
  5008.2  718.81  5009.5  720.50  5028.7  725.74  5040.6  729.71  5045.2  729.60
  5057.8  728.93  5084.9  728.84  5485.6  730.67  5515.6  732.39  5528.6  735.20
  5547.5  740.43  5574.4  746.57  5598.5  747.03  5719.4  753.84  5816.4  756.87
#Mann=5,-1,0
  4484.3    0.09       0  4953.5    0.12       0  4991.8   0.048       0
  5008.2    0.12       0  5045.2    0.09       0
Bank Sta=4991.8,5008.2
XS Rating Curve= 0
Exp/Cntr=0.3,0.1

Type RM Length L Ch R = 1,22629,630,630,630
BEGIN DESCRIPTION:
Kerr Creek 43.0
END DESCRIPTION:
XS GIS Cut Line= 3
      1503758.30       683517.82      1504270.77       683444.22
      1505050.08       683205.79
#Sta/Elev= 30
  4483.3  747.39  4513.0  746.46  4608.7  741.48  4647.9  741.09  4706.1  739.83
  4756.3  737.88  4815.8  736.95  4869.7  735.22  4882.0  734.67  4903.6  732.65
  4944.9  730.01  4963.1  729.12  4982.6  727.22  4989.8  721.41  4991.8  717.92
  4992.8  715.92  5007.2  715.92  5008.2  717.92  5029.2  727.12  5040.8  727.01
  5436.4  728.93  5448.6  729.87  5478.0  733.47  5489.5  736.69  5509.2  738.45
  5540.3  744.23  5561.9  746.45  5622.3  749.29  5708.3  752.15  5816.0  754.63
#Mann=5,-1,0
  4483.3    0.09       0  4944.9    0.12       0  4991.8   0.048       0
  5008.2    0.12       0  5040.8    0.09       0
#XS Ineff=2,0
       0                 5200.00    0.00  729.32
Permanent Ineff=
       F       F
Bank Sta=4991.8,5008.2
XS Rating Curve= 0
Exp/Cntr=0.3,0.1

Type RM Length L Ch R = 1,21999,484,484,484
BEGIN DESCRIPTION:
Kerr Creek 42.0
END DESCRIPTION:
XS GIS Cut Line= 3
      1503982.09       684049.50      1504317.42       684067.00
      1505090.68       684208.00
#Sta/Elev= 30
  4663.1  757.42  4676.8  757.06  4708.2  754.70  4742.3  751.03  4843.7  742.16
  4878.2  737.52  4929.2  727.94  4987.8  723.78  4991.8  714.83  4992.8  712.83
  5007.2  712.83  5008.2  714.83  5011.8  718.06  5030.6  722.62  5056.4  725.95
  5261.7  726.99  5326.4  726.31  5364.9  734.00  5373.4  734.71  5425.9  738.00
  5451.9  740.33  5495.5  742.40  5549.7  743.67  5596.0  747.18  5617.5  747.66
  5664.1  751.89  5691.6  753.27  5739.4  757.76  5768.4  762.12  5784.9  763.05
#Mann=3,-1,0
  4663.1    0.09       0  4991.8   0.048       0  5008.2    0.09       0
#XS Ineff=2,0
       0                 5261.00    0.00  727.97
Permanent Ineff=
       F       F
Bank Sta=4991.8,5008.2
XS Rating Curve= 0
Exp/Cntr=0.3,0.1

Type RM Length L Ch R = 1,21515,519,519,519
BEGIN DESCRIPTION:
Kerr Creek 41.0
END DESCRIPTION:
XS GIS Cut Line= 3
      1503773.97       684434.53      1504317.42       684550.99
      1504881.62       684574.93
#Sta/Elev= 30
  4442.5  772.24  4493.8  769.83  4524.1  766.76  4560.9  761.49  4615.0  752.66
  4648.3  748.09  4685.2  740.20  4710.2  736.09  4745.2  731.68  4776.5  726.19
  4789.8  724.55  4819.5  723.20  4895.7  724.83  4974.4  725.16  4991.8  714.61
  4992.8  712.61  5007.2  712.61  5008.2  714.61  5009.1  717.93  5021.9  724.52
  5048.1  724.04  5105.6  724.82  5304.3  725.29  5334.6  728.87  5351.7  734.75
  5378.3  738.87  5406.9  741.94  5445.6  748.10  5527.8  756.28  5563.0  757.43
#Mann=3,-1,0
  4442.5    0.09       0  4991.8   0.048       0  5008.2    0.09       0
#XS Ineff=2,0
    0.00 4960.00  725.99               0
Permanent Ineff=
       F       F
Bank Sta=4991.8,5008.2
XS Rating Curve= 0
Exp/Cntr=0.3,0.1

Type RM Length L Ch R = 1,20996,654,654,654
BEGIN DESCRIPTION:
Kerr Creek 40.0
END DESCRIPTION:
XS GIS Cut Line= 3
      1504159.99       685379.01      1504469.03       685026.24
      1504874.28       684606.41
#Sta/Elev= 30
  4533.2  775.77  4555.2  772.17  4572.6  770.87  4611.7  764.76  4679.2  749.99
  4728.8  740.69  4778.8  732.68  4824.4  726.40  4851.4  723.64  4904.6  722.47
  4962.2  722.88  4967.4  722.26  4986.6  719.96  4991.2  713.65  4992.2  711.65
  5007.8  711.65  5008.8  713.65  5013.8  714.21  5029.9  723.22  5032.7  723.96
  5068.4  724.50  5131.7  722.38  5287.9  724.72  5336.7  724.21  5409.3  735.40
  5432.0  737.61  5459.6  740.68  5511.1  749.85  5548.6  754.24  5585.7  756.69
#Mann=6,-1,0
  4533.2    0.12       0  4904.6    0.09       0  4967.4    0.12       0
  4991.2   0.048       0  5008.8    0.12       0  5432.0    0.09       0
Bank Sta=4991.2,5008.8
XS Rating Curve= 0
Exp/Cntr=0.3,0.1

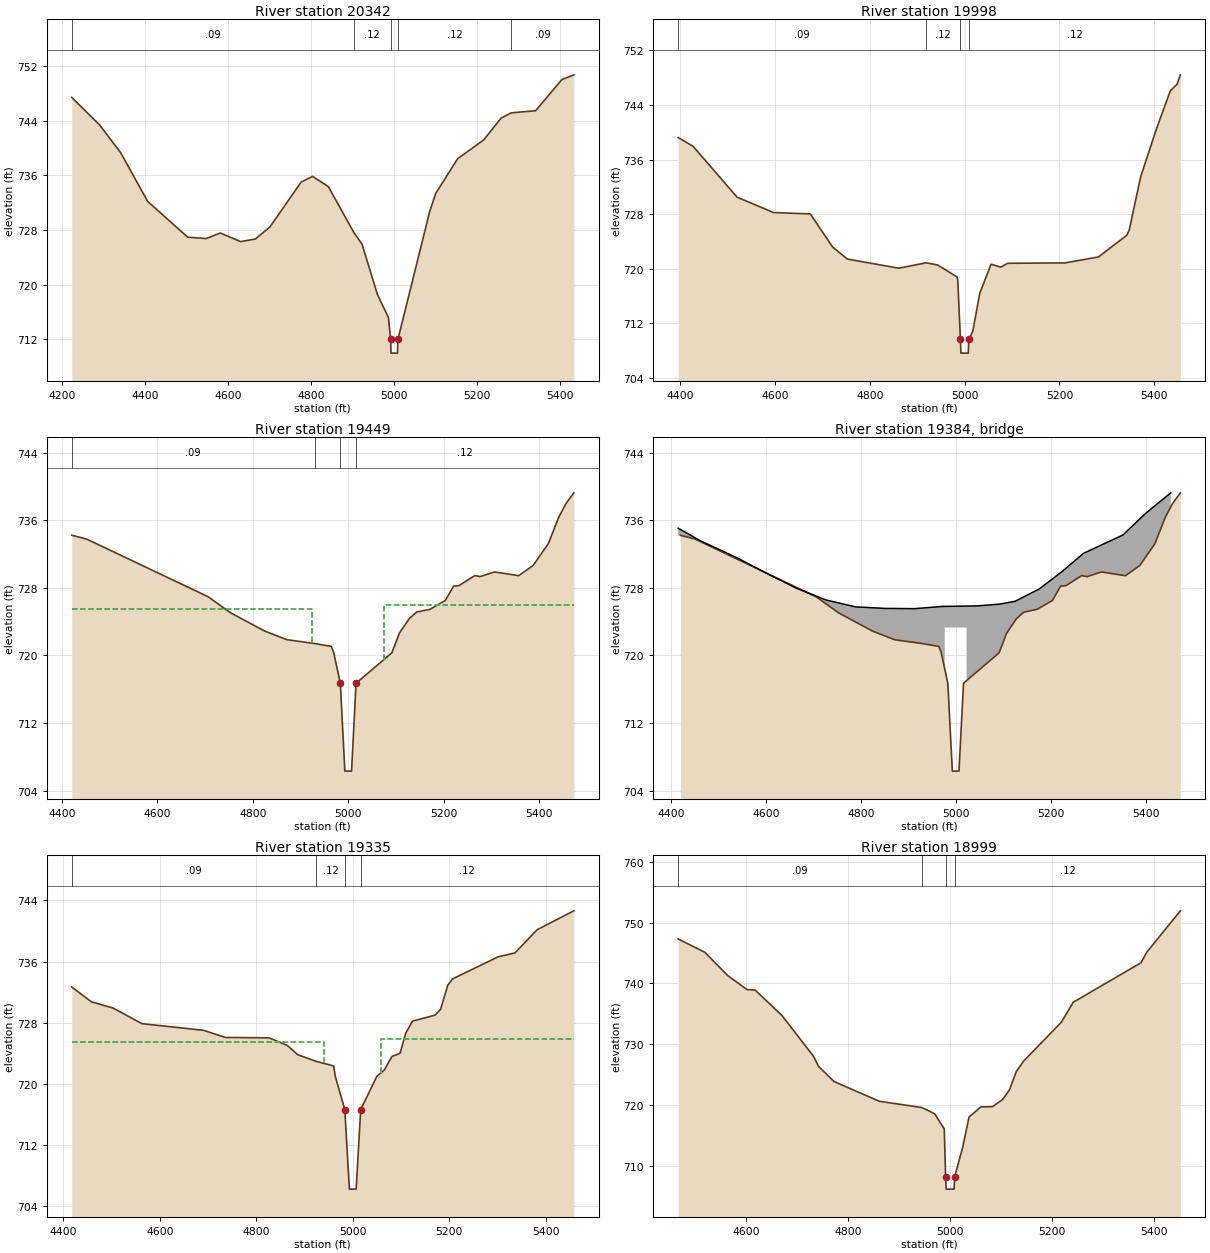
Type RM Length L Ch R = 1,20342,344,344,344
BEGIN DESCRIPTION:
Kerr Creek 39.0
END DESCRIPTION:
XS GIS Cut Line= 4
      1504888.88       685749.32      1505150.26       685505.19
      1505098.50       685087.89      1505066.16       684657.66
#Sta/Elev= 30
  4223.1  747.42  4290.8  743.35  4341.1  739.31  4406.0  732.19  4502.5  726.96
  4546.9  726.75  4580.8  727.57  4630.0  726.31  4665.4  726.69  4700.6  728.46
  4775.6  735.02  4803.1  735.86  4841.2  734.37  4903.4  727.57  4922.4  725.93
  4959.6  718.55  4986.1  715.18  4991.2  711.98  4992.2  709.98  5007.8  709.98
  5008.8  711.98  5085.3  730.69  5100.0  733.37  5152.8  738.45  5215.4  741.19
  5257.6  744.40  5281.8  745.16  5340.7  745.48  5403.9  750.04  5432.7  750.73
#Mann=5,-1,0
  4223.1    0.09       0  4903.4    0.12       0  4991.2   0.048       0
  5008.8    0.12       0  5281.8    0.09       0
Bank Sta=4991.2,5008.8
XS Rating Curve= 0
Exp/Cntr=0.3,0.1

Type RM Length L Ch R = 1,19998,549,549,549
BEGIN DESCRIPTION:
Kerr Creek 38.0
END DESCRIPTION:
XS GIS Cut Line= 3
      1505033.23       685702.88      1505381.62       685207.01
      1505625.01       684824.98
#Sta/Elev= 30
  4396.0  739.22  4427.2  737.95  4520.2  730.48  4596.8  728.23  4674.6  728.03
  4721.8  723.16  4752.8  721.41  4861.1  720.07  4918.7  720.86  4943.3  720.54
  4984.4  718.77  4985.6  718.30  4991.2  709.62  4992.2  707.62  5007.8  707.62
  5008.8  709.62  5017.3  710.82  5031.9  716.36  5055.8  720.65  5076.4  720.23
  5090.9  720.79  5211.9  720.85  5282.5  721.72  5342.1  724.90  5347.2  725.64
  5371.5  733.51  5404.8  740.52  5433.8  746.06  5448.1  747.04  5455.0  748.42
#Mann=4,-1,0
  4396.0    0.09       0  4918.7    0.12       0  4991.2   0.048       0
  5008.8    0.12       0
Bank Sta=4991.2,5008.8
XS Rating Curve= 0
Exp/Cntr=0.5,0.3

Type RM Length L Ch R = 1,19449,114,114,114
BEGIN DESCRIPTION:
Caldwell Road (Kerr) us
END DESCRIPTION:
XS GIS Cut Line= 3
      1505357.86       686100.09      1505693.60       685626.86
      1505938.10       685222.34
#Sta/Elev= 30
  4420.3  734.21  4451.4  733.76  4706.1  726.94  4753.1  725.04  4825.0  722.87
  4871.6  721.85  4929.4  721.40  4964.5  721.06  4969.4  720.37  4983.5  716.70
  4993.0  706.30  5007.0  706.30  5016.5  716.70  5091.5  720.30  5107.4  722.63
  5128.4  724.37  5143.6  725.12  5171.6  725.45  5203.7  726.49  5221.1  728.20
  5232.3  728.25  5265.6  729.44  5276.8  729.32  5307.0  729.87  5357.7  729.43
  5387.9  730.64  5419.9  733.23  5440.8  736.25  5456.4  737.93  5473.2  739.23
#Mann=4,-1,0
  4420.3    0.09       0  4929.4    0.12       0  4983.5   0.048       0
  5016.5    0.12       0
#XS Ineff=2,0
    0.00 4925.00  725.54 5075.00    0.00  725.93
Permanent Ineff=
       F       F
Bank Sta=4983.5,5016.5
XS Rating Curve= 0
Exp/Cntr=0.5,0.3

Type RM Length L Ch R =3,19384,,,
BEGIN DESCRIPTION:
Caldwell Road TOR (Kerr)
Structure ID: LDS_KC_05
Approximate Survey Structure
END DESCRIPTION:
Bridge Culvert--1,0,-1,-1,0
Deck Dist Width WeirC Skew NumUp NumDn MinLoCord MaxHiCord MaxSubmerge Is_Ogee
52,26,3,,23,23,,,,0,1,1,,,
  4415.6  4461.7  4539.9  4602.4  4664.8  4727.2  4789.4  4851.5  4913.2  4971.0
  4977.0  4977.0  5023.0  5023.0  5045.8  5091.3  5125.1  5175.8  5222.7  5269.3
  5352.3  5400.1  5453.1
  735.05  733.58  731.54  729.69  727.94  726.55  725.74  725.56  725.53  725.79
  725.80  725.80  725.84  725.84  725.86  726.06  726.40  727.85  729.86  732.08
  734.25  736.81  739.24
  686.52  686.52  686.52  686.52  686.52  686.52  686.52  686.52  686.52  686.52
  686.52  723.30  723.30  686.52  686.52  686.52  686.52  686.52  686.52  686.52
  686.52  686.52  686.52
  4415.6  4461.7  4539.9  4602.4  4664.8  4727.2  4789.4  4851.5  4913.2  4971.0
  4977.0  4977.0  5023.0  5023.0  5045.8  5091.3  5125.1  5175.8  5222.7  5269.3
  5352.3  5400.1  5453.1
  735.05  733.58  731.54  729.69  727.94  726.55  725.74  725.56  725.53  725.79
  725.80  725.80  725.84  725.84  725.86  726.06  726.40  727.85  729.86  732.08
  734.25  736.81  739.24
  686.52  686.52  686.52  686.52  686.52  686.52  686.52  686.52  686.52  686.52
  686.52  723.30  723.30  686.52  686.52  686.52  686.52  686.52  686.52  686.52
  686.52  686.52  686.52
BR Coef=1,1,0,1.25,0,,,0.8,0,2,0,
WSPro=,,,, 1 ,,,, 0 ,,,, 0 ,,,,-1 ,-1 ,-1 , 0 , 0 , 0 , 0 , 0
BC Design=,,0,,0,,,,,,

Type RM Length L Ch R = 1,19335,336,336,336
BEGIN DESCRIPTION:
Caldwell Road (Kerr) ds
END DESCRIPTION:
XS GIS Cut Line= 5
      1505484.27       686201.33      1505758.36       685762.78
      1505781.07       685699.75      1505808.29       685656.69
      1505991.00       685294.46
#Sta/Elev= 30
  4417.5  732.69  4458.1  730.75  4503.2  729.93  4563.1  727.89  4690.4  727.03
  4735.9  726.09  4826.4  726.04  4864.5  725.04  4885.8  723.84  4924.7  722.96
  4960.4  722.37  4963.9  720.98  4983.5  716.67  4993.0  706.27  5007.0  706.27
  5016.5  716.67  5049.9  721.00  5065.6  721.86  5081.3  723.61  5098.1  724.02
  5109.9  726.67  5123.8  728.22  5170.6  729.01  5182.1  729.77  5196.8  732.90
  5207.0  733.75  5301.5  736.63  5336.0  737.13  5382.2  740.17  5458.3  742.64
#Mann=4,-1,0
  4417.5    0.09       0  4924.7    0.12       0  4983.5   0.048       0
  5016.5    0.12       0
#XS Ineff=2,0
    0.00 4941.00  725.56 5059.00    0.00  725.92
Permanent Ineff=
       F       F
Bank Sta=4983.5,5016.5
XS Rating Curve= 0
Exp/Cntr=0.5,0.3

Type RM Length L Ch R = 1,18999,509,509,509
BEGIN DESCRIPTION:
Kerr Creek 37.0
END DESCRIPTION:
XS GIS Cut Line= 3
      1505783.98       686358.68      1506052.22       685895.10
      1506361.27       685568.55
#Sta/Elev= 30
  4466.5  747.29  4518.8  745.10  4563.3  741.29  4601.6  738.96  4617.5  738.88
  4670.2  734.68  4732.4  727.93  4741.6  726.33  4772.5  723.81  4861.3  720.57
  4944.8  719.54  4969.7  718.51  4988.5  716.02  4991.2  708.11  4992.2  706.11
  5007.8  706.11  5008.8  708.11  5024.6  712.96  5037.1  717.99  5060.5  719.65
  5083.0  719.68  5103.0  720.87  5116.4  722.44  5129.8  725.45  5144.1  727.17
  5218.5  733.62  5241.5  736.87  5374.6  743.38  5385.4  745.06  5451.7  751.93
#Mann=4,-1,0
  4466.5    0.09       0  4944.8    0.12       0  4991.2   0.048       0
  5008.8    0.12       0
Bank Sta=4991.2,5008.8
XS Rating Curve= 0
Exp/Cntr=0.3,0.1

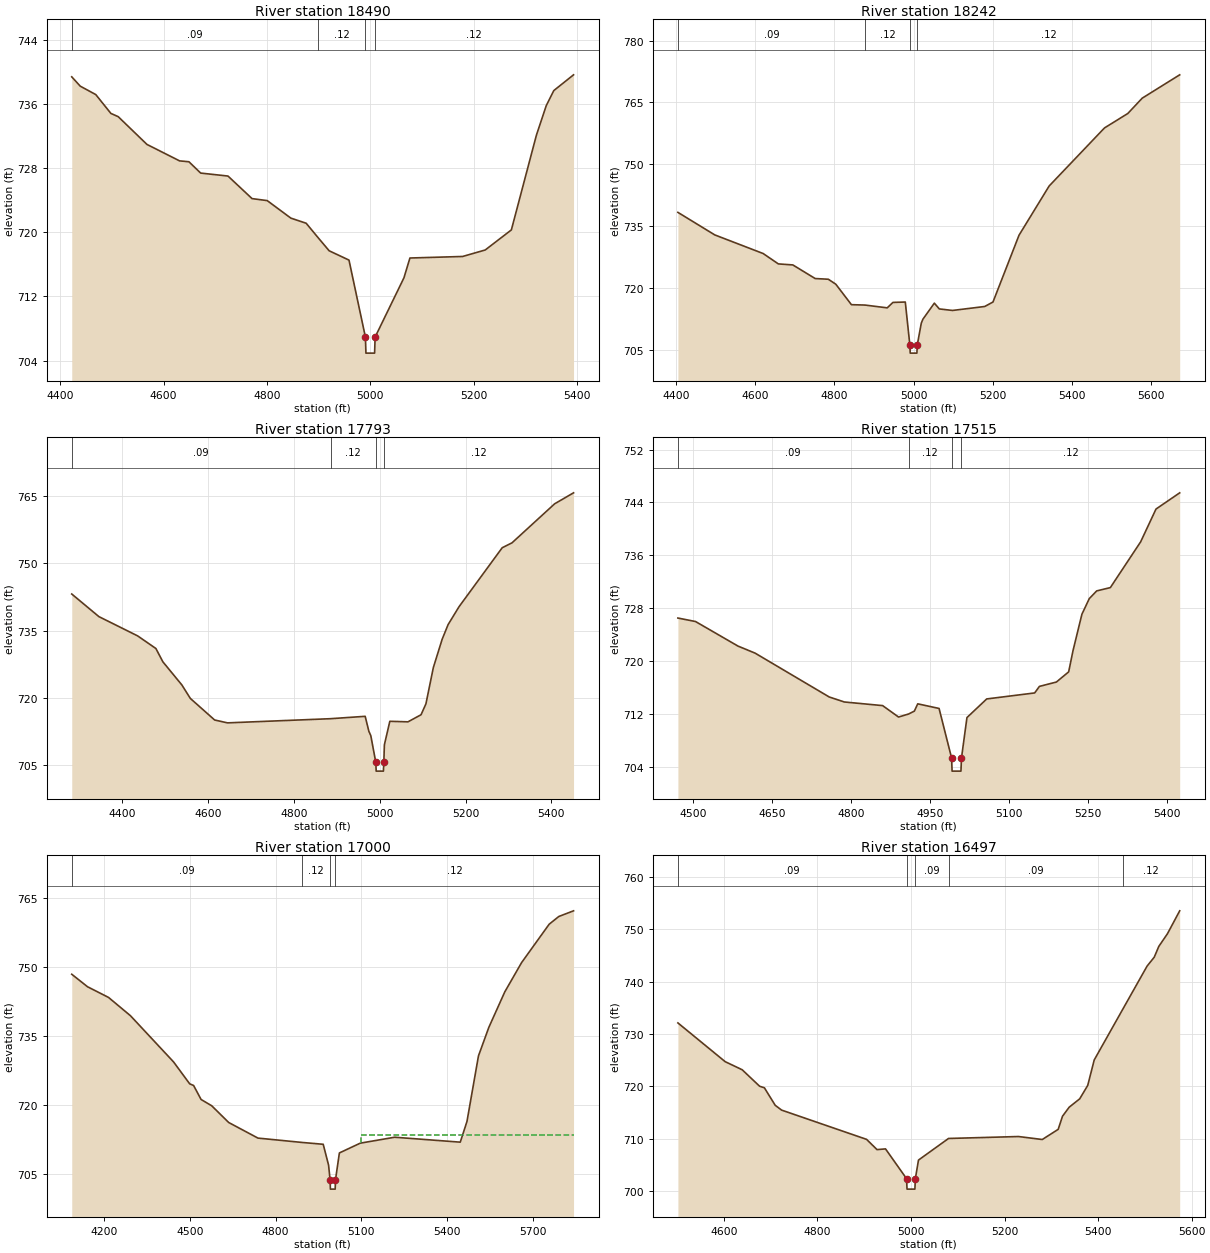
Type RM Length L Ch R = 1,18490,248,248,248
BEGIN DESCRIPTION:
Kerr Creek 36.0
END DESCRIPTION:
XS GIS Cut Line= 3
      1506122.22       686574.41      1506492.48       686134.18
      1506757.79       685839.71
#Sta/Elev= 30
  4422.0  739.36  4438.4  738.20  4468.5  737.15  4497.8  734.80  4511.9  734.40
  4567.6  730.94  4630.8  728.89  4648.9  728.78  4671.6  727.37  4724.5  727.00
  4771.1  724.19  4800.5  723.94  4846.2  721.76  4875.9  721.12  4899.7  719.27
  4920.4  717.69  4958.8  716.53  4990.6  706.94  4991.6  704.94  5008.4  704.94
  5009.4  706.94  5065.2  714.32  5076.8  716.79  5178.8  716.98  5222.6  717.79
  5273.2  720.29  5321.6  732.07  5340.8  735.78  5355.4  737.65  5393.6  739.61
#Mann=4,-1,0
  4422.0    0.09       0  4899.7    0.12       0  4990.6   0.048       0
  5009.4    0.12       0
Bank Sta=4990.6,5009.4
XS Rating Curve= 0
Exp/Cntr=0.3,0.1

Type RM Length L Ch R = 1,18242,449,449,449
BEGIN DESCRIPTION:
Kerr Creek 35.5
END DESCRIPTION:
XS GIS Cut Line= 3
      1506165.87       686596.07      1506680.51       686294.48
      1507311.31       686064.85
#Sta/Elev= 30
  4404.6  738.32  4497.8  732.85  4619.9  728.34  4658.4  725.82  4695.0  725.57
  4751.4  722.27  4784.6  722.10  4803.6  720.89  4843.0  715.93  4877.1  715.84
  4933.5  715.16  4947.9  716.48  4979.1  716.57  4990.6  706.18  4991.6  704.18
  5008.4  704.18  5009.4  706.18  5019.5  711.44  5023.5  712.39  5052.5  716.30
  5065.1  714.90  5098.4  714.53  5179.8  715.49  5200.7  716.58  5266.4  732.77
  5342.6  744.72  5482.4  758.80  5541.3  762.30  5577.7  766.02  5672.4  771.68
#Mann=4,-1,0
  4404.6    0.09       0  4877.1    0.12       0  4990.6   0.048       0
  5009.4    0.12       0
Bank Sta=4990.6,5009.4
XS Rating Curve= 0
Exp/Cntr=0.3,0.1

Type RM Length L Ch R = 1,17793,278,278,278
BEGIN DESCRIPTION:
Kerr Creek 35.0
END DESCRIPTION:
XS GIS Cut Line= 3
      1506337.43       686972.36      1506968.27       686637.58
      1507319.65       686347.06
#Sta/Elev= 30
  4281.7  743.15  4345.0  738.11  4435.4  733.81  4477.9  731.00  4494.2  728.03
  4538.5  722.87  4558.2  719.87  4614.9  715.06  4644.9  714.42  4885.2  715.35
  4965.9  715.88  4974.5  712.55  4979.1  711.55  4990.6  705.66  4991.6  703.66
  5008.4  703.66  5009.4  705.66  5010.7  709.53  5023.4  714.77  5065.7  714.65
  5096.2  716.23  5107.6  718.67  5124.9  726.76  5145.3  733.03  5159.3  736.33
  5184.8  740.32  5285.4  753.46  5308.3  754.56  5407.7  763.26  5451.8  765.71
#Mann=4,-1,0
  4281.7    0.09       0  4885.2    0.12       0  4990.6   0.048       0
  5009.4    0.12       0
Bank Sta=4990.6,5009.4
XS Rating Curve= 0
Exp/Cntr=0.3,0.1

Type RM Length L Ch R = 1,17515,515,515,515
BEGIN DESCRIPTION:
Kerr Creek 34.0
END DESCRIPTION:
XS GIS Cut Line= 3
      1506807.37       687250.86      1507148.50       686848.51
      1507448.81       686548.20
#Sta/Elev= 30
  4471.3  726.49  4504.8  725.96  4585.4  722.24  4617.7  721.18  4758.4  714.54
  4787.1  713.78  4859.8  713.23  4890.0  711.50  4909.0  711.96  4920.0  712.40
  4926.4  713.50  4966.9  712.80  4990.6  705.31  4991.6  703.31  5008.4  703.31
  5009.4  705.31  5019.8  711.42  5057.3  714.24  5148.3  715.15  5157.3  716.14
  5189.5  716.80  5212.8  718.34  5221.1  721.57  5237.9  727.06  5251.9  729.43
  5266.0  730.60  5291.9  731.10  5349.4  738.03  5378.5  742.99  5423.5  745.45
#Mann=4,-1,0
  4471.3    0.09       0  4909.0    0.12       0  4990.6   0.048       0
  5009.4    0.12       0
Bank Sta=4990.6,5009.4
XS Rating Curve= 0
Exp/Cntr=0.3,0.1

Type RM Length L Ch R = 1,17000,503,503,503
BEGIN DESCRIPTION:
Kerr Creek 33.0
END DESCRIPTION:
XS GIS Cut Line= 3
      1506661.77       687760.60      1507431.31       687268.36
      1508253.09       687085.88
#Sta/Elev= 30
  4086.9  748.38  4142.0  745.67  4215.6  743.35  4292.3  739.38  4442.9  729.37
  4499.5  724.60  4513.1  724.25  4539.3  721.21  4576.6  719.84  4635.8  716.22
  4738.3  712.83  4894.0  711.88  4966.5  711.49  4985.3  706.96  4990.6  703.76
  4991.6  701.76  5008.4  701.76  5009.4  703.76  5023.1  709.61  5096.0  711.73
  5216.4  713.02  5445.9  711.95  5469.4  716.44  5509.6  730.66  5545.9  736.86
  5601.8  744.57  5660.6  750.92  5757.0  759.24  5790.6  760.91  5842.2  762.14
#Mann=4,-1,0
  4086.9    0.09       0  4894.0    0.12       0  4990.6   0.048       0
  5009.4    0.12       0
#XS Ineff=2,0
       0                 5100.00    0.00  713.50
Permanent Ineff=
       F       F
Bank Sta=4990.6,5009.4
XS Rating Curve= 0
Exp/Cntr=0.3,0.1

Type RM Length L Ch R = 1,16497,320,320,320
BEGIN DESCRIPTION:
Kerr Creek 32.0
END DESCRIPTION:
XS GIS Cut Line= 3
      1507128.13       687886.46      1507600.42       687740.69
      1508160.18       687594.92
#Sta/Elev= 30
  4501.8  732.09  4602.8  724.69  4639.2  723.14  4676.5  719.99  4686.7  719.69
  4709.8  716.35  4723.5  715.43  4905.1  709.84  4927.5  707.88  4945.6  708.02
  4990.6  702.33  4991.6  700.33  5008.4  700.33  5009.4  702.33  5016.1  705.88
  5080.3  710.01  5229.9  710.38  5280.7  709.81  5314.7  711.75  5324.0  714.26
  5338.3  715.99  5360.7  717.58  5377.9  720.15  5391.8  725.02  5452.4  734.64
  5504.8  742.95  5520.0  744.64  5529.9  746.72  5548.3  749.13  5574.5  753.51
#Mann=5,-1,0
  4501.8    0.09       0  4990.6   0.048       0  5009.4    0.09       0
  5080.3    0.09       0  5452.4    0.12       0
Bank Sta=4990.6,5009.4
XS Rating Curve= 0
Exp/Cntr=0.3,0.1