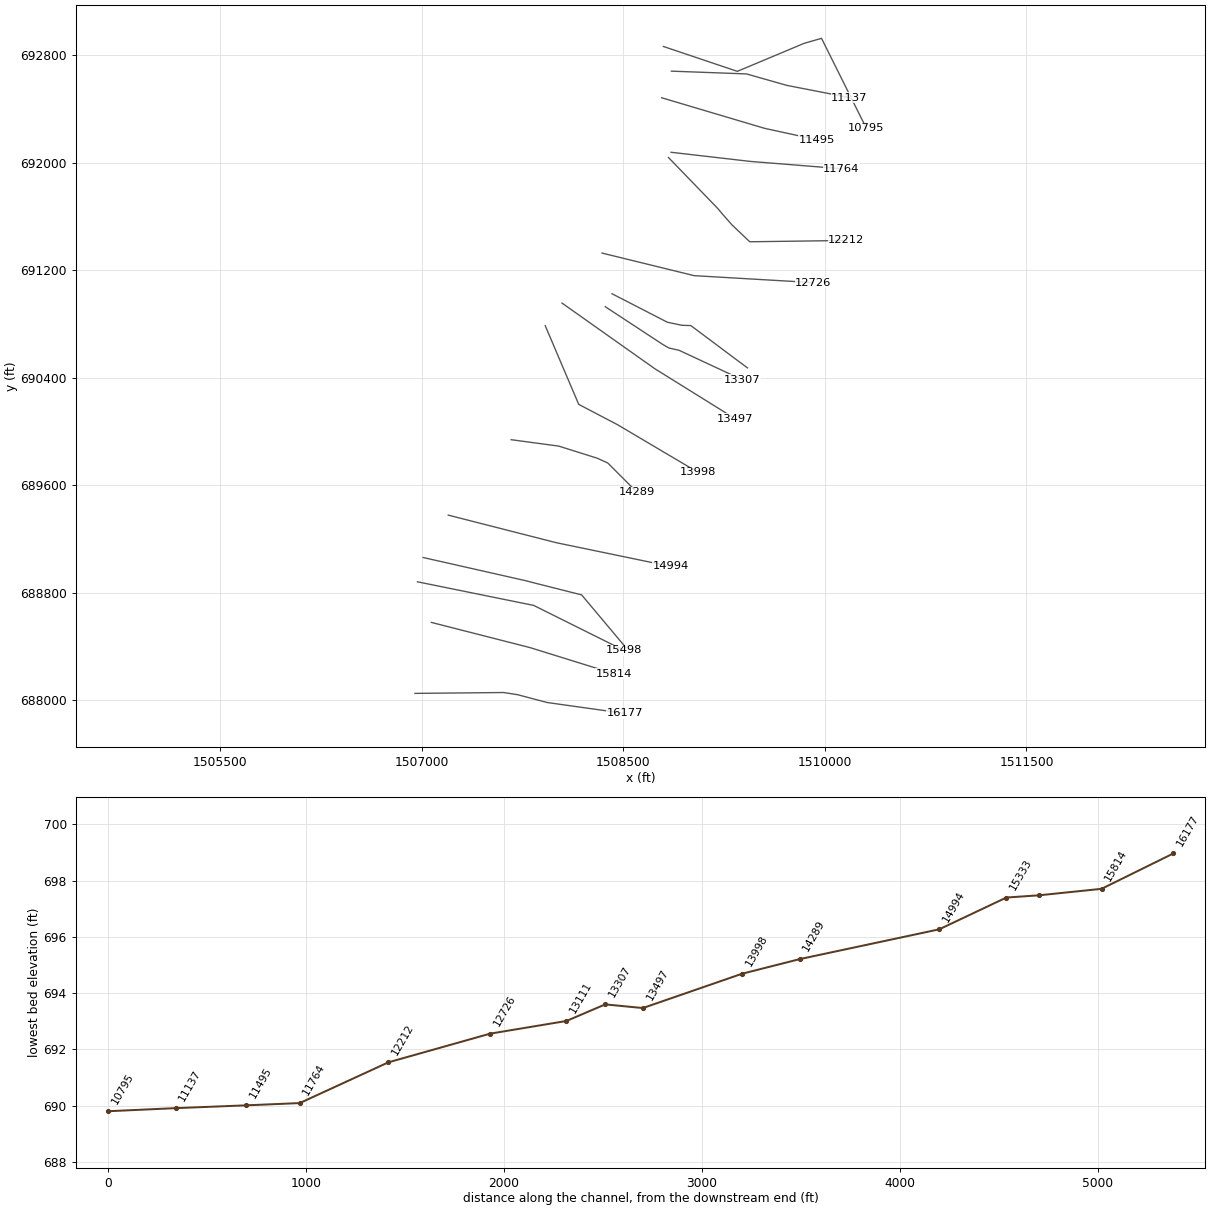
HEC-RAS study Kerr Creek.prj: .Kerr Creek Limited Detail Study

--- Kerr Creek.g01 (geometry) --- (continued)

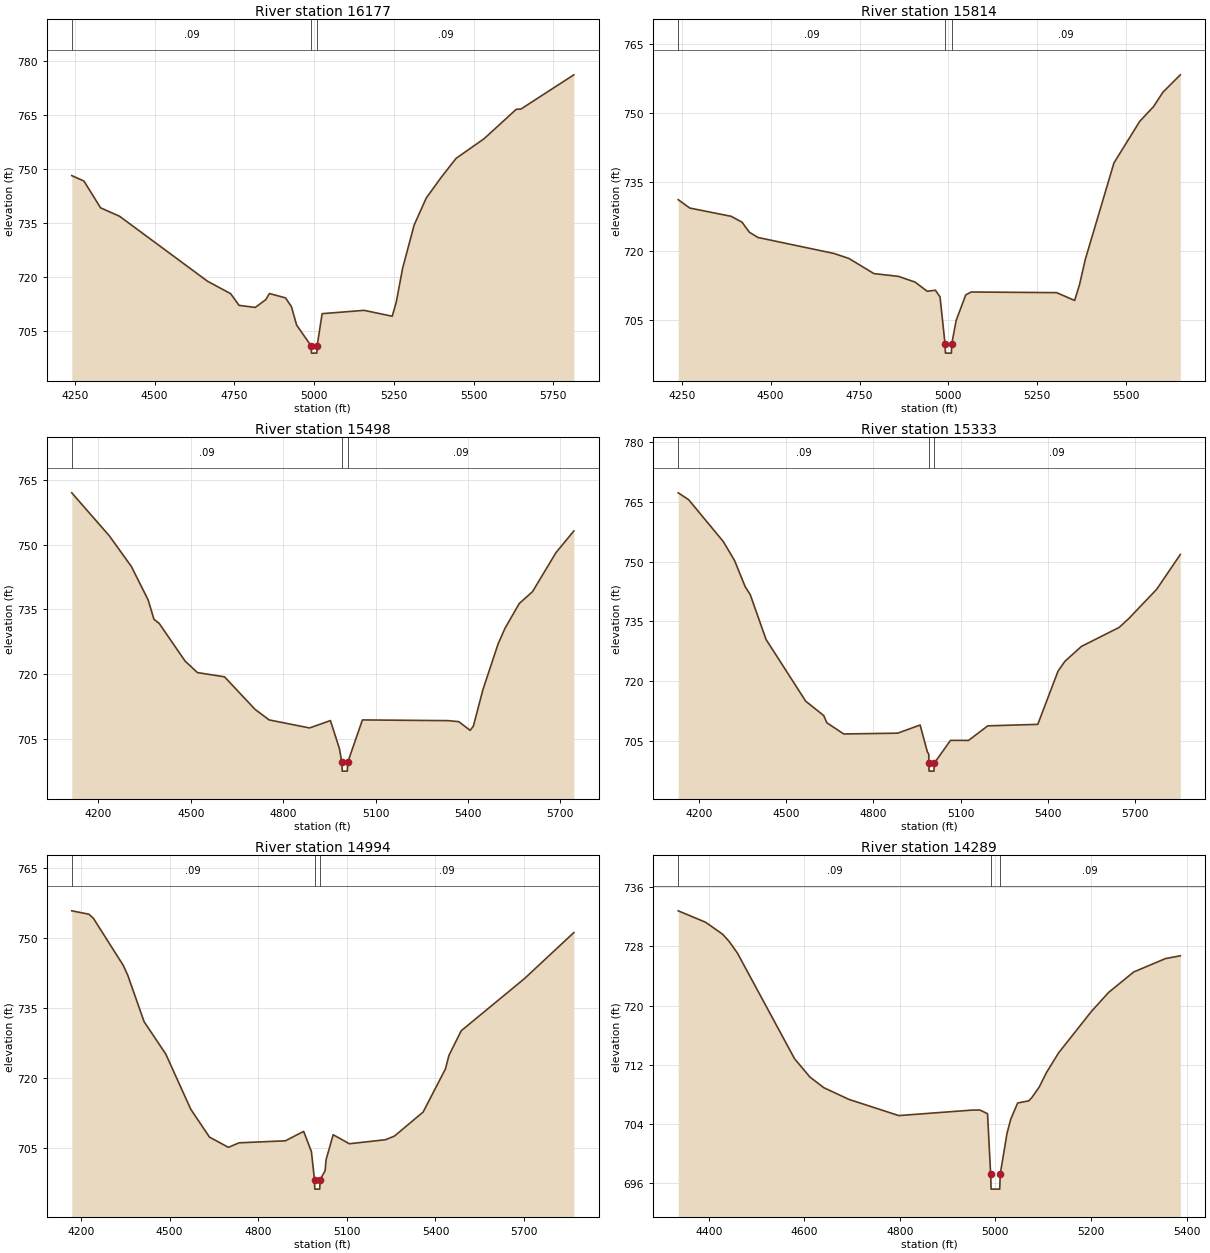
Type RM Length L Ch R = 1,16177,363,363,363
BEGIN DESCRIPTION:
Kerr Creek 31.0
END DESCRIPTION:
XS GIS Cut Line= 5
      1506950.18       688050.10      1507610.10       688056.57
      1507713.61       688040.40      1507933.59       687982.17
      1508509.37       687901.30
#Sta/Elev= 30
  4240.3  748.14  4278.5  746.64  4330.6  739.22  4390.2  736.88  4665.6  718.90
  4738.4  715.43  4764.6  712.20  4815.5  711.63  4848.4  713.79  4859.8  715.48
  4910.4  714.27  4928.8  711.85  4945.1  706.74  4990.6  700.97  4991.6  698.97
  5008.4  698.97  5009.4  700.97  5025.0  709.90  5156.7  710.82  5244.7  709.19
  5257.3  713.06  5277.3  722.47  5313.4  734.45  5351.4  741.94  5398.6  747.70
  5444.8  752.91  5532.5  758.35  5633.5  766.51  5648.2  766.58  5814.0  776.06
#Mann=3,-1,0
  4240.3    0.09       0  4990.6   0.048       0  5009.4    0.09       0
Bank Sta=4990.6,5009.4
XS Rating Curve= 0
Exp/Cntr=0.3,0.1

Type RM Length L Ch R = 1,15814,316,316,316
BEGIN DESCRIPTION:
Kerr Creek 30.0
END DESCRIPTION:
XS GIS Cut Line= 3
      1507071.77       688578.70      1507806.13       688391.06
      1508430.50       688196.96
#Sta/Elev= 30
  4240.3  731.12  4272.8  729.30  4389.2  727.50  4419.7  726.22  4440.3  724.04
  4464.6  722.89  4677.8  719.42  4720.3  718.32  4790.6  715.03  4859.7  714.42
  4906.3  713.18  4940.4  711.18  4963.4  711.40  4976.4  709.97  4990.6  699.71
  4991.6  697.71  5008.4  697.71  5009.4  699.71  5021.8  704.82  5048.7  710.38
  5064.1  711.02  5304.2  710.88  5355.0  709.18  5368.7  712.63  5384.9  718.11
  5465.5  739.13  5538.1  748.19  5576.8  751.39  5603.3  754.54  5652.1  758.31
#Mann=3,-1,0
  4240.3    0.09       0  4990.6   0.048       0  5009.4    0.09       0
Bank Sta=4990.6,5009.4
XS Rating Curve= 0
Exp/Cntr=0.3,0.1

Type RM Length L Ch R = 1,15498,165,165,165
BEGIN DESCRIPTION:
Kerr Creek 29.0
END DESCRIPTION:
XS GIS Cut Line= 3
      1506968.51       688880.98      1507833.67       688705.18
      1508502.63       688371.73
#Sta/Elev= 30
  4113.5  761.99  4235.6  752.01  4306.9  744.93  4361.5  737.17  4380.4  732.68
  4397.3  731.73  4481.4  723.00  4521.6  720.32  4609.5  719.34  4708.6  711.80
  4754.5  709.35  4885.7  707.49  4953.4  709.20  4982.6  702.71  4990.6  699.48
  4991.6  697.48  5008.4  697.48  5009.4  699.48  5057.3  709.35  5336.3  709.18
  5370.4  708.94  5407.1  706.93  5417.6  707.92  5448.5  716.35  5497.6  726.91
  5520.1  730.57  5566.5  736.33  5609.6  739.08  5685.6  748.11  5743.8  753.15
#Mann=3,-1,0
  4113.5    0.09       0  4990.6   0.048       0  5009.4    0.09       0
Bank Sta=4990.6,5009.4
XS Rating Curve= 0
Exp/Cntr=0.3,0.1

Type RM Length L Ch R = 1,15333,339,339,339
BEGIN DESCRIPTION:
Kerr Creek 28.5
END DESCRIPTION:
XS GIS Cut Line= 5
      1507011.37       689061.81      1507771.29       688889.75
      1507860.19       688866.81      1508189.98       688783.64
      1508520.30       688389.94
#Sta/Elev= 30
  4129.7  767.27  4165.2  765.57  4284.8  755.01  4323.5  750.24  4359.6  743.72
  4377.1  741.71  4431.5  730.45  4567.7  714.96  4629.5  711.35  4640.2  709.55
  4698.3  706.73  4883.9  706.93  4960.7  708.98  4985.5  702.27  4990.5  701.65
  4990.6  699.40  4991.6  697.40  5008.4  697.40  5009.4  699.40  5065.1  705.12
  5127.2  705.11  5193.2  708.77  5365.0  709.14  5434.6  722.50  5457.8  724.94
  5515.1  728.72  5644.6  733.48  5678.2  735.74  5773.6  743.06  5854.7  751.79
#Mann=3,-1,0
  4129.7    0.09       0  4990.6   0.048       0  5009.4    0.09       0
Bank Sta=4990.6,5009.4
XS Rating Curve= 0
Exp/Cntr=0.3,0.1

Type RM Length L Ch R = 1,14994,705,705,705
BEGIN DESCRIPTION:
Kerr Creek 28.0
END DESCRIPTION:
XS GIS Cut Line= 3
      1507197.67       689377.49      1508001.03       689172.27
      1508852.73       688995.55
#Sta/Elev= 30
  4169.2  755.76  4227.3  755.04  4242.6  754.14  4343.2  744.13  4358.5  742.03
  4414.0  732.06  4487.3  725.15  4571.7  713.37  4635.2  707.39  4699.3  705.20
  4735.3  706.17  4892.0  706.60  4953.9  708.61  4980.1  704.31  4990.6  698.27
  4991.6  696.27  5008.4  696.27  5009.4  698.27  5026.6  700.22  5029.6  702.53
  5053.8  707.90  5108.5  705.97  5230.8  706.83  5261.4  707.62  5358.2  712.75
  5433.6  721.95  5445.6  724.86  5487.0  730.12  5701.1  741.27  5868.2  751.11
#Mann=3,-1,0
  4169.2    0.09       0  4990.6   0.048       0  5009.4    0.09       0
Bank Sta=4990.6,5009.4
XS Rating Curve= 0
Exp/Cntr=0.3,0.1

Type RM Length L Ch R = 1,14289,291,291,291
BEGIN DESCRIPTION:
Kerr Creek 27.0
END DESCRIPTION:
XS GIS Cut Line= 5
      1507665.76       689939.07      1508019.64       689891.42
      1508307.54       689800.84      1508385.18       689765.26
      1508601.64       689548.39
#Sta/Elev= 30
  4336.2  732.79  4393.4  731.25  4428.9  729.64  4442.5  728.68  4460.1  727.08
  4579.6  712.82  4611.7  710.35  4640.8  708.91  4693.3  707.33  4797.7  705.14
  4950.7  705.88  4967.7  705.89  4983.5  705.39  4990.0  697.21  4991.0  695.21
  5009.0  695.21  5010.0  697.21  5024.2  702.73  5032.0  704.64  5046.5  706.84
  5069.7  707.13  5076.2  707.57  5091.6  708.99  5106.7  710.94  5132.1  713.60
  5200.9  719.21  5237.0  721.78  5289.3  724.53  5355.8  726.34  5386.9  726.72
#Mann=3,-1,0
  4336.2    0.09       0  4990.0   0.048       0  5010.0    0.09       0
Bank Sta=4990,5010
XS Rating Curve= 0
Exp/Cntr=0.3,0.1

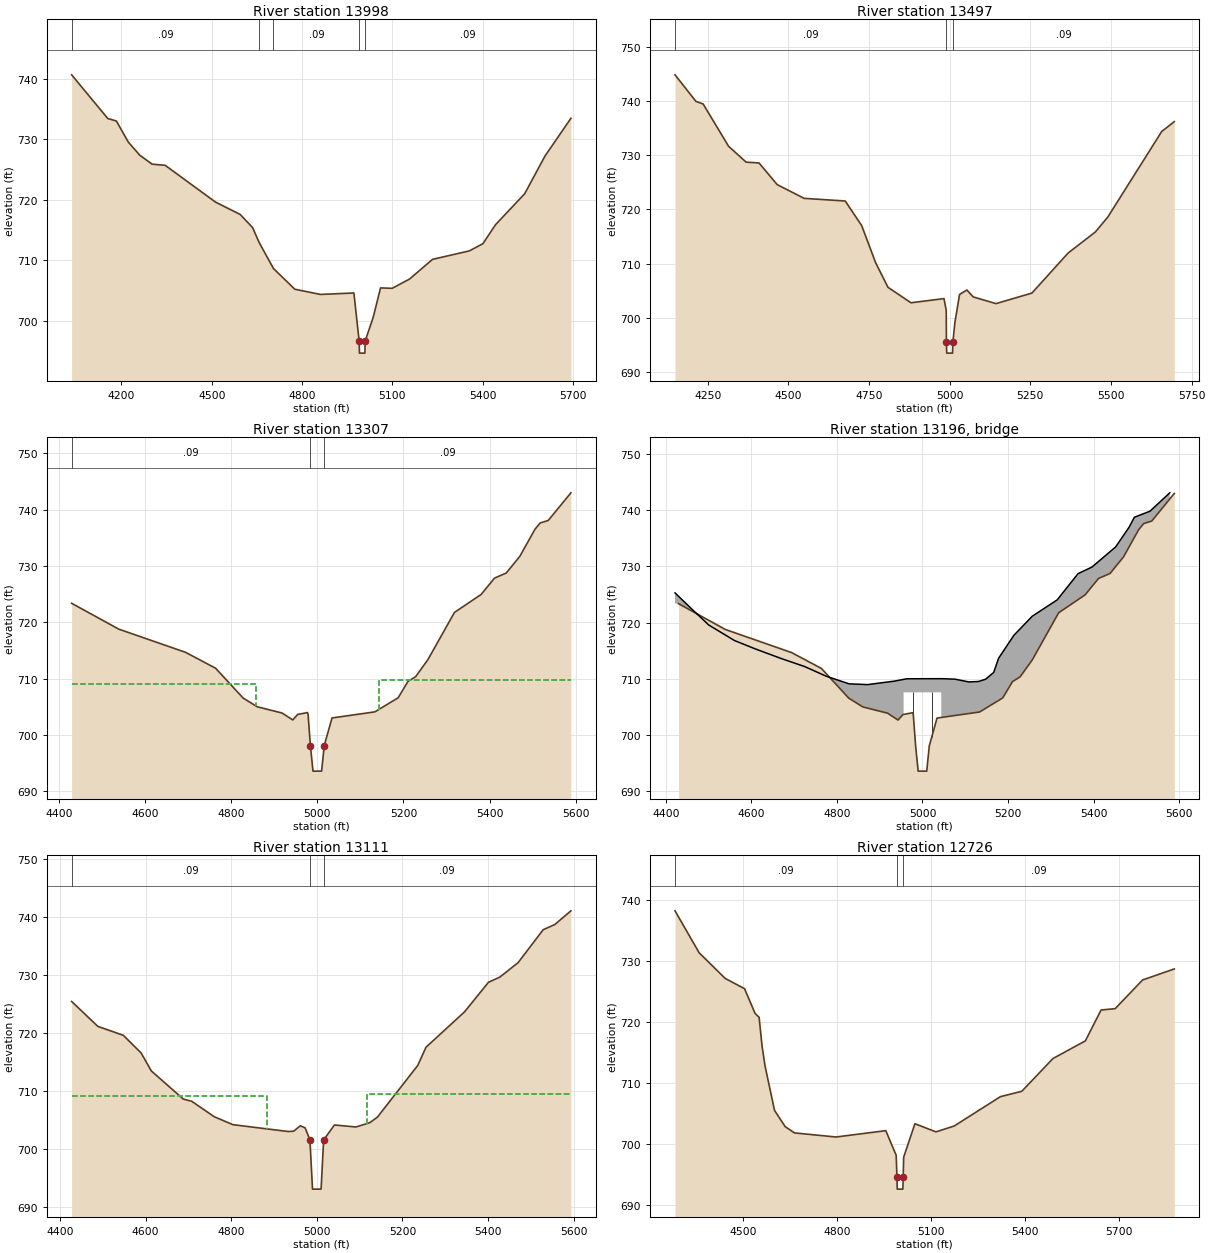
Type RM Length L Ch R = 1,13998,501,501,501
BEGIN DESCRIPTION:
Kerr Creek 26.0
END DESCRIPTION:
XS GIS Cut Line= 4
      1507919.36       690787.80      1508168.48       690202.07
      1508458.78       690049.87      1509056.47       689695.76
#Sta/Elev= 30
  4034.6  740.64  4154.7  733.43  4183.4  733.01  4222.6  729.56  4261.2  727.36
  4302.1  725.89  4345.5  725.70  4512.9  719.62  4594.6  717.59  4635.9  715.42
  4657.7  712.96  4705.3  708.66  4776.2  705.24  4861.2  704.38  4972.5  704.62
  4990.0  696.69  4991.0  694.69  5009.0  694.69  5010.0  696.69  5036.7  700.60
  5061.1  705.46  5099.7  705.39  5157.4  706.92  5233.7  710.17  5356.2  711.57
  5401.2  712.76  5443.1  715.89  5540.2  721.02  5607.4  727.22  5693.6  733.46
#Mann=5,-1,0
  4034.6    0.09       0  4657.7    0.11       0  4705.3    0.09       0
  4990.0   0.048       0  5010.0    0.09       0
Bank Sta=4990,5010
XS Rating Curve= 0
Exp/Cntr=0.3,0.1

Type RM Length L Ch R = 1,13497,190,190,190
BEGIN DESCRIPTION:
Kerr Creek 25.0
END DESCRIPTION:
XS GIS Cut Line= 3
      1508044.31       690956.17      1508735.77       690466.81
      1509330.20       690096.79
#Sta/Elev= 30
  4148.9  744.86  4213.9  739.95  4236.0  739.48  4315.0  731.66  4369.3  728.74
  4409.3  728.58  4465.7  724.58  4549.1  722.05  4676.4  721.56  4727.5  717.01
  4770.6  710.17  4809.0  705.62  4880.1  702.77  4982.5  703.54  4989.4  701.37
  4990.0  695.47  4991.0  693.47  5009.0  693.47  5010.0  695.47  5016.4  699.18
  5030.8  704.31  5053.5  705.12  5073.1  703.85  5143.6  702.61  5254.9  704.56
  5367.3  711.96  5451.5  715.84  5490.2  718.60  5657.2  734.39  5696.2  736.22
#Mann=3,-1,0
  4148.9    0.09       0  4990.0   0.048       0  5010.0    0.09       0
Bank Sta=4990,5010
XS Rating Curve= 0
Exp/Cntr=0.5,0.3

Type RM Length L Ch R = 1,13307,196,196,196
BEGIN DESCRIPTION:
Fannie Sloan Road (Kerr) us
END DESCRIPTION:
XS GIS Cut Line= 5
      1508366.19       690929.17      1508793.67       690648.35
      1508839.56       690621.92      1508915.36       690604.67
      1509383.34       690386.27
#Sta/Elev= 30
  4429.9  723.37  4539.4  718.78  4694.3  714.67  4764.0  711.85  4827.8  706.57
  4860.5  705.02  4918.4  703.90  4943.0  702.68  4954.6  703.66  4977.2  703.98
  4978.6  703.66  4984.0  698.10  4990.0  693.60  5010.0  693.60  5016.0  698.10
  5034.1  703.03  5133.6  704.11  5187.6  706.61  5210.4  709.51  5228.3  710.36
  5256.9  713.40  5318.3  721.75  5380.1  724.93  5411.2  727.83  5438.5  728.74
  5470.0  731.70  5505.3  736.52  5517.1  737.61  5535.8  738.05  5588.5  742.96
#Mann=3,-1,0
  4429.9    0.09       0  4984.0   0.048       0  5016.0    0.09       0
#XS Ineff=2,0
    0.00 4857.50  709.02 5142.50    0.00  709.85
Permanent Ineff=
       F       F
Bank Sta=4984,5016
XS Rating Curve= 0
Exp/Cntr=0.5,0.3

Type RM Length L Ch R =3,13196,,,
BEGIN DESCRIPTION:
Fannie Sloan Road TOR (Kerr)
Structure ID: LDS_KC_04
Approximate Survey Structure
END DESCRIPTION:
Bridge Culvert--1,0,-1,-1,0
Deck Dist Width WeirC Skew NumUp NumDn MinLoCord MaxHiCord MaxSubmerge Is_Ogee
98.5,25,3,,33,33,,,,0,1,1,,,
  4421.8  4462.3  4500.7  4560.9  4609.6  4670.8  4724.7  4774.8  4828.4  4871.6
  4933.7  4956.0  4956.0  4964.1  5044.0  5044.0  5046.4  5076.1  5108.1  5130.8
  5147.7  5166.6  5177.9  5213.8  5256.8  5314.7  5363.5  5396.2  5451.4  5482.9
  5495.2  5531.6  5577.9
  725.28  722.32  719.57  716.81  715.32  713.59  712.19  710.48  709.12  708.98
  709.59  709.91  709.91  710.02  710.03  710.03  710.03  709.95  709.46  709.53
  709.94  711.16  713.66  717.76  721.15  724.03  728.70  729.88  733.45  736.96
  738.73  739.80  743.07
  673.26  673.26  673.26  673.26  673.26  673.26  673.26  673.26  673.26  673.26
  673.26  673.26  707.60  707.60  707.60  673.26  673.26  673.26  673.26  673.26
  673.26  673.26  673.26  673.26  673.26  673.26  673.26  673.26  673.26  673.26
  673.26  673.26  673.26
  4421.8  4462.3  4500.7  4560.9  4609.6  4670.8  4724.7  4774.8  4828.4  4871.6
  4933.7  4956.0  4956.0  4964.1  5044.0  5044.0  5046.4  5076.1  5108.1  5130.8
  5147.7  5166.6  5177.9  5213.8  5256.8  5314.7  5363.5  5396.2  5451.4  5482.9
  5495.2  5531.6  5577.9
  725.28  722.32  719.57  716.81  715.32  713.59  712.19  710.48  709.12  708.98
  709.59  709.91  709.91  710.02  710.03  710.03  710.03  709.95  709.46  709.53
  709.94  711.16  713.66  717.76  721.15  724.03  728.70  729.88  733.45  736.96
  738.73  739.80  743.07
  673.26  673.26  673.26  673.26  673.26  673.26  673.26  673.26  673.26  673.26
  673.26  673.26  707.60  707.60  707.60  673.26  673.26  673.26  673.26  673.26
  673.26  673.26  673.26  673.26  673.26  673.26  673.26  673.26  673.26  673.26
  673.26  673.26  673.26
Pier Skew, UpSta & Num, DnSta & Num=,4978,2,4978,2,0,0,0,0,0
       1       1
  703.80  707.60
       1       1
  703.72  707.60
Pier Skew, UpSta & Num, DnSta & Num=,5022,2,5022,2,0,0,0,0,0
       1       1
  700.86  707.60
       1       1
  699.52  707.60
BR Coef=1,1,0,1.25,0,,,0.8,0,2,0,
WSPro=,,,, 1 ,,,, 0 ,,,, 0 ,,,,-1 ,-1 ,-1 , 0 , 0 , 0 , 0 , 0
BC Design=,,0,,0,,,,,,

Type RM Length L Ch R = 1,13111,385,385,385
BEGIN DESCRIPTION:
Fannie Sloan Road (Kerr) ds
END DESCRIPTION:
XS GIS Cut Line= 5
      1508416.10       691025.90      1508827.99       690813.72
      1508935.78       690791.02      1509002.72       690788.76
      1509423.92       690473.63
#Sta/Elev= 30
  4427.2  725.45  4488.4  721.14  4548.1  719.59  4589.8  716.52  4613.5  713.43
  4688.2  708.57  4707.6  708.20  4760.5  705.52  4804.0  704.15  4933.0  702.97
  4945.9  703.02  4961.4  703.96  4972.7  703.60  4984.0  701.51  4990.0  693.01
  5010.0  693.01  5016.0  701.51  5041.2  704.10  5091.5  703.75  5123.8  704.49
  5141.7  705.46  5235.9  714.39  5255.1  717.53  5345.2  723.65  5401.1  728.76
  5427.6  729.65  5470.5  732.17  5528.9  737.84  5556.4  738.76  5593.7  741.11
#Mann=3,-1,0
  4427.2    0.09       0  4984.0   0.048       0  5016.0    0.09       0
#XS Ineff=2,0
    0.00 4883.50  709.03 5116.50    0.00  709.37
Permanent Ineff=
       F       F
Bank Sta=4984,5016
XS Rating Curve= 0
Exp/Cntr=0.5,0.3

Type RM Length L Ch R = 1,12726,514,514,514
BEGIN DESCRIPTION:
Kerr Creek 24.0
END DESCRIPTION:
XS GIS Cut Line= 3
      1508341.83       691328.69      1509027.64       691160.48
      1509913.99       691108.72
#Sta/Elev= 30
  4281.5  738.16  4358.5  731.29  4441.6  727.09  4503.5  725.40  4537.0  721.36
  4550.0  720.71  4559.5  715.96  4568.9  712.74  4599.3  705.45  4633.4  702.79
  4663.0  701.77  4795.4  701.10  4954.4  702.14  4987.6  698.11  4990.0  694.56
  4991.0  692.56  5009.0  692.56  5010.0  694.56  5011.5  697.79  5047.4  703.28
  5114.4  701.94  5172.8  702.90  5320.3  707.71  5388.6  708.59  5488.2  713.96
  5591.6  716.85  5641.8  721.91  5686.7  722.13  5774.3  726.83  5875.5  728.64
#Mann=3,-1,0
  4281.5    0.09       0  4990.0   0.048       0  5010.0    0.09       0
Bank Sta=4990,5010
XS Rating Curve= 0
Exp/Cntr=0.3,0.1

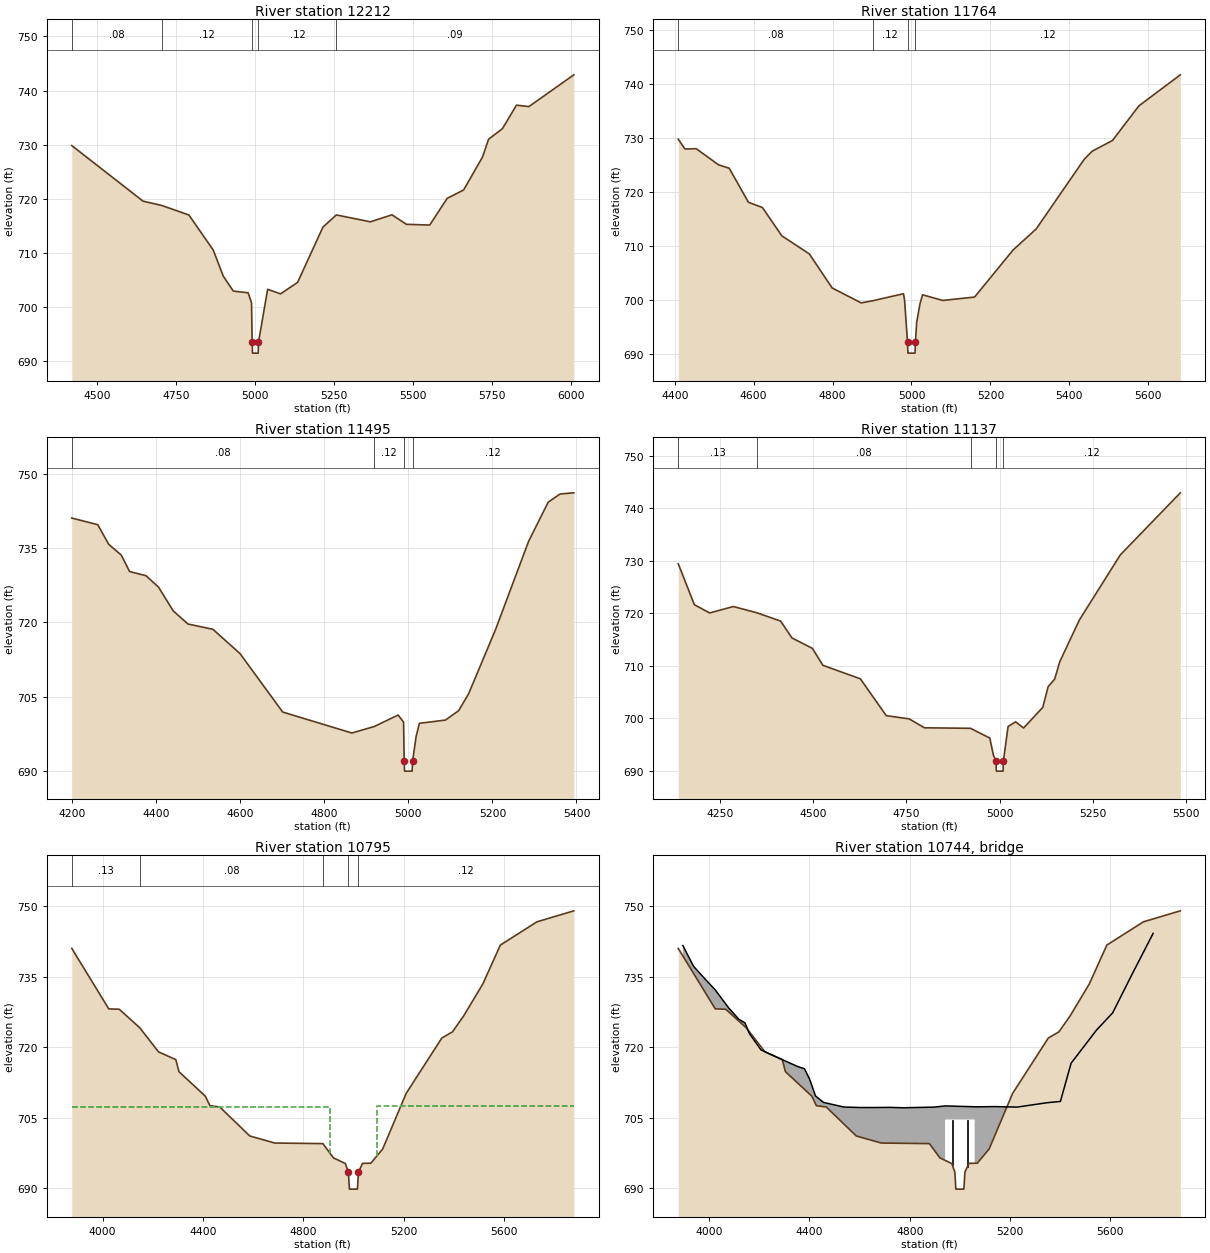
Type RM Length L Ch R = 1,12212,448,448,448
BEGIN DESCRIPTION:
Kerr Creek 23.0
END DESCRIPTION:
XS GIS Cut Line= 6
      1508836.15       692040.35      1509204.91       691658.65
      1509237.26       691619.83      1509308.43       691538.96
      1509441.06       691412.80      1510159.25       691422.50
#Sta/Elev= 30
  4418.6  729.85  4644.5  719.59  4704.0  718.79  4789.6  717.04  4866.8  710.56
  4898.5  705.75  4930.3  702.99  4977.2  702.68  4988.0  700.83  4990.0  693.54
  4991.0  691.54  5009.0  691.54  5010.0  693.54  5039.0  703.32  5080.1  702.48
  5133.9  704.60  5214.2  714.80  5256.6  717.05  5364.4  715.78  5432.9  717.07
  5478.6  715.32  5552.4  715.18  5607.7  720.11  5659.7  721.65  5719.3  727.70
  5738.9  731.03  5782.8  732.98  5827.1  737.31  5866.6  737.05  6008.9  742.91
#Mann=5,-1,0
  4418.6    0.08       0  4704.0    0.12       0  4990.0   0.048       0
  5010.0    0.12       0  5256.6    0.09       0
Bank Sta=4990,5010
XS Rating Curve= 0
Exp/Cntr=0.3,0.1

Type RM Length L Ch R = 1,11764,269,269,269
BEGIN DESCRIPTION:
Kerr Creek 22.0
END DESCRIPTION:
XS GIS Cut Line= 3
      1508855.54       692079.19      1509444.29       692011.26
      1510122.06       691956.83
#Sta/Elev= 30
  4408.8  729.71  4425.8  727.88  4454.5  727.93  4511.0  724.95  4538.0  724.32
  4586.8  718.01  4622.3  717.04  4671.3  711.81  4741.1  708.46  4799.0  702.15
  4872.6  699.39  4901.5  699.78  4979.8  701.09  4982.6  699.81  4990.0  692.09
  4991.0  690.09  5009.0  690.09  5010.0  692.09  5013.2  695.79  5021.5  699.21
  5028.1  700.89  5079.4  699.84  5159.9  700.47  5257.5  709.18  5316.1  713.08
  5438.1  726.00  5458.0  727.47  5509.5  729.46  5576.5  735.87  5681.4  741.61
#Mann=4,-1,0
  4408.8    0.08       0  4901.5    0.12       0  4990.0   0.048       0
  5010.0    0.12       0
Bank Sta=4990,5010
XS Rating Curve= 0
Exp/Cntr=0.3,0.1

Type RM Length L Ch R = 1,11495,358,358,358
BEGIN DESCRIPTION:
Kerr Creek 21.0
END DESCRIPTION:
XS GIS Cut Line= 3
      1508785.28       692485.17      1509550.98       692257.58
      1509937.48       692173.25
#Sta/Elev= 30
  4199.3  741.07  4261.2  739.73  4287.2  735.77  4317.1  733.60  4336.9  730.28
  4375.8  729.44  4405.6  727.15  4440.6  722.35  4475.7  719.69  4535.0  718.63
  4599.5  713.73  4701.1  701.93  4865.7  697.70  4919.2  699.02  4975.6  701.33
  4988.7  699.89  4990.0  692.01  4991.0  690.01  5009.0  690.01  5010.0  692.01
  5018.4  696.97  5026.3  699.66  5088.3  700.31  5119.8  702.22  5143.5  705.64
  5207.4  718.57  5286.0  736.36  5332.6  744.27  5361.1  745.93  5393.7  746.16
#Mann=4,-1,0
  4199.3    0.08       0  4919.2    0.12       0  4990.0   0.048       0
  5010.0    0.12       0
Bank Sta=4990,5010
XS Rating Curve= 0
Exp/Cntr=0.3,0.1

Type RM Length L Ch R = 1,11137,342,342,342
BEGIN DESCRIPTION:
Kerr Creek 20.0
END DESCRIPTION:
XS GIS Cut Line= 4
      1508858.04       692683.28      1509416.99       692662.58
      1509717.19       692577.18      1510183.02       692486.60
#Sta/Elev= 30
  4138.2  729.44  4181.5  721.63  4222.3  720.05  4285.8  721.28  4349.1  720.09
  4412.6  718.51  4443.2  715.29  4497.8  713.31  4526.0  710.08  4626.5  707.50
  4695.9  700.48  4757.3  699.87  4798.2  698.17  4921.9  698.07  4973.5  696.21
  4983.1  692.96  4990.0  691.91  4991.0  689.91  5009.0  689.91  5010.0  691.91
  5022.5  698.41  5042.7  699.31  5064.0  698.13  5115.5  702.06  5129.8  706.00
  5147.4  707.45  5161.0  710.75  5213.5  718.70  5323.3  731.12  5484.2  742.95
#Mann=5,-1,0
  4138.2    0.13       0  4349.1    0.08       0  4921.9    0.12       0
  4990.0   0.048       0  5010.0    0.12       0
Bank Sta=4990,5010
XS Rating Curve= 0
Exp/Cntr=0.5,0.3

Type RM Length L Ch R = 1,10795,168,168,168
BEGIN DESCRIPTION:
Mooresville Road (Kerr) us
END DESCRIPTION:
XS GIS Cut Line= 5
      1508798.45       692867.03      1509348.67       692681.73
      1509845.45       692890.28      1509974.95       692927.58
      1510308.58       692257.92
#Sta/Elev= 30
  3876.8  740.99  4024.3  728.13  4066.4  728.04  4148.1  724.10  4222.8  718.98
  4291.7  717.34  4304.3  714.77  4409.6  709.56  4427.7  707.54  4467.0  707.27
  4586.8  701.10  4686.5  699.60  4878.2  699.48  4920.5  696.44  4967.9  695.24
  4980.0  693.40  4984.0  689.80  5016.0  689.80  5020.0  693.40  5036.2  695.28
  5069.5  695.31  5116.8  698.34  5210.5  710.17  5352.6  721.92  5395.0  723.24
  5439.6  726.62  5516.0  733.41  5586.0  741.68  5731.8  746.63  5879.1  748.97
#Mann=5,-1,0
  3876.8    0.13       0  4148.1    0.08       0  4878.2    0.12       0
  4980.0   0.048       0  5020.0    0.12       0
#XS Ineff=2,0
    0.00 4905.50  707.24 5094.50    0.00  707.44
Permanent Ineff=
       F       F
Bank Sta=4980,5020
XS Rating Curve= 0
Exp/Cntr=0.5,0.3

Type RM Length L Ch R =3,10744,,,
BEGIN DESCRIPTION:
Mooresville Road TOR (Kerr)
Structure ID: LDS_KC_03
Approximate Survey Structure
END DESCRIPTION:
Bridge Culvert--1,0,-1,-1,0
Deck Dist Width WeirC Skew NumUp NumDn MinLoCord MaxHiCord MaxSubmerge Is_Ogee
35.5,31,3,,36,36,,,,0,1,1,,,
  3895.4  3937.8  3981.3  4024.6  4079.3  4118.0  4143.0  4160.6  4206.6  4268.6
  4354.6  4380.3  4400.6  4424.3  4456.1  4536.8  4603.6  4656.5  4721.9  4773.5
  4895.2  4941.0  4941.0  4942.8  5059.0  5059.0  5066.9  5141.5  5227.9  5349.0
  5400.8  5443.6  5545.1  5609.2  5688.2  5770.7
  741.58  737.17  734.62  732.14  728.24  725.95  725.13  722.88  719.42  717.88
  715.83  715.40  713.19  709.61  708.24  707.26  707.15  707.15  707.18  707.10
  707.23  707.48  707.48  707.49  707.31  707.31  707.30  707.35  707.24  708.18
  708.44  716.57  723.63  727.27  735.64  744.17
  669.80  669.80  669.80  669.80  669.80  669.80  669.80  669.80  669.80  669.80
  669.80  669.80  669.80  669.80  669.80  669.80  669.80  669.80  669.80  669.80
  669.80  669.80  704.60  704.60  704.60  669.80  669.80  669.80  669.80  669.80
  669.80  669.80  669.80  669.80  669.80  669.80
  3895.4  3937.8  3981.3  4024.6  4079.3  4118.0  4143.0  4160.6  4206.6  4268.6
  4354.6  4380.3  4400.6  4424.3  4456.1  4536.8  4603.6  4656.5  4721.9  4773.5
  4895.2  4941.0  4941.0  4942.8  5059.0  5059.0  5066.9  5141.5  5227.9  5349.0
  5400.8  5443.6  5545.1  5609.2  5688.2  5770.7
  741.58  737.17  734.62  732.14  728.24  725.95  725.13  722.88  719.42  717.88
  715.83  715.40  713.19  709.61  708.24  707.26  707.15  707.15  707.18  707.10
  707.23  707.48  707.48  707.49  707.31  707.31  707.30  707.35  707.24  708.18
  708.44  716.57  723.63  727.27  735.64  744.17
  669.80  669.80  669.80  669.80  669.80  669.80  669.80  669.80  669.80  669.80
  669.80  669.80  669.80  669.80  669.80  669.80  669.80  669.80  669.80  669.80
  669.80  669.80  704.60  704.60  704.60  669.80  669.80  669.80  669.80  669.80
  669.80  669.80  669.80  669.80  669.80  669.80
Pier Skew, UpSta & Num, DnSta & Num=,4970.5,2,4970.5,2,0,0,0,0,0
     2.1     2.1
  696.03  704.60
     2.1     2.1
  696.21  704.60
Pier Skew, UpSta & Num, DnSta & Num=,5029.5,2,5029.5,2,0,0,0,0,0
     2.1     2.1
  696.78  704.60
     2.1     2.1
  693.63  704.60
BR Coef=1,1,0,1.25,0,,,0.8,0,2,0,
WSPro=,,,, 1 ,,,, 0 ,,,, 0 ,,,,-1 ,-1 ,-1 , 0 , 0 , 0 , 0 , 0
BC Design=,,0,,0,,,,,,