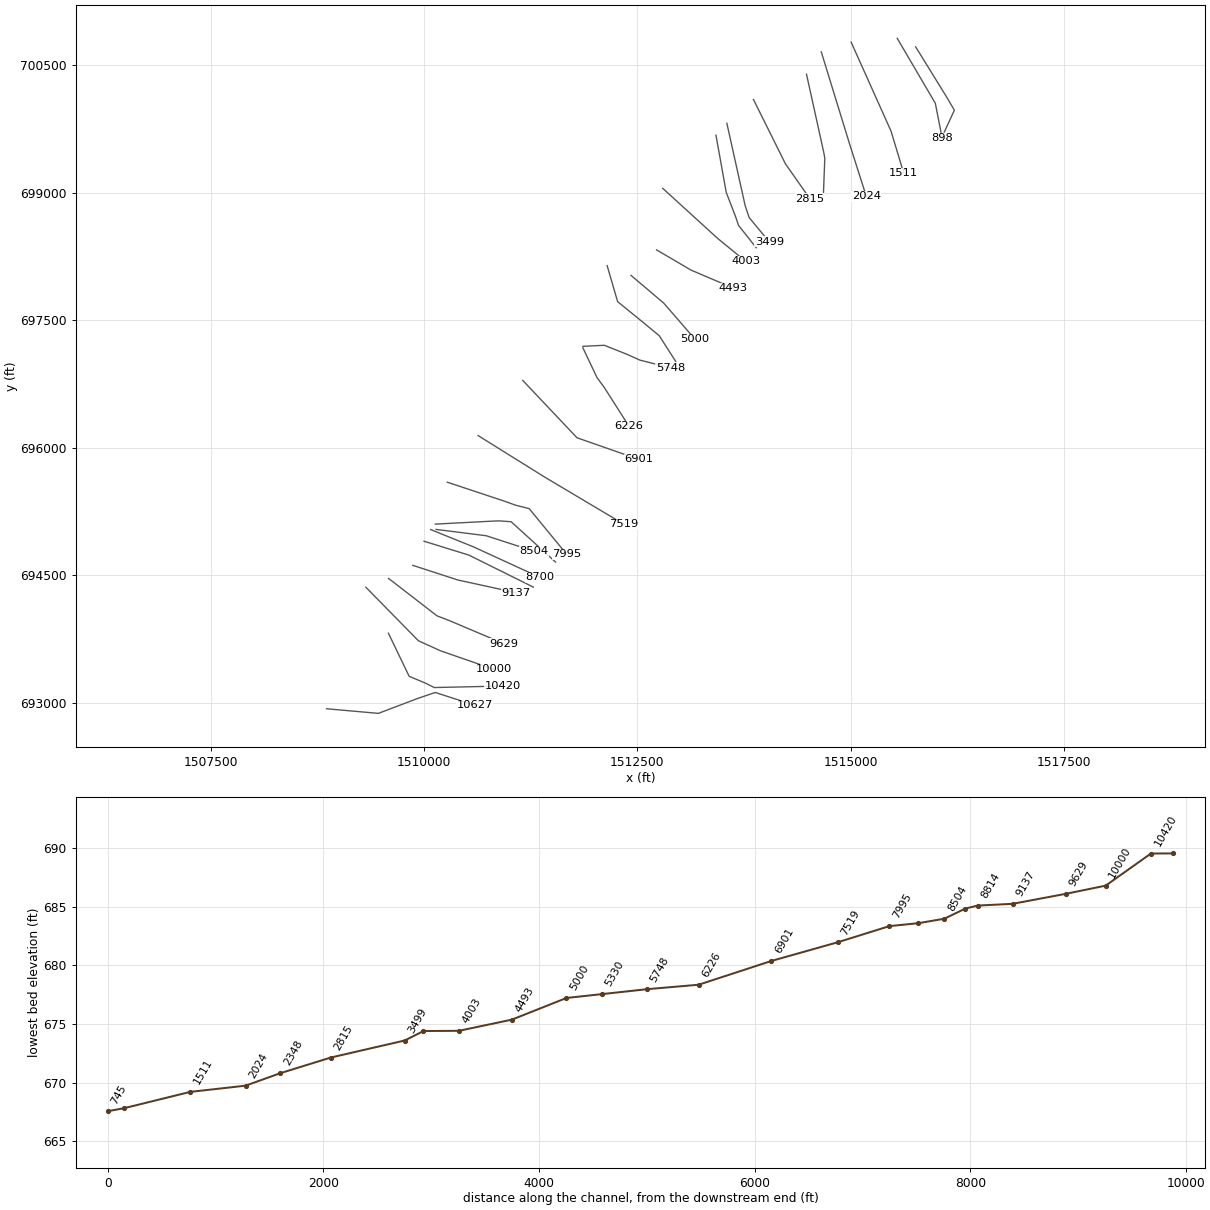
HEC-RAS study Kerr Creek.prj: .Kerr Creek Limited Detail Study

--- Kerr Creek.g01 (geometry) --- (continued)

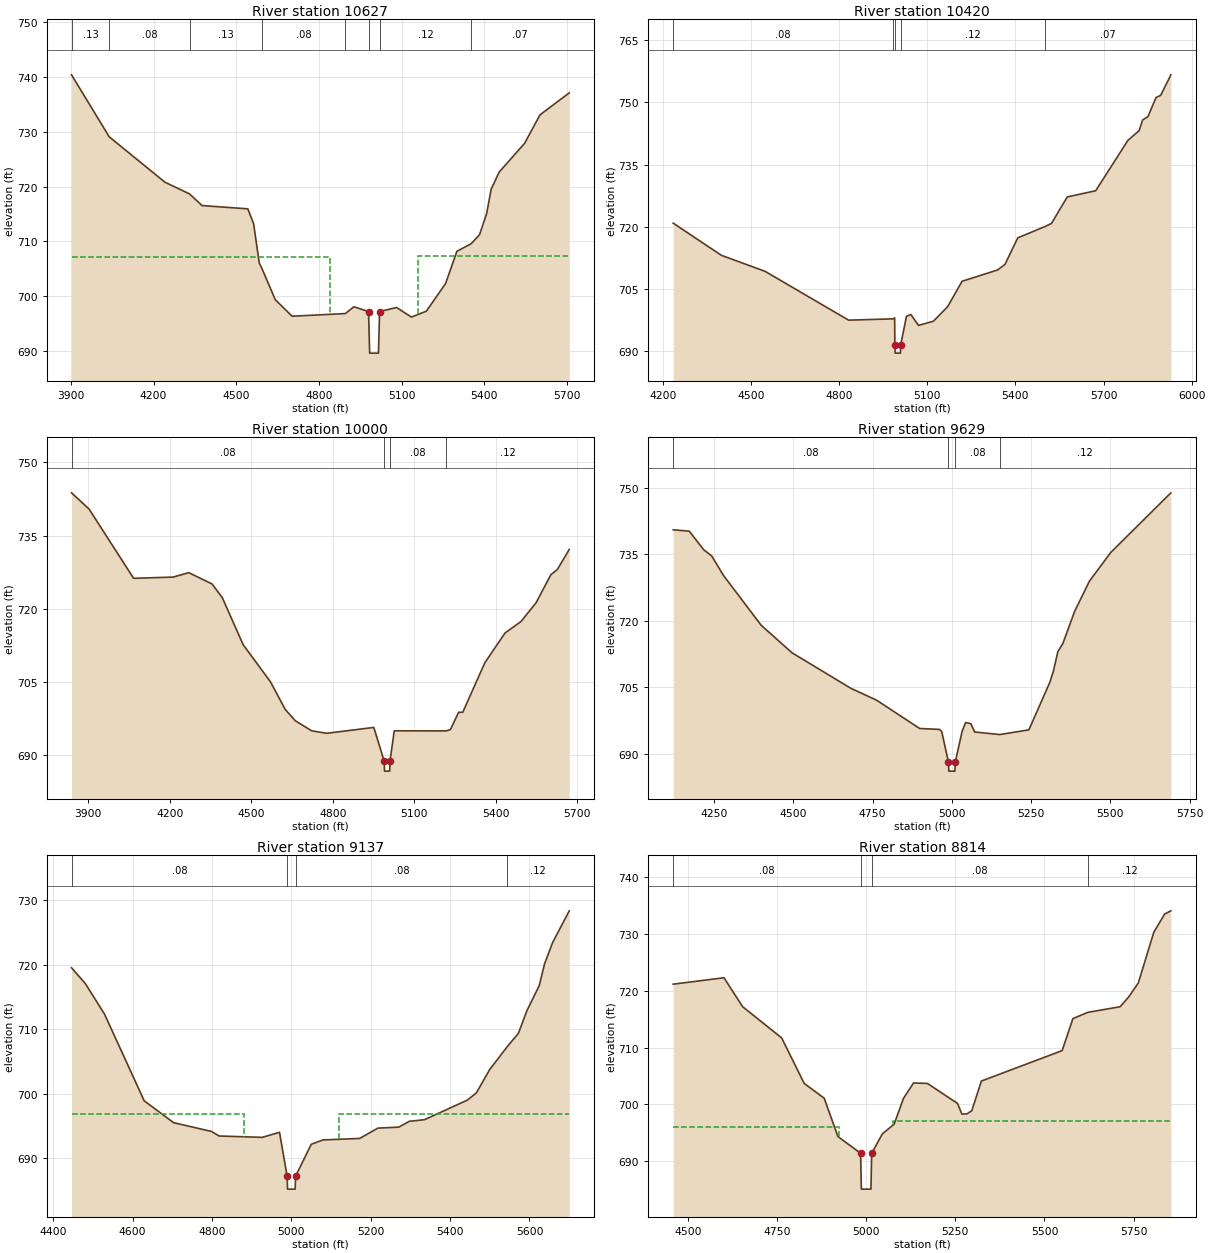
Type RM Length L Ch R = 1,10627,207,207,207
BEGIN DESCRIPTION:
Mooresville Road (Kerr) ds
END DESCRIPTION:
XS GIS Cut Line= 5
      1508852.77       692926.55      1509460.99       692872.20
      1509925.78       693049.21      1510128.67       693118.05
      1510588.26       692969.00
#Sta/Elev= 30
  3902.6  740.43  4039.2  729.10  4241.1  720.81  4330.6  718.66  4376.0  716.53
  4542.0  715.93  4563.1  713.20  4583.5  706.04  4592.9  705.06  4641.7  699.32
  4702.6  696.30  4895.9  696.78  4926.9  698.03  4980.0  697.15  4984.0  689.55
  5016.0  689.55  5020.0  697.15  5081.7  697.89  5135.4  696.14  5189.6  697.22
  5259.2  702.25  5300.6  708.17  5352.7  709.57  5382.7  711.21  5408.5  715.09
  5424.8  719.52  5453.8  722.64  5546.2  727.92  5601.9  733.11  5708.0  737.13
#Mann=8,-1,0
  3902.6    0.13       0  4039.2    0.08       0  4330.6    0.13       0
  4592.9    0.08       0  4895.9    0.12       0  4980.0   0.048       0
  5020.0    0.12       0  5352.7    0.07       0
#XS Ineff=2,0
    0.00 4839.50  707.16 5160.50    0.00  707.26
Permanent Ineff=
       F       F
Bank Sta=4980,5020
XS Rating Curve= 0
Exp/Cntr=0.5,0.3

Type RM Length L Ch R = 1,10420,420,420,420
BEGIN DESCRIPTION:
Kerr Creek 19.0
END DESCRIPTION:
XS GIS Cut Line= 5
      1509579.00       693815.24      1509822.26       693308.01
      1510008.59       693230.37      1510117.29       693176.02
      1510924.75       693194.14
#Sta/Elev= 30
  4235.7  720.88  4399.8  713.12  4548.4  709.26  4832.6  697.49  4982.9  697.80
  4989.3  698.02  4990.0  691.54  4991.0  689.54  5009.0  689.54  5010.0  691.54
  5029.5  698.41  5044.7  698.84  5070.3  696.23  5121.2  697.23  5169.6  700.74
  5218.7  706.86  5339.7  709.59  5364.9  710.94  5408.2  717.33  5502.0  720.10
  5523.0  720.81  5576.5  727.19  5673.5  728.70  5782.9  740.82  5821.6  743.21
  5832.9  745.74  5851.3  746.56  5878.7  751.16  5894.7  751.71  5929.3  756.64
#Mann=5,-1,0
  4235.7    0.08       0  4982.9    0.12       0  4990.0   0.048       0
  5010.0    0.12       0  5502.0    0.07       0
Bank Sta=4990,5010
XS Rating Curve= 0
Exp/Cntr=0.3,0.1

Type RM Length L Ch R = 1,10000,371,371,371
BEGIN DESCRIPTION:
Kerr Creek 18.0
END DESCRIPTION:
XS GIS Cut Line= 4
      1509313.65       694356.65      1509930.95       693726.22
      1510192.41       693607.52      1510818.57       693389.80
#Sta/Elev= 30
  3838.2  743.74  3902.8  740.42  4066.7  726.25  4212.5  726.50  4269.8  727.41
  4355.4  725.10  4393.6  722.25  4469.9  712.68  4570.6  705.07  4624.9  699.43
  4661.7  697.12  4722.1  695.05  4777.7  694.54  4951.2  695.74  4989.4  688.80
  4990.4  686.80  5009.6  686.80  5010.6  688.80  5026.3  695.05  5217.9  695.03
  5233.0  695.29  5263.3  698.83  5278.6  698.85  5359.8  708.97  5434.2  715.06
  5492.9  717.41  5548.4  721.24  5603.2  727.01  5626.6  728.03  5670.6  732.15
#Mann=4,-1,0
  3838.2    0.08       0  4989.4   0.048       0  5010.6    0.08       0
  5217.9    0.12       0
Bank Sta=4989.4,5010.6
XS Rating Curve= 0
Exp/Cntr=0.3,0.1

Type RM Length L Ch R = 1,9629,492,492,492
BEGIN DESCRIPTION:
Kerr Creek 17.0
END DESCRIPTION:
XS GIS Cut Line= 4
      1509580.97       694459.80      1510148.34       694019.95
      1510295.85       693963.01      1510935.07       693691.28
#Sta/Elev= 30
  4120.6  740.55  4171.4  740.24  4217.0  736.04  4242.1  734.66  4279.7  730.21
  4398.0  719.03  4495.4  712.81  4680.4  704.82  4763.1  702.08  4898.4  695.72
  4961.0  695.51  4967.9  695.07  4989.4  688.10  4990.4  686.10  5009.6  686.10
  5010.6  688.10  5032.4  695.07  5043.3  697.05  5060.0  696.82  5072.0  694.93
  5151.1  694.35  5243.1  695.41  5308.8  706.07  5320.2  708.58  5334.4  713.03
  5350.6  714.94  5387.4  722.14  5434.1  728.96  5502.0  735.48  5691.2  748.89
#Mann=4,-1,0
  4120.6    0.08       0  4989.4   0.048       0  5010.6    0.08       0
  5151.1    0.12       0
Bank Sta=4989.4,5010.6
XS Rating Curve= 0
Exp/Cntr=0.3,0.1

Type RM Length L Ch R = 1,9137,323,323,323
BEGIN DESCRIPTION:
Kerr Creek 16.0
END DESCRIPTION:
XS GIS Cut Line= 3
      1509865.78       694613.46      1510393.59       694441.39
      1511076.41       694292.08
#Sta/Elev= 30
  4446.1  719.54  4480.7  717.10  4529.1  712.37  4629.2  698.93  4703.4  695.54
  4798.4  694.19  4817.9  693.48  4926.7  693.27  4970.1  694.05  4989.4  687.25
  4990.4  685.25  5009.6  685.25  5010.6  687.25  5050.2  692.20  5079.7  692.87
  5172.1  693.10  5218.1  694.70  5270.6  694.85  5296.9  695.75  5335.6  696.01
  5442.8  699.02  5466.0  700.14  5499.8  703.77  5543.5  707.28  5572.2  709.39
  5593.2  712.84  5624.7  716.79  5637.9  720.13  5658.0  723.40  5700.2  728.36
#Mann=4,-1,0
  4446.1    0.08       0  4989.4   0.048       0  5010.6    0.08       0
  5543.5    0.12       0
#XS Ineff=2,0
    0.00 4880.70  696.94 5120.00    0.00  696.94
Permanent Ineff=
       F       F
Bank Sta=4989.4,5010.6
XS Rating Curve= 0
Exp/Cntr=0.5,0.3

Type RM Length L Ch R = 1,8814,114,114,114
BEGIN DESCRIPTION:
Unnamed Bridge (Kerr) us
END DESCRIPTION:
XS GIS Cut Line= 3
      1509996.80       694897.40      1510521.88       694734.70
      1511279.19       694357.62
#Sta/Elev= 30
  4458.9  721.15  4601.4  722.28  4653.4  717.20  4763.1  711.70  4826.3  703.69
  4882.3  701.10  4920.9  694.35  4984.5  691.40  4986.5  685.10  5013.5  685.10
  5015.5  691.40  5045.5  694.82  5078.6  696.53  5104.6  701.05  5132.8  703.77
  5171.9  703.69  5256.4  700.17  5268.5  698.30  5282.7  698.34  5296.3  698.89
  5323.2  704.11  5549.6  709.46  5579.9  715.10  5622.2  716.20  5712.1  717.18
  5735.6  718.84  5763.2  721.35  5806.7  730.28  5837.1  733.49  5854.6  734.05
#Mann=4,-1,0
  4458.9    0.08       0  4984.5   0.048       0  5015.5    0.08       0
  5622.2    0.12       0
#XS Ineff=2,0
    0.00 4923.50  695.99 5076.50    0.00  697.14
Permanent Ineff=
       F       F
Bank Sta=4984.5,5015.5
XS Rating Curve= 0
Exp/Cntr=0.5,0.3

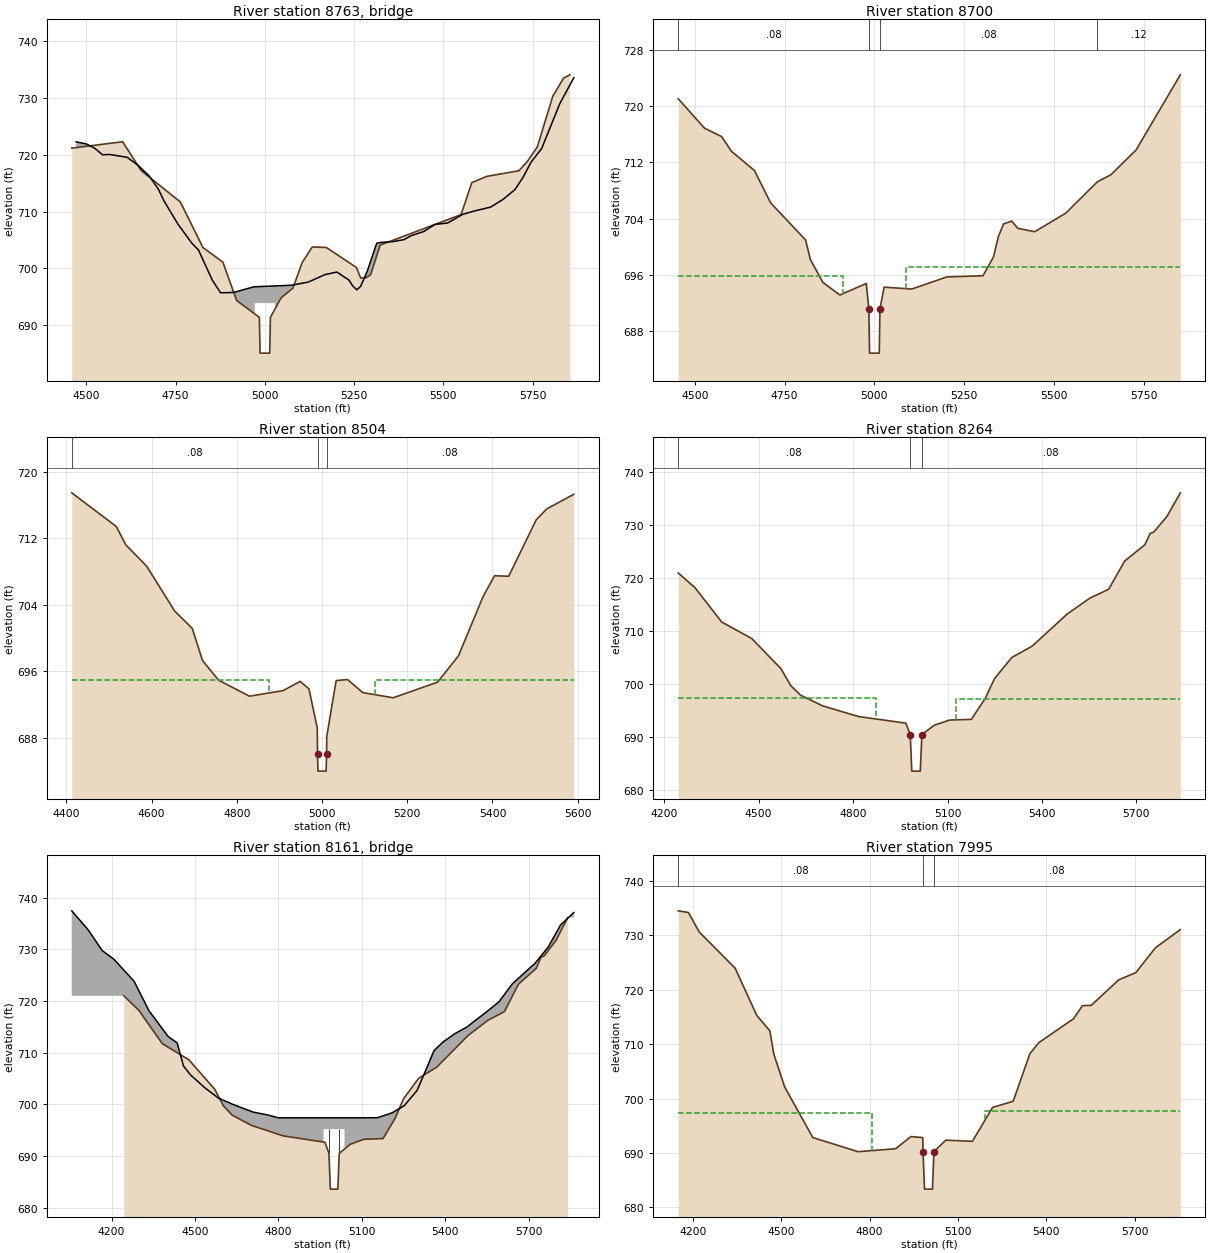
Type RM Length L Ch R =3,8763,,,
BEGIN DESCRIPTION:
Unnamed Bridge TOR (Kerr)
Structure ID: LDS_KC_02A
Approximate Survey Structure
END DESCRIPTION:
Bridge Culvert--1,0,-1,-1,0
Deck Dist Width WeirC Skew NumUp NumDn MinLoCord MaxHiCord MaxSubmerge Is_Ogee
48,6,3,,51,51,,,,0,1,1,,,
  4471.1  4499.2  4523.2  4545.0  4565.5  4607.5  4613.7  4644.8  4676.5  4702.0
  4718.4  4756.6  4794.7  4814.3  4836.5  4852.8  4875.8  4912.4  4968.7  4971.5
  4971.5  5028.5  5028.5  5074.3  5121.2  5167.9  5201.6  5235.6  5245.9  5257.5
  5268.4  5287.0  5313.4  5321.6  5359.6  5389.6  5409.3  5444.9  5476.7  5512.2
  5554.5  5587.8  5632.5  5667.8  5700.5  5723.1  5746.1  5775.6  5801.9  5826.3
  5865.7
  722.26  721.91  721.14  719.99  720.04  719.61  719.56  718.13  716.22  713.88
  711.75  707.77  704.49  703.20  700.15  697.92  695.71  695.77  696.76  696.77
  696.77  696.92  696.92  697.04  697.59  698.90  699.36  697.95  696.94  696.23
  696.85  699.55  704.43  704.55  704.73  705.06  705.75  706.48  707.74  707.99
  709.52  710.11  710.78  712.16  713.86  715.99  718.71  721.09  725.18  728.97
  733.56
  665.10  665.10  665.10  665.10  665.10  665.10  665.10  665.10  665.10  665.10
  665.10  665.10  665.10  665.10  665.10  665.10  665.10  665.10  665.10  665.10
  693.90  693.90  665.10  665.10  665.10  665.10  665.10  665.10  665.10  665.10
  665.10  665.10  665.10  665.10  665.10  665.10  665.10  665.10  665.10  665.10
  665.10  665.10  665.10  665.10  665.10  665.10  665.10  665.10  665.10  665.10
  665.10
  4471.1  4499.2  4523.2  4545.0  4565.5  4607.5  4613.7  4644.8  4676.5  4702.0
  4718.4  4756.6  4794.7  4814.3  4836.5  4852.8  4875.8  4912.4  4968.7  4971.5
  4971.5  5028.5  5028.5  5074.3  5121.2  5167.9  5201.6  5235.6  5245.9  5257.5
  5268.4  5287.0  5313.4  5321.6  5359.6  5389.6  5409.3  5444.9  5476.7  5512.2
  5554.5  5587.8  5632.5  5667.8  5700.5  5723.1  5746.1  5775.6  5801.9  5826.3
  5865.7
  722.26  721.91  721.14  719.99  720.04  719.61  719.56  718.13  716.22  713.88
  711.75  707.77  704.49  703.20  700.15  697.92  695.71  695.77  696.76  696.77
  696.77  696.92  696.92  697.04  697.59  698.90  699.36  697.95  696.94  696.23
  696.85  699.55  704.43  704.55  704.73  705.06  705.75  706.48  707.74  707.99
  709.52  710.11  710.78  712.16  713.86  715.99  718.71  721.09  725.18  728.97
  733.56
  665.10  665.10  665.10  665.10  665.10  665.10  665.10  665.10  665.10  665.10
  665.10  665.10  665.10  665.10  665.10  665.10  665.10  665.10  665.10  665.10
  693.90  693.90  665.10  665.10  665.10  665.10  665.10  665.10  665.10  665.10
  665.10  665.10  665.10  665.10  665.10  665.10  665.10  665.10  665.10  665.10
  665.10  665.10  665.10  665.10  665.10  665.10  665.10  665.10  665.10  665.10
  665.10
BR Coef=1,1,0,1.25,0,,,0.8,0,2,0,
WSPro=,,,, 1 ,,,, 0 ,,,, 0 ,,,,-1 ,-1 ,-1 , 0 , 0 , 0 , 0 , 0
BC Design=,,0,,0,,,,,,

Type RM Length L Ch R = 1,8700,196,196,196
BEGIN DESCRIPTION:
Unnamed Bridge (Kerr) ds
END DESCRIPTION:
XS GIS Cut Line= 3
      1510074.85       695034.67      1510577.28       694830.92
      1511354.04       694473.08
#Sta/Elev= 30
  4454.0  721.06  4526.8  716.88  4575.1  715.66  4601.9  713.59  4666.1  710.84
  4710.9  706.25  4808.6  700.95  4821.6  698.18  4856.7  694.91  4903.9  693.12
  4977.4  694.77  4984.5  691.15  4986.5  684.85  5013.5  684.85  5015.5  691.15
  5027.0  694.24  5103.8  693.97  5202.0  695.70  5302.2  695.86  5331.4  698.54
  5345.0  701.44  5359.5  703.25  5382.1  703.64  5399.2  702.61  5446.2  702.13
  5532.8  704.78  5620.6  709.24  5658.0  710.23  5728.3  713.76  5851.4  724.46
#Mann=4,-1,0
  4454.0    0.08       0  4984.5   0.048       0  5015.5    0.08       0
  5620.6    0.12       0
#XS Ineff=2,0
    0.00 4911.50  695.77 5088.50    0.00  697.16
Permanent Ineff=
       F       F
Bank Sta=4984.5,5015.5
XS Rating Curve= 0
Exp/Cntr=0.5,0.3

Type RM Length L Ch R = 1,8504,240,240,240
BEGIN DESCRIPTION:
Kerr Creek 15.0
END DESCRIPTION:
XS GIS Cut Line= 3
      1510138.42       695036.57      1510725.97       694962.12
      1511283.56       694780.71
#Sta/Elev= 30
  4412.5  717.44  4517.1  713.39  4539.2  711.20  4588.5  708.61  4654.2  703.22
  4695.4  701.14  4719.4  697.28  4757.3  694.91  4829.8  692.99  4908.7  693.66
  4948.6  694.77  4969.3  693.87  4988.8  689.16  4989.4  685.98  4990.4  683.98
  5009.6  683.98  5010.6  685.98  5011.1  688.15  5033.1  694.86  5059.8  695.00
  5095.6  693.42  5167.1  692.80  5271.3  694.68  5320.3  697.85  5377.9  704.95
  5405.0  707.47  5438.2  707.41  5502.8  714.20  5527.4  715.50  5591.1  717.27
#Mann=3,-1,0
  4412.5    0.08       0  4989.4   0.048       0  5010.6    0.08       0
#XS Ineff=2,0
    0.00 4875.00  694.90 5125.00    0.00  694.90
Permanent Ineff=
       F       F
Bank Sta=4989.4,5010.6
XS Rating Curve= 0
Exp/Cntr=0.5,0.3

Type RM Length L Ch R = 1,8264,269,269,269
BEGIN DESCRIPTION:
Sloan Road (Kerr) us
END DESCRIPTION:
XS GIS Cut Line= 5
      1510129.09       695098.96      1510787.46       695133.29
      1510874.67       695137.06      1511018.35       695127.05
      1511539.44       694652.77
#Sta/Elev= 30
  4244.4  721.00  4297.9  718.21  4382.6  711.74  4478.2  708.62  4570.7  702.94
  4602.3  699.71  4633.3  697.93  4703.2  695.92  4816.6  693.91  4967.4  692.66
  4981.5  690.50  4986.5  683.60  5013.5  683.60  5018.5  690.50  5057.8  692.26
  5106.7  693.24  5175.8  693.37  5219.9  697.34  5249.5  701.07  5304.1  705.05
  5369.1  707.20  5480.9  713.29  5552.8  716.27  5611.9  717.92  5663.0  723.27
  5726.9  726.33  5743.9  728.48  5755.2  728.72  5797.8  731.73  5839.6  736.13
#Mann=3,-1,0
  4244.4    0.08       0  4981.5   0.048       0  5018.5    0.08       0
#XS Ineff=2,0
    0.00 4871.50  697.40 5128.50    0.00  697.26
Permanent Ineff=
       F       F
Bank Sta=4981.5,5018.5
XS Rating Curve= 0
Exp/Cntr=0.5,0.3

Type RM Length L Ch R =3,8161,,,
BEGIN DESCRIPTION:
Sloan Road TOR (Kerr)
Structure ID: LDS_KC_02
Approximate Survey Structure
END DESCRIPTION:
Bridge Culvert--1,0,-1,-1,0
Deck Dist Width WeirC Skew NumUp NumDn MinLoCord MaxHiCord MaxSubmerge Is_Ogee
91,24,3,,37,37,,,,0,1,1,,,
  4057.2  4117.2  4166.6  4209.2  4281.3  4334.6  4403.3  4436.1  4458.6  4483.3
  4535.2  4584.1  4638.3  4709.2  4763.8  4799.4  4962.5  4962.5  5037.5  5037.5
  5106.8  5156.7  5208.7  5252.3  5298.2  5337.7  5359.0  5391.8  5433.6  5475.5
  5547.5  5592.1  5640.5  5721.9  5769.1  5813.6  5861.7
  737.44  733.69  729.75  728.05  723.80  718.12  713.14  711.89  707.44  705.73
  703.22  701.21  699.95  698.50  697.92  697.40  697.40  697.40  697.40  697.40
  697.40  697.42  698.37  699.75  702.68  707.64  710.39  712.07  713.66  714.90
  717.88  719.81  723.30  727.28  730.39  734.67  737.13
  663.60  663.60  663.60  663.60  663.60  663.60  663.60  663.60  663.60  663.60
  663.60  663.60  663.60  663.60  663.60  663.60  663.60  695.20  695.20  663.60
  663.60  663.60  663.60  663.60  663.60  663.60  663.60  663.60  663.60  663.60
  663.60  663.60  663.60  663.60  663.60  663.60  663.60
  4057.2  4117.2  4166.6  4209.2  4281.3  4334.6  4403.3  4436.1  4458.6  4483.3
  4535.2  4584.1  4638.3  4709.2  4763.8  4799.4  4962.5  4962.5  5037.5  5037.5
  5106.8  5156.7  5208.7  5252.3  5298.2  5337.7  5359.0  5391.8  5433.6  5475.5
  5547.5  5592.1  5640.5  5721.9  5769.1  5813.6  5861.7
  737.44  733.69  729.75  728.05  723.80  718.12  713.14  711.89  707.44  705.73
  703.22  701.21  699.95  698.50  697.92  697.40  697.40  697.40  697.40  697.40
  697.40  697.42  698.37  699.75  702.68  707.64  710.39  712.07  713.66  714.90
  717.88  719.81  723.30  727.28  730.39  734.67  737.13
  663.60  663.60  663.60  663.60  663.60  663.60  663.60  663.60  663.60  663.60
  663.60  663.60  663.60  663.60  663.60  663.60  663.60  695.20  695.20  663.60
  663.60  663.60  663.60  663.60  663.60  663.60  663.60  663.60  663.60  663.60
  663.60  663.60  663.60  663.60  663.60  663.60  663.60
Pier Skew, UpSta & Num, DnSta & Num=,4981.3,2,4981.3,2,0,0,0,0,0
       1       1
  691.23  695.20
       1       1
  691.56  695.20
Pier Skew, UpSta & Num, DnSta & Num=,5018.8,2,5018.8,2,0,0,0,0,0
       1       1
  685.76  695.20
       1       1
  690.49  695.20
BR Coef=1,1,0,1.25,0,,,0.8,0,2,0,
WSPro=,,,, 1 ,,,, 0 ,,,, 0 ,,,,-1 ,-1 ,-1 , 0 , 0 , 0 , 0 , 0
BC Design=,,0,,0,,,,,,

Type RM Length L Ch R = 1,7995,476,476,476
BEGIN DESCRIPTION:
Sloan Road (Kerr) ds
END DESCRIPTION:
XS GIS Cut Line= 5
      1510269.52       695591.95      1510923.85       695374.08
      1511072.93       695320.75      1511230.05       695281.29
      1511670.48       694743.25
#Sta/Elev= 30
  4150.0  734.49  4184.6  734.18  4221.3  730.60  4343.3  723.95  4416.8  715.27
  4461.3  712.43  4474.4  708.20  4511.6  702.11  4607.1  692.83  4760.7  690.23
  4888.1  690.77  4940.5  693.01  4980.5  692.82  4981.5  690.25  4986.5  683.35
  5013.5  683.35  5018.5  690.25  5058.8  692.35  5149.0  692.13  5217.8  698.37
  5287.6  699.49  5344.5  708.25  5374.8  710.27  5492.8  714.67  5523.0  717.07
  5552.8  717.12  5646.2  721.81  5704.1  723.13  5770.9  727.71  5855.3  731.04
#Mann=3,-1,0
  4150.0    0.08       0  4981.5   0.048       0  5018.5    0.08       0
#XS Ineff=2,0
    0.00 4808.50  697.40 5191.50    0.00  697.68
Permanent Ineff=
       F       F
Bank Sta=4981.5,5018.5
XS Rating Curve= 0
Exp/Cntr=0.5,0.3

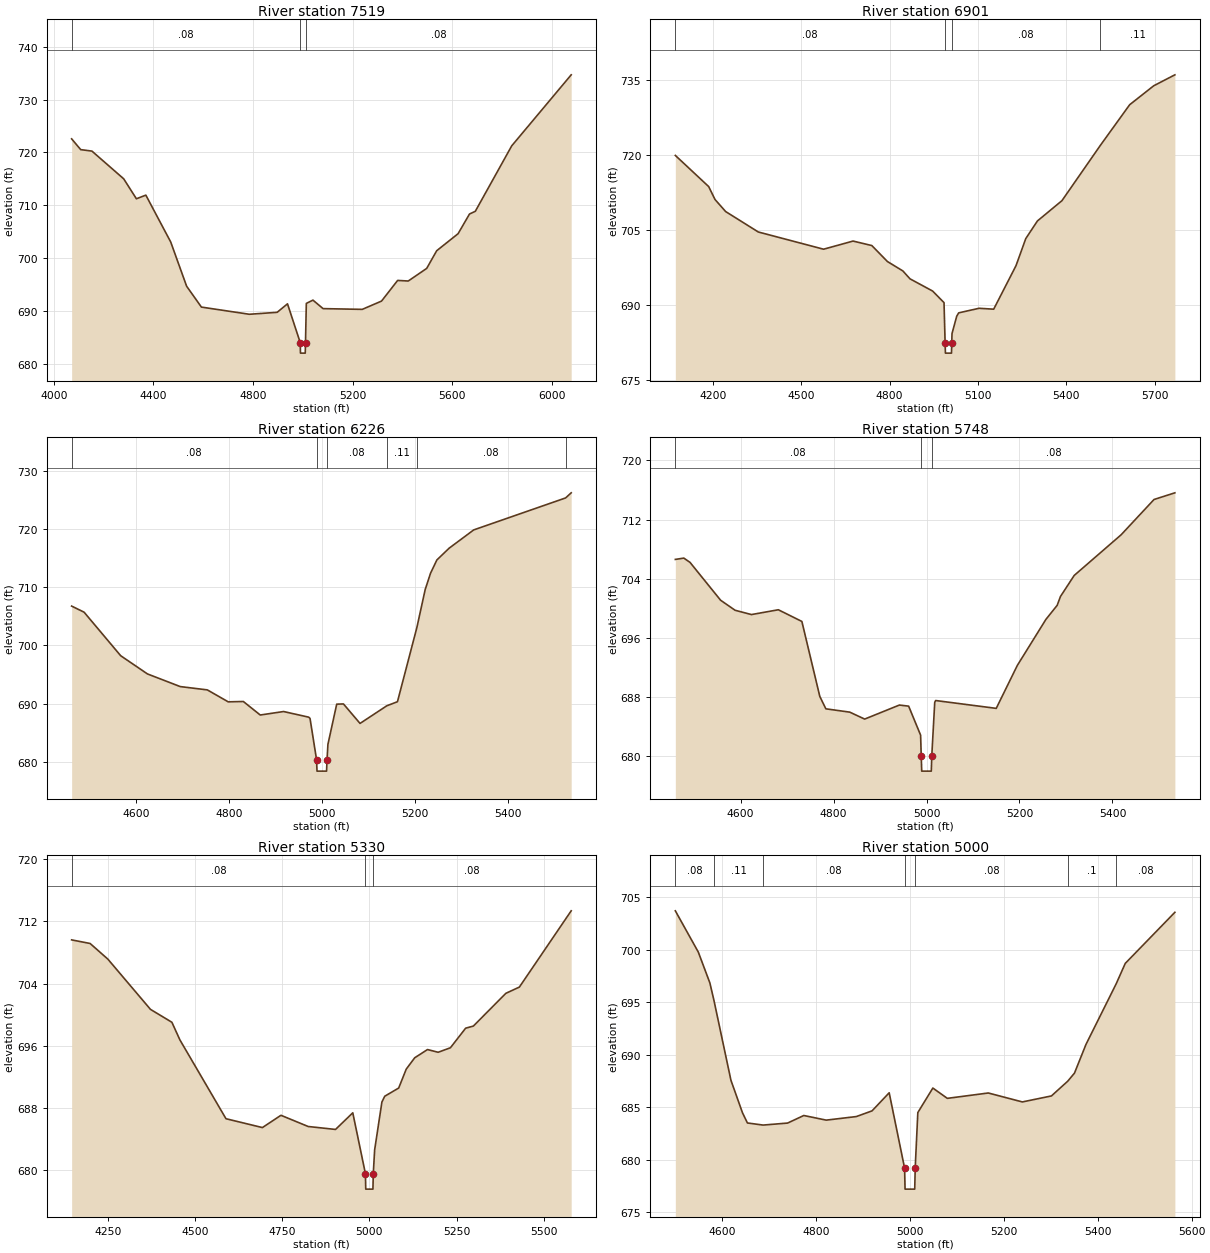
Type RM Length L Ch R = 1,7519,618,618,618
BEGIN DESCRIPTION:
Kerr Creek 14.0
END DESCRIPTION:
XS GIS Cut Line= 3
      1510631.29       696140.32      1511419.89       695647.30
      1512343.64       695096.36
#Sta/Elev= 30
  4071.7  722.57  4108.1  720.53  4153.2  720.25  4280.7  715.00  4331.7  711.22
  4369.6  711.91  4469.4  703.04  4533.3  694.66  4592.7  690.70  4785.1  689.34
  4896.8  689.71  4938.3  691.32  4989.4  683.98  4990.4  681.98  5009.6  681.98
  5010.6  683.98  5013.9  691.40  5040.5  692.02  5081.2  690.41  5238.6  690.27
  5315.9  691.84  5380.5  695.75  5423.1  695.64  5497.2  698.03  5537.2  701.37
  5623.3  704.61  5669.0  708.33  5692.4  708.85  5838.6  721.25  6077.3  734.70
#Mann=3,-1,0
  4071.7    0.08       0  4989.4   0.048       0  5010.6    0.08       0
Bank Sta=4989.4,5010.6
XS Rating Curve= 0
Exp/Cntr=0.3,0.1

Type RM Length L Ch R = 1,6901,675,675,675
BEGIN DESCRIPTION:
Kerr Creek 13.0
END DESCRIPTION:
XS GIS Cut Line= 3
      1511154.58       696789.58      1511791.13       696114.84
      1512516.83       695860.21
#Sta/Elev= 30
  4072.4  719.97  4185.7  713.73  4207.2  711.14  4243.3  708.73  4354.1  704.64
  4575.9  701.19  4676.1  702.82  4739.8  701.92  4792.8  698.72  4845.2  696.84
  4869.4  695.26  4946.3  692.81  4985.0  690.49  4988.7  682.38  4989.7  680.38
  5010.3  680.38  5011.3  682.38  5012.1  684.29  5028.1  687.77  5034.8  688.44
  5103.9  689.36  5153.7  689.18  5229.4  697.88  5262.6  703.31  5302.1  706.84
  5385.5  710.91  5516.3  722.01  5615.5  730.12  5697.3  733.92  5769.1  736.11
#Mann=4,-1,0
  4072.4    0.08       0  4988.7   0.048       0  5011.3    0.08       0
  5516.3    0.11       0
Bank Sta=4988.7,5011.3
XS Rating Curve= 0
Exp/Cntr=0.3,0.1

Type RM Length L Ch R = 1,6226,478,478,478
BEGIN DESCRIPTION:
Kerr Creek 12.0
END DESCRIPTION:
XS GIS Cut Line= 4
      1511860.11       697173.58      1512025.11       696824.17
      1512112.45       696704.48      1512402.21       696248.55
#Sta/Elev= 30
  4461.8  706.79  4488.6  705.74  4567.3  698.24  4624.9  695.10  4695.4  692.92
  4753.7  692.35  4798.7  690.29  4831.2  690.35  4867.6  688.02  4917.8  688.62
  4971.8  687.65  4974.7  687.44  4988.7  680.35  4989.7  678.35  5010.3  678.35
  5011.3  680.35  5013.2  682.96  5032.1  689.89  5046.6  689.93  5082.3  686.57
  5139.9  689.61  5162.8  690.31  5204.5  703.07  5222.5  709.65  5234.0  712.46
  5247.6  714.74  5274.0  716.77  5326.9  719.92  5524.6  725.43  5536.6  726.31
#Mann=6,-1,0
  4461.8    0.08       0  4988.7   0.048       0  5011.3    0.08       0
  5139.9    0.11       0  5204.5    0.08       0  5524.6    0.11       0
Bank Sta=4988.7,5011.3
XS Rating Curve= 0
Exp/Cntr=0.3,0.1

Type RM Length L Ch R = 1,5748,418,418,418
BEGIN DESCRIPTION:
Kerr Creek 11.0
END DESCRIPTION:
XS GIS Cut Line= 5
      1511861.11       697190.62      1512112.45       697202.65
      1512380.95       697095.26      1512529.76       697027.97
      1512888.83       696936.75
#Sta/Elev= 30
  4459.7  706.61  4477.9  706.79  4491.3  706.21  4557.1  701.09  4588.3  699.73
  4623.5  699.15  4681.3  699.80  4731.9  698.22  4770.5  688.07  4783.5  686.40
  4834.9  685.95  4867.0  685.01  4941.7  686.91  4961.6  686.76  4987.3  682.84
  4988.7  679.97  4989.7  677.97  5010.3  677.97  5011.3  679.97  5017.7  687.27
  5019.7  687.52  5150.0  686.46  5195.3  692.26  5256.9  698.50  5281.1  700.40
  5288.2  701.60  5317.7  704.44  5418.6  709.94  5489.5  714.72  5534.3  715.62
#Mann=3,-1,0
  4459.7    0.08       0  4988.7   0.048       0  5011.3    0.08       0
Bank Sta=4988.7,5011.3
XS Rating Curve= 0
Exp/Cntr=0.3,0.1

Type RM Length L Ch R = 1,5330,330,330,330
BEGIN DESCRIPTION:
Kerr Creek 10.0
END DESCRIPTION:
XS GIS Cut Line= 5
      1512144.79       698140.17      1512267.73       697716.36
      1512584.75       697457.57      1512756.20       697315.23
      1512949.66       697012.40
#Sta/Elev= 30
  4146.2  709.62  4199.1  709.16  4250.0  707.15  4372.3  700.68  4433.7  699.02
  4456.6  696.76  4588.8  686.61  4693.3  685.47  4746.5  687.05  4824.5  685.61
  4903.0  685.23  4952.5  687.37  4988.7  679.55  4989.7  677.55  5010.3  677.55
  5011.3  679.55  5015.2  682.60  5036.0  688.75  5044.1  689.50  5084.2  690.56
  5105.8  692.99  5130.1  694.45  5166.8  695.51  5197.4  695.16  5232.5  695.74
  5276.2  698.26  5298.3  698.53  5391.4  702.74  5430.3  703.55  5578.9  713.36
#Mann=3,-1,0
  4146.2    0.08       0  4988.7   0.048       0  5011.3    0.08       0
Bank Sta=4988.7,5011.3
XS Rating Curve= 0
Exp/Cntr=0.3,0.1

Type RM Length L Ch R = 1,5000,507,507,507
BEGIN DESCRIPTION:
Kerr Creek 9.0
END DESCRIPTION:
XS GIS Cut Line= 3
      1512424.99       698025.01      1512807.73       697699.90
      1513174.99       697275.01
#Sta/Elev= 30
  4500.5  703.68  4549.4  699.76  4574.1  696.82  4582.8  695.15  4618.9  687.57
  4643.5  684.48  4654.0  683.51  4687.4  683.31  4739.5  683.50  4774.1  684.22
  4821.8  683.78  4886.0  684.12  4919.4  684.66  4955.9  686.38  4988.7  679.22
  4989.7  677.22  5010.3  677.22  5011.3  679.22  5016.9  684.50  5048.9  686.83
  5079.7  685.85  5167.0  686.36  5239.5  685.51  5301.4  686.08  5336.1  687.48
  5350.5  688.25  5375.1  690.99  5439.5  696.76  5458.6  698.68  5564.3  703.54
#Mann=7,-1,0
  4500.5    0.08       0  4582.8    0.11       0  4687.4    0.08       0
  4988.7   0.048       0  5011.3    0.08       0  5336.1     0.1       0
  5439.5    0.08       0
Bank Sta=4988.7,5011.3
XS Rating Curve= 0
Exp/Cntr=0.3,0.1

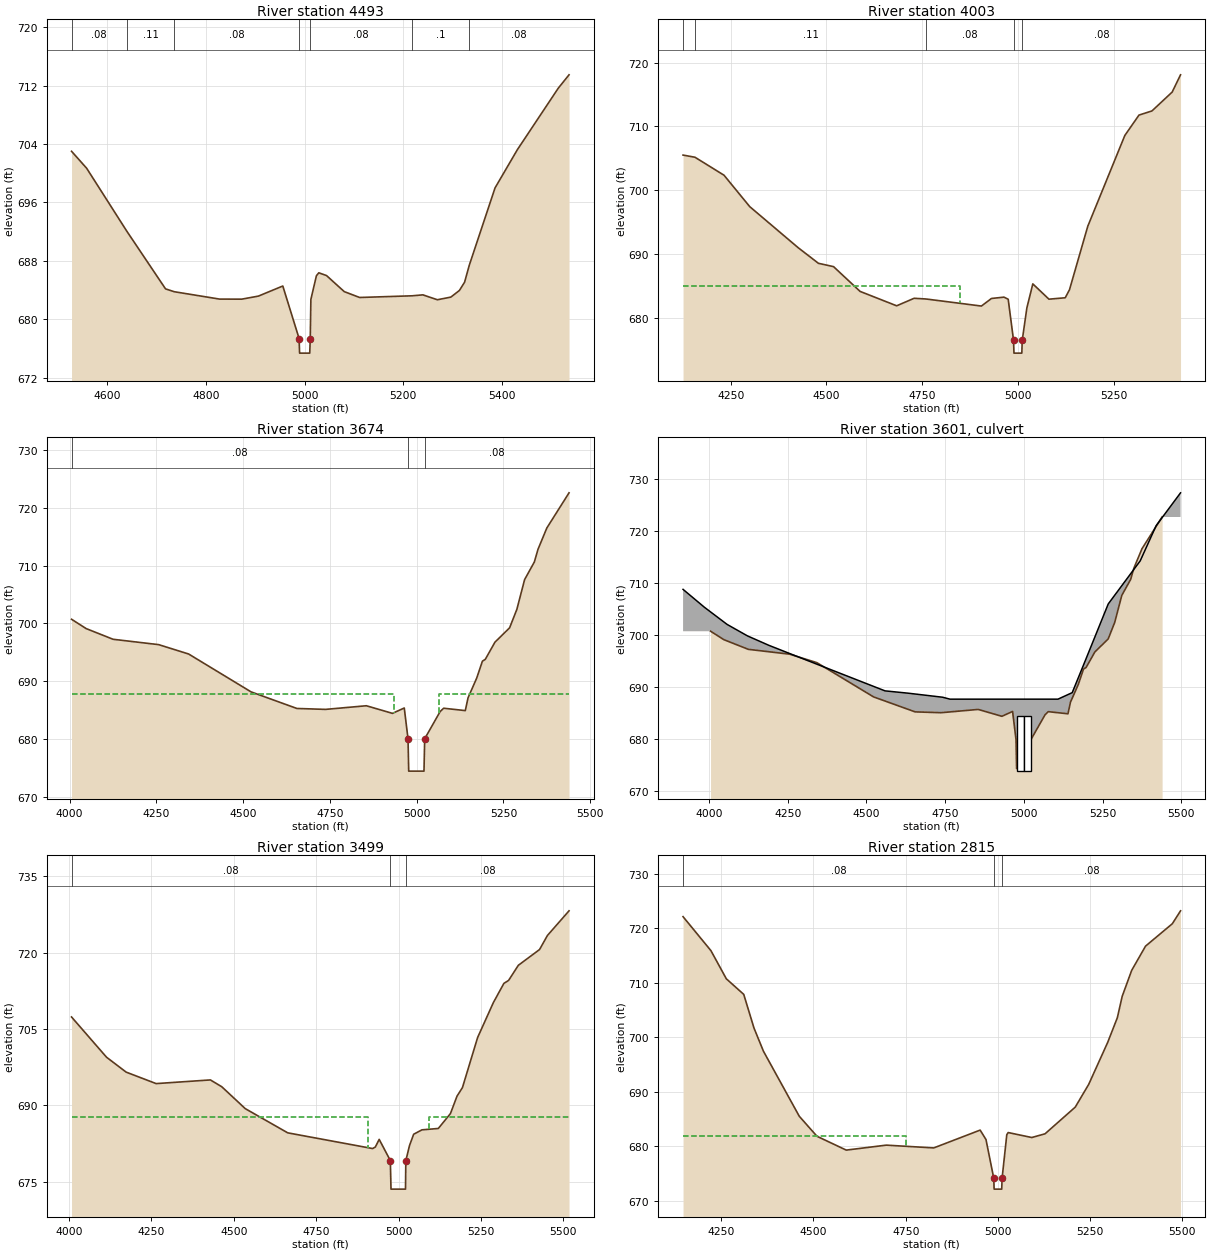
Type RM Length L Ch R = 1,4493,490,490,490
BEGIN DESCRIPTION:
Kerr Creek 8.0
END DESCRIPTION:
XS GIS Cut Line= 3
      1512724.97       698325.02      1513128.45       698087.68
      1513625.01       697875.00
#Sta/Elev= 30
  4527.5  703.01  4558.1  700.69  4639.6  692.06  4718.0  684.17  4735.6  683.78
  4827.5  682.77  4872.5  682.76  4906.3  683.18  4955.7  684.56  4988.7  677.37
  4989.7  675.37  5010.3  675.37  5011.3  677.37  5012.6  682.73  5023.8  685.97
  5028.7  686.37  5044.3  685.99  5080.3  683.79  5111.4  682.99  5218.0  683.22
  5239.6  683.35  5268.9  682.68  5296.2  683.04  5313.6  683.95  5324.1  685.08
  5333.6  687.40  5385.8  697.99  5431.1  703.23  5514.1  711.66  5535.8  713.48
#Mann=7,-1,0
  4527.5    0.08       0  4639.6    0.11       0  4735.6    0.08       0
  4988.7   0.048       0  5011.3    0.08       0  5218.0     0.1       0
  5333.6    0.08       0
Bank Sta=4988.7,5011.3
XS Rating Curve= 0
Exp/Cntr=0.3,0.1

Type RM Length L Ch R = 1,4003,329,329,329
BEGIN DESCRIPTION:
Kerr Creek 7.0
END DESCRIPTION:
XS GIS Cut Line= 3
      1512796.90       699049.38      1513440.43       698460.88
      1513770.85       698190.01
#Sta/Elev= 30
  4125.5  705.51  4156.7  705.17  4232.5  702.35  4299.8  697.41  4426.2  690.97
  4479.1  688.52  4518.5  688.00  4587.9  684.11  4683.4  681.85  4729.0  683.03
  4759.9  682.92  4904.7  681.81  4931.0  683.00  4963.6  683.21  4974.7  682.88
  4988.7  676.42  4989.7  674.42  5010.3  674.42  5011.3  676.42  5023.5  681.53
  5039.0  685.29  5081.1  682.89  5123.6  683.11  5134.7  684.36  5182.5  694.33
  5279.3  708.59  5316.3  711.79  5350.1  712.44  5402.9  715.40  5424.8  718.11
#Mann=5,-1,0
  4125.5    0.08       0  4156.7    0.11       0  4759.9    0.08       0
  4988.7   0.048       0  5011.3    0.08       0
#XS Ineff=2,0
    0.00 4850.00  684.90               0
Permanent Ineff=
       F       F
Bank Sta=4988.7,5011.3
XS Rating Curve= 0
Exp/Cntr=0.5,0.3

Type RM Length L Ch R = 1,3674,175,175,175
BEGIN DESCRIPTION:
White Road (Kerr) us
END DESCRIPTION:
XS GIS Cut Line= 5
      1513421.48       699674.76      1513541.99       699001.91
      1513652.45       698714.04      1513685.93       698613.62
      1513893.93       698350.18
#Sta/Elev= 30
  4005.5  700.72  4047.7  699.10  4125.2  697.25  4256.6  696.32  4342.8  694.70
  4522.9  688.13  4654.8  685.26  4737.4  685.10  4855.0  685.73  4930.2  684.41
  4964.2  685.34  4975.0  680.00  4977.0  674.40  5021.0  674.40  5023.0  680.00
  5067.4  684.71  5077.6  685.30  5140.0  684.89  5148.0  687.12  5172.8  690.51
  5189.3  693.45  5197.7  693.78  5225.5  696.75  5267.7  699.24  5288.5  702.42
  5310.9  707.59  5339.0  710.65  5349.4  712.83  5374.9  716.53  5438.9  722.63
#Mann=3,-1,0
  4005.5    0.08       0  4975.0   0.048       0  5023.0    0.08       0
#XS Ineff=2,0
    0.00 4935.50  687.70 5064.50    0.00  687.70
Permanent Ineff=
       F       F
Bank Sta=4975,5023
XS Rating Curve= 0
Exp/Cntr=0.5,0.3

Type RM Length L Ch R =2,3601,,,
BEGIN DESCRIPTION:
White Road TOR (Kerr)
Structure ID: LDS_KC_01
Approximate Survey Structure
END DESCRIPTION:
Bridge Culvert--1,0,-1,-1,0
Deck Dist Width WeirC Skew NumUp NumDn MinLoCord MaxHiCord MaxSubmerge Is_Ogee
41.5,63,3,,17,17,,,,0,1,1,,,
  3918.0  3985.8  4057.9  4122.5  4190.5  4283.0  4559.2  4631.8  4742.1  4765.5
  5108.3  5153.5  5196.1  5267.8  5369.4  5419.8  5497.4
  708.75  705.32  702.03  699.83  698.02  695.82  689.29  688.85  688.07  687.70
  687.70  688.95  695.25  705.95  714.22  720.95  727.26
  653.90  653.90  653.90  653.90  653.90  653.90  653.90  653.90  653.90  653.90
  653.90  653.90  653.90  653.90  653.90  653.90  653.90
  3918.0  3985.8  4057.9  4122.5  4190.5  4283.0  4559.2  4631.8  4742.1  4765.5
  5108.3  5153.5  5196.1  5267.8  5369.4  5419.8  5497.4
  708.75  705.32  702.03  699.83  698.02  695.82  689.29  688.85  688.07  687.70
  687.70  688.95  695.25  705.95  714.22  720.95  727.26
  653.59  653.59  653.59  653.59  653.59  653.59  653.59  653.59  653.59  653.59
  653.59  653.59  653.59  653.59  653.59  653.59  653.59
Culvert=2,10.5,22.5,63,0.012,0.4,1,8,1,673.9,4988.3,673.59,4988.3,Culvert #1,0,41.5
Culvert Bottom n=0.012
Culvert Bottom Depth=0
Culvert Depth Blocked=0
Culvert=2,10.5,22.5,63,0.012,0.4,1,8,1,673.9,5011.8,673.59,5011.8,Culvert #2,0,41.5
Culvert Bottom n=0.012
Culvert Bottom Depth=0
Culvert Depth Blocked=0
BC Design=,,0,,0,,,,,,

Type RM Length L Ch R = 1,3499,684,684,684
BEGIN DESCRIPTION:
White Road (Kerr) ds
END DESCRIPTION:
XS GIS Cut Line= 4
      1513549.32       699814.49      1513764.06       698845.74
      1513811.14       698705.06      1514045.83       698420.46
#Sta/Elev= 30
  4007.7  707.36  4113.8  699.47  4173.4  696.54  4264.4  694.29  4429.0  695.01
  4463.6  693.67  4534.8  689.38  4663.7  684.63  4921.2  681.55  4929.5  681.85
  4941.2  683.35  4975.0  679.19  4977.0  673.59  5021.0  673.59  5022.0  679.19
  5033.2  682.14  5045.8  684.36  5071.0  685.22  5120.6  685.49  5157.3  688.40
  5177.4  691.84  5193.7  693.49  5239.8  703.32  5287.9  710.22  5319.6  713.95
  5333.8  714.53  5363.3  717.49  5427.8  720.59  5451.5  723.33  5517.2  728.18
#Mann=3,-1,0
  4007.7    0.08       0  4975.0   0.048       0  5022.0    0.08       0
#XS Ineff=2,0
    0.00 4906.50  687.70 5093.50    0.00  687.70
Permanent Ineff=
       F       F
Bank Sta=4975,5022
XS Rating Curve= 0
Exp/Cntr=0.5,0.3

Type RM Length L Ch R = 1,2815,467,467,467
BEGIN DESCRIPTION:
Kerr Creek 6.0
END DESCRIPTION:
XS GIS Cut Line= 3
      1513861.25       700094.57      1514236.80       699337.11
      1514524.98       698925.03
#Sta/Elev= 30
  4146.6  722.13  4222.2  715.89  4263.9  710.73  4311.1  707.87  4338.9  701.69
  4364.5  697.44  4461.6  685.51  4509.5  681.84  4588.9  679.30  4697.3  680.21
  4826.1  679.70  4951.8  682.97  4967.6  681.24  4988.7  674.14  4989.7  672.14
  5010.3  672.14  5011.3  674.14  5024.0  682.13  5027.8  682.52  5091.7  681.61
  5127.7  682.29  5209.6  687.19  5246.0  691.36  5297.4  699.05  5323.6  703.58
  5336.8  707.52  5362.5  712.28  5400.0  716.72  5472.6  720.83  5494.9  723.20
#Mann=3,-1,0
  4146.6    0.08       0  4988.7   0.048       0  5011.3    0.08       0
#XS Ineff=2,0
    0.00 4750.00  681.80               0
Permanent Ineff=
       F       F
Bank Sta=4988.7,5011.3
XS Rating Curve= 0
Exp/Cntr=0.3,0.1

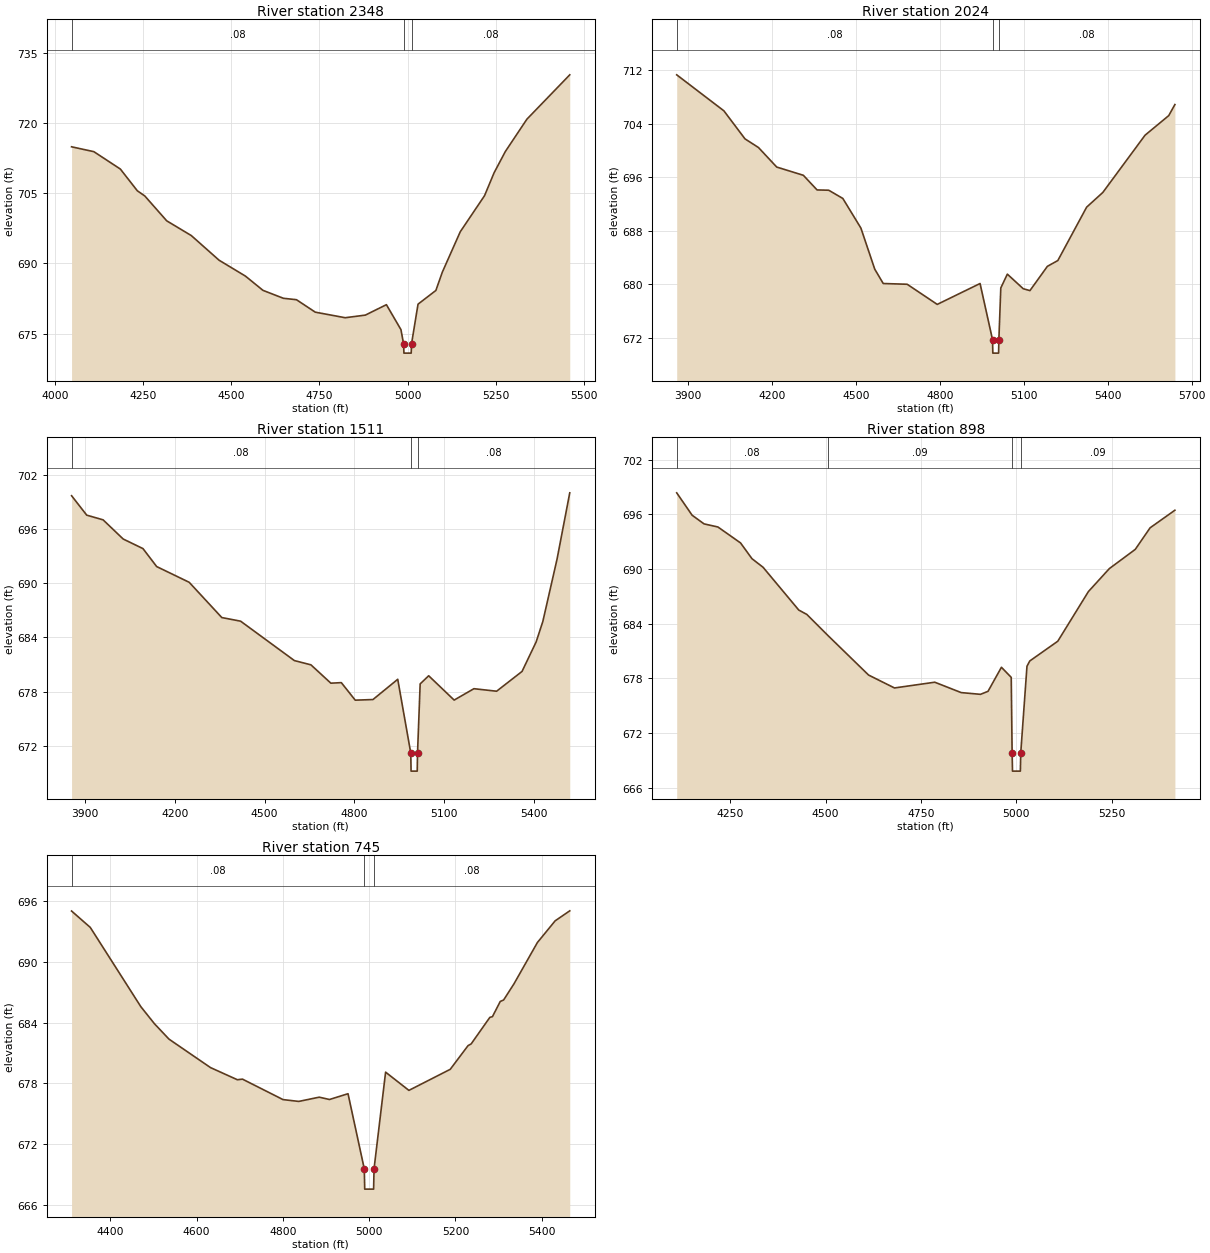
Type RM Length L Ch R = 1,2348,324,324,324
BEGIN DESCRIPTION:
Kerr Creek 5.0
END DESCRIPTION:
XS GIS Cut Line= 4
      1514483.64       700391.99      1514688.10       699462.89
      1514698.45       699403.37      1514682.92       699002.22
#Sta/Elev= 30
  4046.9  714.93  4110.1  713.89  4185.3  710.17  4233.4  705.53  4254.7  704.41
  4316.8  699.10  4386.5  695.95  4465.3  690.68  4540.1  687.28  4589.9  684.23
  4647.6  682.54  4684.9  682.23  4738.2  679.57  4823.1  678.38  4880.3  678.94
  4940.0  681.17  4981.2  675.84  4988.7  672.81  4989.7  670.81  5010.3  670.81
  5011.3  672.81  5029.7  681.28  5080.3  684.21  5098.6  688.12  5149.4  696.75
  5218.4  704.48  5245.5  709.38  5277.2  713.90  5338.6  720.84  5460.1  730.32
#Mann=3,-1,0
  4046.9    0.08       0  4988.7   0.048       0  5011.3    0.08       0
Bank Sta=4988.7,5011.3
XS Rating Curve= 0
Exp/Cntr=0.3,0.1

Type RM Length L Ch R = 1,2024,513,513,513
BEGIN DESCRIPTION:
Kerr Creek 4.0
END DESCRIPTION:
XS GIS Cut Line= 3
      1514656.93       700654.78      1514991.54       699562.99
      1515185.28       698955.13
#Sta/Elev= 30
  3860.3  711.32  4028.9  705.94  4104.3  701.75  4152.4  700.46  4217.6  697.54
  4312.8  696.31  4361.8  694.12  4403.3  694.08  4453.8  692.85  4518.3  688.43
  4567.9  682.28  4598.2  680.14  4683.7  680.03  4791.1  677.02  4944.1  680.14
  4988.7  671.74  4989.7  669.74  5010.3  669.74  5011.3  671.74  5018.2  679.48
  5041.6  681.54  5098.4  679.36  5122.3  679.08  5184.7  682.71  5221.9  683.57
  5324.9  691.55  5382.6  693.74  5533.6  702.30  5618.3  705.23  5640.2  706.88
#Mann=3,-1,0
  3860.3    0.08       0  4988.7   0.048       0  5011.3    0.08       0
Bank Sta=4988.7,5011.3
XS Rating Curve= 0
Exp/Cntr=0.3,0.1

Type RM Length L Ch R = 1,1511,613,613,613
BEGIN DESCRIPTION:
Kerr Creek 3.0
END DESCRIPTION:
XS GIS Cut Line= 3
      1515007.01       700769.41      1515474.83       699723.76
      1515625.00       699225.00
#Sta/Elev= 30
  3854.1  699.68  3904.8  697.53  3959.6  697.01  4026.7  694.89  4092.9  693.83
  4138.8  691.84  4247.6  690.10  4356.6  686.20  4419.5  685.80  4599.4  681.44
  4654.7  680.97  4721.4  678.94  4756.4  679.00  4803.0  677.06  4862.2  677.13
  4945.1  679.37  4988.7  671.21  4989.7  669.21  5010.3  669.21  5011.3  671.21
  5020.1  678.86  5048.6  679.76  5133.8  677.07  5199.9  678.33  5275.8  678.05
  5360.9  680.24  5408.0  683.50  5430.4  685.76  5477.9  692.65  5520.5  700.00
#Mann=3,-1,0
  3854.1    0.08       0  4988.7   0.048       0  5011.3    0.08       0
Bank Sta=4988.7,5011.3
XS Rating Curve= 0
Exp/Cntr=0.3,0.1

Type RM Length L Ch R = 1,898,153,153,153
BEGIN DESCRIPTION:
Kerr Creek 2.0
END DESCRIPTION:
XS GIS Cut Line= 3
      1515548.09       700813.97      1515995.00       700049.84
      1516075.32       699638.13
#Sta/Elev= 30
  4110.3  698.37  4150.7  695.91  4181.9  694.96  4218.2  694.62  4277.5  692.87
  4307.4  691.14  4336.4  690.20  4430.0  685.50  4451.1  685.02  4505.8  682.73
  4612.7  678.37  4680.6  676.95  4786.1  677.58  4855.4  676.44  4905.9  676.25
  4925.6  676.58  4960.7  679.22  4986.4  678.11  4988.7  669.82  4989.7  667.82
  5010.3  667.82  5011.3  669.82  5027.6  679.33  5034.9  679.91  5108.3  682.08
  5188.5  687.53  5243.3  690.05  5311.2  692.16  5350.1  694.53  5415.0  696.46
#Mann=4,-1,0
  4110.3    0.08       0  4505.8    0.09       0  4988.7   0.048       0
  5011.3    0.09       0
Bank Sta=4988.7,5011.3
XS Rating Curve= 0
Exp/Cntr=0.3,0.1

Type RM Length L Ch R = 1,745,0,0,0
BEGIN DESCRIPTION:
Kerr Creek 1.0
END DESCRIPTION:
XS GIS Cut Line= 4
      1515764.56       700713.41      1516124.91       700127.84
      1516218.47       699968.45      1516100.64       699712.01
#Sta/Elev= 30
  4310.3  695.02  4353.7  693.40  4470.9  685.57  4502.4  683.89  4536.1  682.37
  4632.3  679.56  4694.6  678.36  4706.4  678.42  4800.4  676.40  4836.8  676.22
  4884.2  676.64  4908.0  676.41  4951.0  676.98  4988.7  669.56  4989.7  667.56
  5010.3  667.56  5011.3  669.56  5038.1  679.11  5092.1  677.31  5187.9  679.39
  5229.2  681.73  5236.4  681.90  5279.7  684.52  5285.7  684.59  5303.8  686.09
  5311.7  686.24  5335.6  687.83  5389.9  691.91  5431.0  694.05  5464.9  695.04
#Mann=3,-1,0
  4310.3    0.08       0  4988.7   0.048       0  5011.3    0.08       0
Bank Sta=4988.7,5011.3
XS Rating Curve= 0
Exp/Cntr=0.3,0.1

Chan Stop Cuts=-1