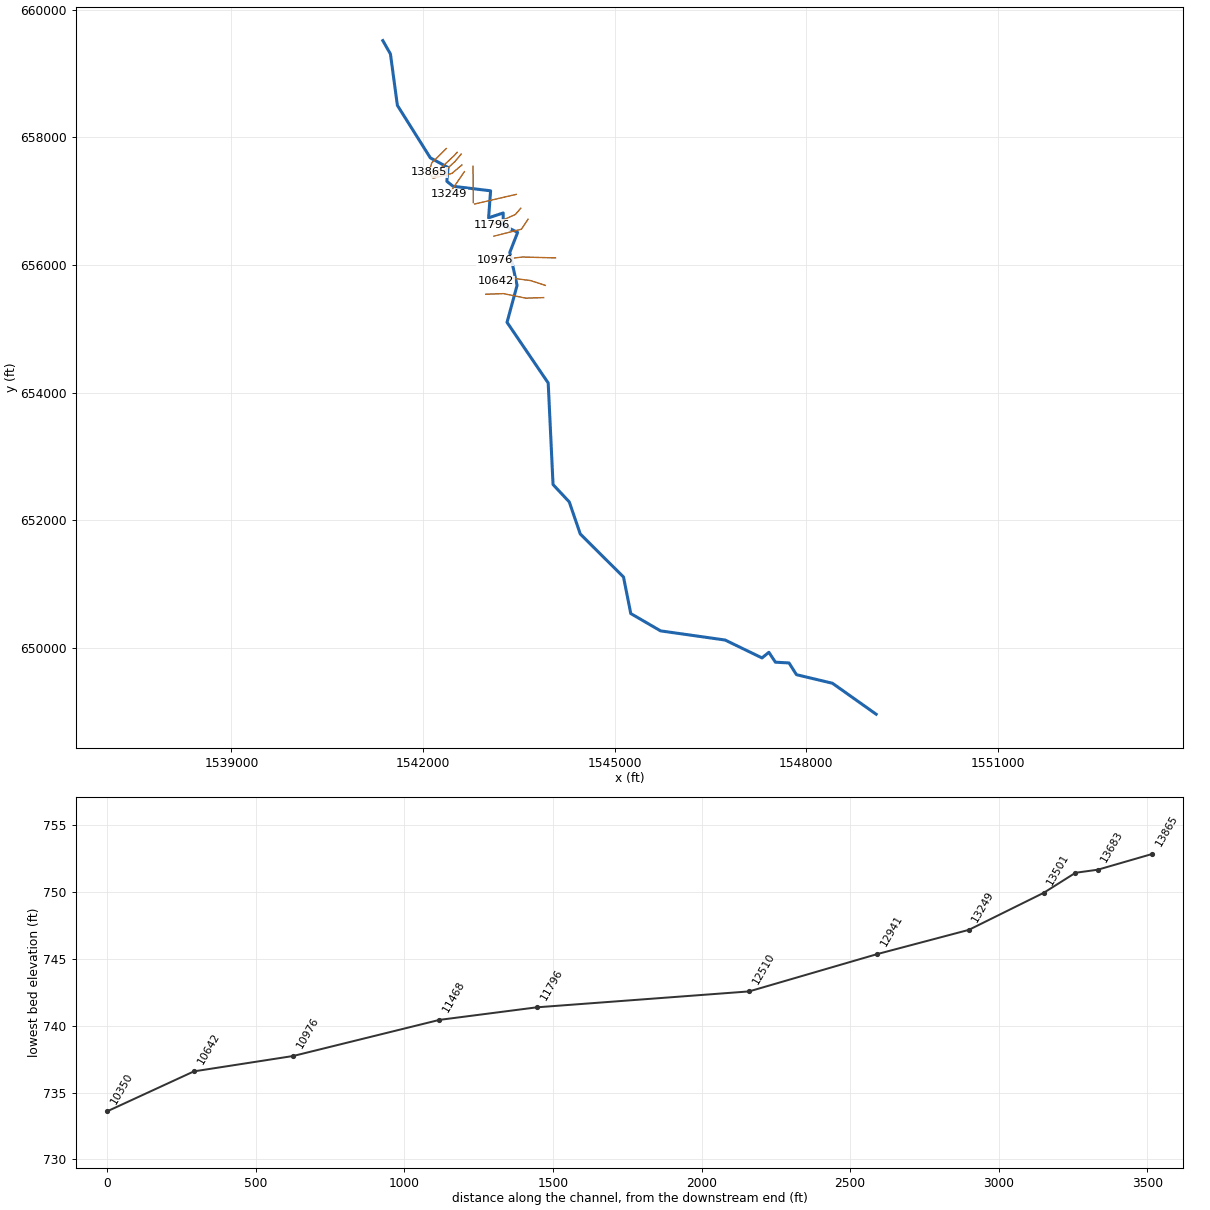
--- Bostian Heights Branch.prj (project) ---

Proj Title=Bostian Heights Branch Detailed Study
Current Plan=p01
Default Exp/Contr=0.3,0.1
English Units
Geom File=g01
Flow File=f02
Flow File=f01
Plan File=p02
Plan File=p01
Y Axis Title=Elevation
X Axis Title(PF)=Main Channel Distance
X Axis Title(XS)=Station
BEGIN DESCRIPTION:
Bostian Heights Branch
END DESCRIPTION:
DSS Export Rating Curves= 0
DSS Export Rating Curve Sorted= 0
DSS Export Volume Flow Curves= 0
DXF OffsetX= 0
DXF OffsetY= 0
DXF ScaleX= 1
DXF ScaleY= 10

--- Bostian Heights Branch.p01 (plan) ---

Plan Title=Multiple Run
Program Version=3.12
Short Identifier=Multiple
Geom File=g01
Flow File=f01
Subcritical Flow
K Sum by GR= 0
Std Step Tol= 0.01
Critical Tol= 0.01
Num of Std Step Trials= 20
Max Error Tol= 0.3
Flow Tol Ratio= 0.001
Split Flow NTrial= 30
Split Flow Tol= 0.02
Split Flow Ratio= 0.02
Log Output Level= 0
Friction Slope Method= 1
Unsteady Friction Slope Method= 2
Unsteady Bridges Friction Slope Method= 1
Parabolic Critical Depth
Global Vel Dist= 0 , 0 , 0
Global Log Level= 0
CheckData=True
Encroach Param=-1 ,0,0, 0
BEGIN DESCRIPTION:
Multiple Run
END DESCRIPTION:
Computation Interval=1HOUR
Output Interval=1HOUR
Run HTab= 0
Run UNet= 0
Run PostProcess= 0
UNET Theta= 1
UNET Theta Warmup= 1
UNET ZTol= 0.02
UNET ZSATol= 0.05
UNET MxIter= 20
UNET MaxInSteps= 0
UNET DtIC= 0
UNET DtMin= 0
UNET MaxCRTS= 20
UNET WFStab= 2
UNET SFStab= 1
UNET WFX= 1
UNET SFX= 1
UNET DSS MLevel= 4
UNET DZMax Abort= 100
UNET Convert EG Bridges=-1
UNET Use Existing IB Tables=-1
UNET Froude Reduction=False
UNET Froude Limit= 1
UNET Froude Power= 10
Instantaneous Interval=1HOUR
Write IC File= 0
Echo Input=False
Echo Output=False
Write Detailed= 0
Detailed Automatic Start=False, 10

--- Bostian Heights Branch.p02 (plan) ---

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Plan Title=Floodway Run
Short Identifier=Floodway
Geom File=g01
Flow File=f02
Encroach Param=-1 ,5,5, 2
Encroach River=Bostian Heights
Encroach Reach=Reach-1
Encroach Node=13865
       1    4960    5013
Encroach Node=13683
       1    4982  5012.9
Encroach Node=13608
       1  4984.5  5009.5
Encroach Node=13501
       1    4986    5018
Encroach Node=13249
       1  4986.8  5047.7
Encroach Node=12941
       1    4970    5020
Encroach Node=12510
       1    4924 5021.47
Encroach Node=11796
       1 4916.69 5016.07
Encroach Node=11468
       1    4970    5085
Encroach Node=10976
       1    4810  5014.8
Encroach Node=10642
       1    4917    5068
Encroach Node=10350
       1    4902    5012
Floodway Run

--- Bostian Heights Branch.f01 (steady flow) ---

Flow Title=Multiple
Number of Profiles=4
Profile Names=10-year,50-year,100-year,500-year
River Rch & RM= Bostian Heights ,Reach-1,13865
     191     353     440     697
River Rch & RM= Bostian Heights ,Reach-1,12510
     507     898    1104    1698
River Rch & RM= Bostian Heights ,Reach-1,10976
     864    1498    1827    2764
River Rch & RM= Bostian Heights ,Reach-1,10350
     670    1190    1450    2040
Boundary for River Rch & Prof#=Bostian Heights ,Reach-1,1
Up Type=0
Dn Type=1
Dn Known WS=739.2
Boundary for River Rch & Prof#=Bostian Heights ,Reach-1,2
Up Type=0
Dn Type=1
Dn Known WS=740.6
Boundary for River Rch & Prof#=Bostian Heights ,Reach-1,3
Up Type=0
Dn Type=1
Dn Known WS=741.15
Boundary for River Rch & Prof#=Bostian Heights ,Reach-1,4
Up Type=0
Dn Type=1
Dn Known WS=741.9

--- Bostian Heights Branch.f02 (steady flow) ---

Flow Title=Floodway
Number of Profiles=2
Profile Names=100-year,100-FW
River Rch & RM= Bostian Heights ,Reach-1,13865
     440     440
River Rch & RM= Bostian Heights ,Reach-1,12510
    1104    1104
River Rch & RM= Bostian Heights ,Reach-1,10976
    1827    1827
River Rch & RM= Bostian Heights ,Reach-1,10350
    1450    1450
Boundary for River Rch & Prof#=Bostian Heights ,Reach-1,1
Up Type=0
Dn Type=1
Dn Known WS=741.15
Boundary for River Rch & Prof#=Bostian Heights ,Reach-1,2
Up Type=0
Dn Type=1
Dn Known WS=741.45

--- Bostian Heights Branch.g01 (geometry) ---

Geom Title=Existing Conditions

River Reach=Bostian Heights ,Reach-1
Reach XY= 30
      1541370.40       659514.31      1541489.78       659304.03
      1541598.45       658499.82      1542114.50       657678.06
      1542391.94       657526.30      1542372.95       657310.59
      1542470.63       657232.81      1543058.50       657161.56
      1543026.98       656738.63      1543256.25       656814.61
      1543256.25       656620.61      1543481.88       656510.56
      1543359.36       656197.34      1543473.13       655681.44
      1543315.94       655101.72      1543960.63       654151.69
      1544036.50       652560.63      1544290.50       652289.13
      1544462.75       651786.94      1545140.13       651112.56
      1545254.00       650540.38      1545721.00       650268.88
      1546731.13       650125.81      1547309.25       649845.56
      1547417.25       649933.13      1547519.38       649778.38
      1547732.50       649766.75      1547849.25       649582.81
      1548412.75       649448.50      1549097.38       648963.56

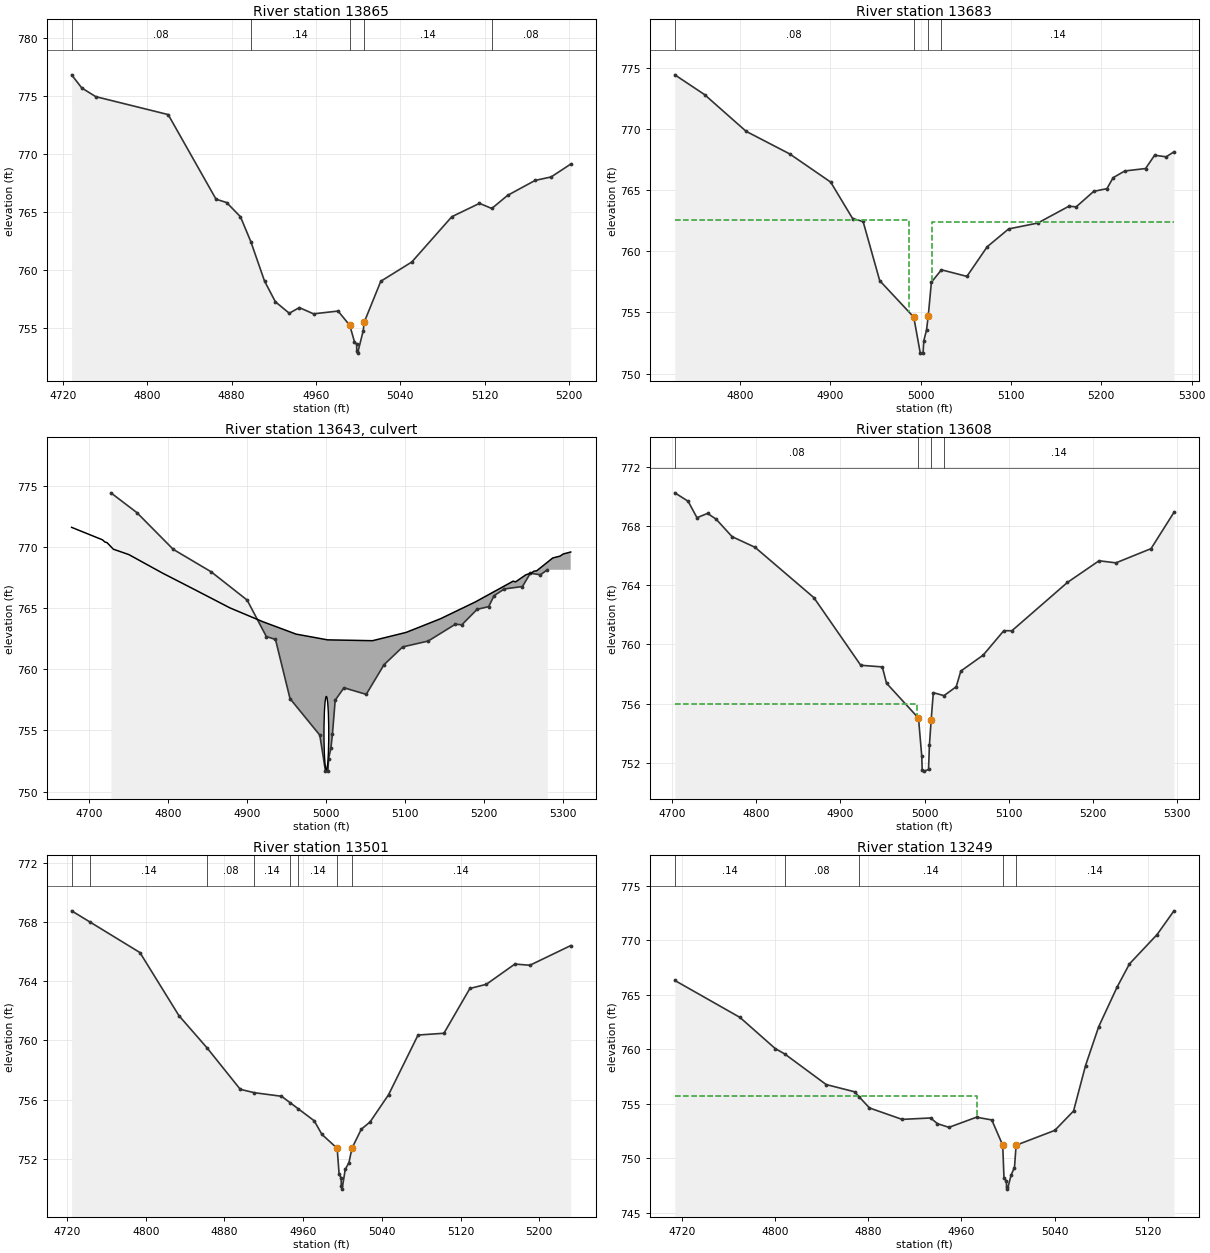
Type RM Length L Ch R = 1,13865,173,182,172
BEGIN DESCRIPTION:
Bostian Heights Branch 9.0
END DESCRIPTION:
XS GIS Cut Line= 3
      1542364.60       657823.56      1542138.07       657600.57
      1542092.05       657451.90
#Sta/Elev= 30
  4728.3  776.85  4737.9  775.72  4751.1  774.97  4819.9  773.42  4865.3  766.12
  4875.4  765.83  4888.5  764.60  4898.3  762.46  4911.3  759.06  4921.6  757.27
  4934.8  756.28  4944.3  756.77  4957.8  756.23  4981.1  756.47  4992.2  755.23
  4996.6  753.83  4998.7  753.60  4998.8  753.04  4999.6  752.84  5005.0  754.79
  5005.8  755.49  5021.6  759.04  5051.0  760.70  5089.0  764.61  5115.2  765.76
  5126.9  765.32  5141.9  766.45  5168.0  767.74  5183.2  768.04  5201.8  769.15
#Mann=5,-1,0
  4728.3    0.08       0  4898.3    0.14       0  4992.2    0.05       0
  5005.8    0.14       0  5126.9    0.08       0
Bank Sta=4992.2,5005.8
XS Rating Curve= 0
Exp/Cntr=0.5,0.3

Type RM Length L Ch R = 1,13683,74,75,77
BEGIN DESCRIPTION:
Daugherty Rd (BHB) us
END DESCRIPTION:
XS GIS Cut Line= 4
      1542534.70       657764.44      1542485.17       657710.66
      1542264.27       657502.51      1542124.09       657396.31
#Sta/Elev= 30
  4727.9  774.48  4760.8  772.86  4806.8  769.85  4855.0  768.00  4900.4  765.69
  4924.7  762.70  4936.3  762.46  4954.7  757.61  4992.4  754.62  4999.6  751.67
  5002.7  751.71  5003.5  752.68  5006.5  753.56  5008.4  754.70  5011.9  757.48
  5023.0  758.50  5051.2  757.96  5073.7  760.39  5097.4  761.85  5129.6  762.33
  5164.1  763.71  5172.2  763.66  5191.6  764.93  5206.2  765.15  5213.1  766.05
  5226.0  766.60  5249.0  766.80  5259.0  767.89  5271.8  767.76  5280.4  768.17
#Mann=4,-1,0
  4727.9    0.08       0  4992.4    0.05       0  5008.4    0.08       0
  5023.0    0.14       0
#XS Ineff=2,0
    0.00 4987.00  762.60 5013.00    0.00  762.41
Permanent Ineff=
       F       F
Bank Sta=4992.4,5008.4
XS Rating Curve= 0
Exp/Cntr=0.5,0.3

Type RM Length L Ch R =2,13643,,,
BEGIN DESCRIPTION:
Daugherty Rd (BHB) TOR
Structure ID: R_DBC_01A
Detailed Survey Structure
END DESCRIPTION:
Bridge Culvert--1,0,-1,-1,0
Deck Dist Width WeirC Skew NumUp NumDn MinLoCord MaxHiCord MaxSubmerge Is_Ogee
10,60,3,,26,26,,,0.95,0,1,1,,,
  4678.2  4717.2  4720.5  4723.0  4731.0  4750.6  4793.0  4835.4  4878.6  4920.1
  4962.4  5002.2  5059.1  5101.7  5145.2  5189.4  5237.2  5240.2  5253.5  5260.3
  5263.6  5267.0  5287.3  5296.4  5300.7  5310.1
  771.65  770.63  770.44  770.40  769.86  769.42  767.91  766.50  765.05  763.92
  762.90  762.43  762.36  763.04  764.16  765.54  767.24  767.18  767.77  767.90
  768.06  768.09  769.14  769.29  769.47  769.63
  731.67  731.67  731.67  731.67  731.67  731.67  731.67  731.67  731.67  731.67
  731.67  731.67  731.67  731.67  731.67  731.67  731.67  731.67  731.67  731.67
  731.67  731.67  731.67  731.67  731.67  731.67
  4678.2  4717.2  4720.5  4723.0  4731.0  4750.6  4793.0  4835.4  4878.6  4920.1
  4962.4  5002.2  5059.1  5101.7  5145.2  5189.4  5237.2  5240.2  5253.5  5260.3
  5263.6  5267.0  5287.3  5296.4  5300.7  5310.1
  771.65  770.63  770.44  770.40  769.86  769.42  767.91  766.50  765.05  763.92
  762.90  762.43  762.36  763.04  764.16  765.54  767.24  767.18  767.77  767.90
  768.06  768.09  769.14  769.29  769.47  769.63
  731.44  731.44  731.44  731.44  731.44  731.44  731.44  731.44  731.44  731.44
  731.44  731.44  731.44  731.44  731.44  731.44  731.44  731.44  731.44  731.44
  731.44  731.44  731.44  731.44  731.44  731.44
Culvert=1,6,,60,0.024,0.9,1,2,3,751.79,5000.7,751.54,5000.7,Culvert #1,0,10
Culvert Bottom n=0.024
Culvert Bottom Depth=0
Culvert Depth Blocked=0
BC Design=,,0,,0,,,,,,

Type RM Length L Ch R = 1,13608,116,107,93
BEGIN DESCRIPTION:
Daugherty Rd (BHB) ds
END DESCRIPTION:
XS GIS Cut Line= 5
      1542597.04       657736.16      1542502.16       657621.45
      1542364.81       657496.85      1542192.06       657386.40
      1542139.63       657375.06
#Sta/Elev= 30
  4703.2  770.24  4719.0  769.67  4729.5  768.56  4742.1  768.85  4752.3  768.46
  4771.2  767.28  4798.5  766.56  4868.4  763.16  4924.1  758.59  4949.7  758.48
  4954.7  757.38  4992.7  755.02  4996.6  752.43  4997.1  751.49  4999.6  751.44
  5004.6  751.55  5005.7  753.21  5007.7  754.87  5010.3  756.74  5023.0  756.54
  5037.5  757.14  5043.0  758.20  5069.6  759.28  5094.1  760.93  5103.6  760.92
  5169.7  764.19  5207.2  765.65  5227.3  765.51  5269.0  766.47  5296.2  768.92
#Mann=4,-1,0
  4703.2    0.08       0  4992.7    0.05       0  5007.7    0.08       0
  5023.0    0.14       0
#XS Ineff=2,0
    0.00 4991.50  756.00 5008.50    0.00  755.00
Permanent Ineff=
       F       F
Bank Sta=4992.7,5007.7
XS Rating Curve= 0
Exp/Cntr=0.5,0.3

Type RM Length L Ch R = 1,13501,229,252,261
BEGIN DESCRIPTION:
Bostian Heights Branch 8.5
END DESCRIPTION:
XS GIS Cut Line= 4
      1542609.24       657566.58      1542454.16       657434.77
      1542306.83       657396.00      1542159.48       657361.10
#Sta/Elev= 30
  4724.7  768.76  4743.7  767.99  4794.1  765.94  4833.8  761.67  4862.5  759.48
  4896.1  756.69  4910.5  756.46  4938.0  756.22  4946.9  755.78  4955.1  755.37
  4971.3  754.56  4979.1  753.64  4994.6  752.70  4996.6  750.93  4998.7  750.70
  4998.8  750.14  4999.6  749.94  5002.8  751.27  5006.6  751.74  5009.6  752.70
  5019.1  753.99  5028.0  754.48  5046.8  756.32  5076.8  760.36  5103.1  760.48
  5129.5  763.51  5146.2  763.79  5175.2  765.16  5190.5  765.08  5232.0  766.41
#Mann=8,-1,0
  4724.7    0.08       0  4743.7    0.14       0  4862.5    0.08       0
  4910.5    0.14       0  4946.9    0.08       0  4955.1    0.14       0
  4994.6    0.05       0  5009.6    0.14       0
Bank Sta=4994.6,5009.6
XS Rating Curve= 0
Exp/Cntr=0.3,0.1

Type RM Length L Ch R = 1,13249,296,308,323
BEGIN DESCRIPTION:
Bostian Heights Branch 8.0
END DESCRIPTION:
XS GIS Cut Line= 2
      1542647.76       657461.09      1542406.13       657107.22
#Sta/Elev= 30
  4714.0  766.32  4769.9  762.93  4800.3  760.06  4808.3  759.58  4843.9  756.77
  4868.4  756.10  4872.5  755.61  4881.1  754.62  4909.1  753.57  4933.6  753.70
  4939.4  753.18  4949.3  752.84  4973.0  753.77  4986.1  753.52  4995.5  751.20
  4996.6  748.16  4998.7  747.93  4998.8  747.37  4999.6  747.17  5002.8  748.50
  5005.6  749.15  5007.0  751.20  5040.2  752.56  5056.3  754.34  5066.6  758.51
  5077.9  762.08  5093.6  765.69  5104.3  767.84  5128.0  770.53  5142.5  772.71
#Mann=5,-1,0
  4714.0    0.14       0  4808.3    0.08       0  4872.5    0.14       0
  4995.5    0.05       0  5007.0    0.14       0
#XS Ineff=2,0
    0.00 4973.80  755.75               0
Permanent Ineff=
       F       F
Bank Sta=4995.5,5007
XS Rating Curve= 0
Exp/Cntr=0.3,0.1

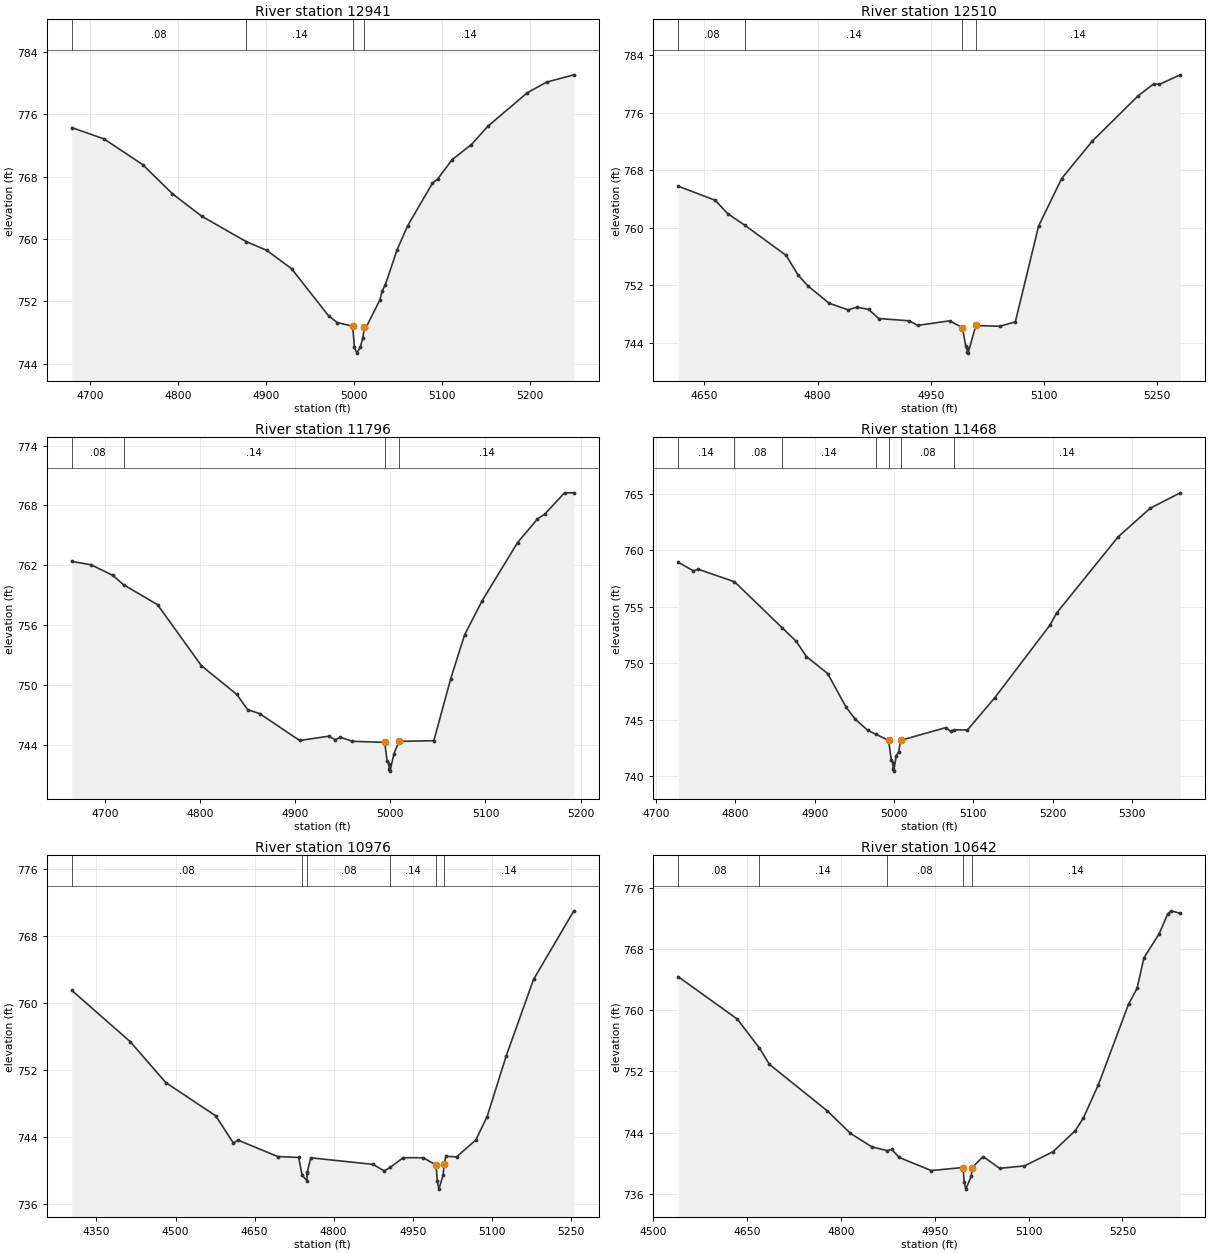
Type RM Length L Ch R = 1,12941,474,431,379
BEGIN DESCRIPTION:
Bostian Heights Branch 7.0
END DESCRIPTION:
XS GIS Cut Line= 2
      1542783.32       657547.07      1542787.67       656976.89
#Sta/Elev= 30
  4679.4  774.28  4715.9  772.84  4760.0  769.53  4793.7  765.80  4826.8  762.93
  4877.4  759.67  4900.7  758.55  4929.1  756.18  4971.0  750.15  4981.0  749.28
  4998.4  748.81  5000.4  746.12  5003.2  745.36  5007.0  746.12  5010.0  747.31
  5011.7  748.69  5014.1  748.77  5029.4  752.20  5031.8  753.32  5035.6  754.15
  5048.7  758.57  5060.7  761.66  5088.9  767.13  5095.0  767.70  5111.4  770.17
  5133.1  772.10  5152.2  774.48  5196.9  778.77  5218.8  780.12  5249.6  781.05
#Mann=4,-1,0
  4679.4    0.08       0  4877.4    0.14       0  4998.4    0.05       0
  5011.7    0.14       0
Bank Sta=4998.4,5011.7
XS Rating Curve= 0
Exp/Cntr=0.3,0.1

Type RM Length L Ch R = 1,12510,468,714,630
BEGIN DESCRIPTION:
Bostian Heights Branch 6.0
END DESCRIPTION:
XS GIS Cut Line= 2
      1543458.23       657105.24      1542809.47       656955.11
#Sta/Elev= 30
  4615.2  765.77  4664.2  763.81  4681.0  761.93  4703.8  760.32  4758.3  756.15
  4774.0  753.45  4787.0  751.93  4815.4  749.50  4840.7  748.58  4852.0  748.96
  4867.7  748.64  4881.1  747.38  4921.5  747.06  4932.7  746.42  4975.0  747.06
  4992.0  746.13  4996.6  743.56  4998.7  743.33  4998.8  742.77  4999.6  742.57
  5009.9  746.41  5041.6  746.30  5062.3  746.92  5093.2  760.25  5123.7  766.83
  5164.2  772.01  5224.9  778.30  5246.0  780.00  5253.3  779.91  5281.1  781.24
#Mann=4,-1,0
  4615.2    0.08       0  4703.8    0.14       0  4992.0    0.05       0
  5009.9    0.14       0
Bank Sta=4992,5009.9
XS Rating Curve= 0
Exp/Cntr=0.3,0.1

Type RM Length L Ch R = 1,11796,268,328,285
BEGIN DESCRIPTION:
Bostian Heights Branch 5.0
END DESCRIPTION:
XS GIS Cut Line= 3
      1543531.97       656889.84      1543444.89       656789.71
      1543083.66       656628.67
#Sta/Elev= 30
  4664.8  762.39  4685.2  762.05  4708.2  760.98  4719.3  760.05  4755.0  758.06
  4801.2  751.94  4838.5  749.06  4849.8  747.54  4862.5  747.14  4904.5  744.45
  4935.1  744.88  4942.0  744.52  4947.4  744.77  4960.0  744.37  4994.0  744.26
  4996.6  742.37  4998.7  742.14  4998.8  741.58  4999.6  741.38  5003.8  743.14
  5009.1  744.36  5045.7  744.43  5063.5  750.65  5078.0  755.02  5096.4  758.43
  5133.8  764.28  5154.7  766.64  5162.4  767.13  5183.2  769.26  5193.0  769.26
#Mann=4,-1,0
  4664.8    0.08       0  4719.3    0.14       0  4994.0    0.05       0
  5009.1    0.14       0
Bank Sta=4994,5009.1
XS Rating Curve= 0
Exp/Cntr=0.3,0.1

Type RM Length L Ch R = 1,11468,435,492,462
BEGIN DESCRIPTION:
Bostian Heights Branch 4.0
END DESCRIPTION:
XS GIS Cut Line= 3
      1543645.11       656716.59      1543540.65       656559.90
      1543109.79       656451.10
#Sta/Elev= 30
  4728.1  758.92  4747.2  758.17  4753.6  758.30  4799.0  757.20  4859.2  753.12
  4876.9  751.92  4889.6  750.58  4916.4  749.08  4939.8  746.08  4951.3  745.03
  4967.1  744.04  4976.7  743.72  4993.2  743.16  4996.6  741.43  4998.7  741.20
  4998.8  740.64  4999.6  740.44  5002.8  741.77  5006.0  742.17  5008.2  743.16
  5065.2  744.29  5071.2  743.98  5076.1  744.09  5092.6  744.09  5127.0  746.94
  5196.3  753.34  5205.1  754.45  5282.5  761.18  5322.9  763.71  5360.8  765.07
#Mann=7,-1,0
  4728.1    0.14       0  4799.0    0.08       0  4859.2    0.14       0
  4976.7    0.08       0  4993.2    0.05       0  5008.2    0.08       0
  5076.1    0.14       0
Bank Sta=4993.2,5008.2
XS Rating Curve= 0
Exp/Cntr=0.3,0.1

Type RM Length L Ch R = 1,10976,341,334,316
BEGIN DESCRIPTION:
Bostian Heights Branch 3.0
END DESCRIPTION:
XS GIS Cut Line= 3
      1544075.39       656110.66      1543557.11       656124.42
      1543125.91       656073.97
#Sta/Elev= 30
  4303.1  761.53  4414.2  755.38  4481.4  750.50  4576.3  746.51  4609.8  743.25
  4618.4  743.61  4694.0  741.64  4733.7  741.53  4740.0  739.41  4749.4  738.74
  4749.5  739.66  4750.0  739.79  4756.6  741.49  4875.0  740.70  4895.9  739.92
  4907.1  740.33  4931.8  741.50  4969.7  741.50  4994.3  740.63  4996.6  738.73
  4999.6  737.74  5007.5  739.39  5009.8  740.77  5013.0  741.67  5033.2  741.60
  5069.7  743.62  5091.2  746.43  5127.4  753.69  5179.3  762.85  5255.7  771.05
#Mann=6,-1,0
  4303.1    0.08       0  4740.0    0.05       0  4750.0    0.08       0
  4907.1    0.14       0  4994.3    0.05       0  5009.8    0.14       0
Bank Sta=4994.3,5009.8
XS Rating Curve= 0
Exp/Cntr=0.3,0.1

Type RM Length L Ch R = 1,10642,283,292,274
BEGIN DESCRIPTION:
Bostian Heights Branch 2.0
END DESCRIPTION:
XS GIS Cut Line= 4
      1543914.98       655680.70      1543688.63       655754.70
      1543266.44       655811.28      1543144.54       655745.97
#Sta/Elev= 30
  4540.1  764.39  4634.5  758.84  4669.7  755.07  4685.8  752.92  4778.2  746.84
  4815.4  743.88  4849.4  742.13  4874.2  741.62  4881.2  741.79  4893.5  740.73
  4944.3  739.02  4995.5  739.42  4996.9  737.58  4999.6  736.59  5008.6  738.31
  5009.5  739.38  5027.4  740.85  5053.8  739.31  5093.4  739.63  5139.3  741.50
  5174.8  744.26  5187.6  745.91  5211.5  750.24  5260.0  760.85  5273.5  762.88
  5284.3  766.85  5308.5  769.98  5322.3  772.59  5327.7  773.01  5342.5  772.68
#Mann=5,-1,0
  4540.1    0.08       0  4669.7    0.14       0  4874.2    0.08       0
  4995.5    0.05       0  5009.5    0.14       0
Bank Sta=4995.5,5009.5
XS Rating Curve= 0
Exp/Cntr=0.3,0.1

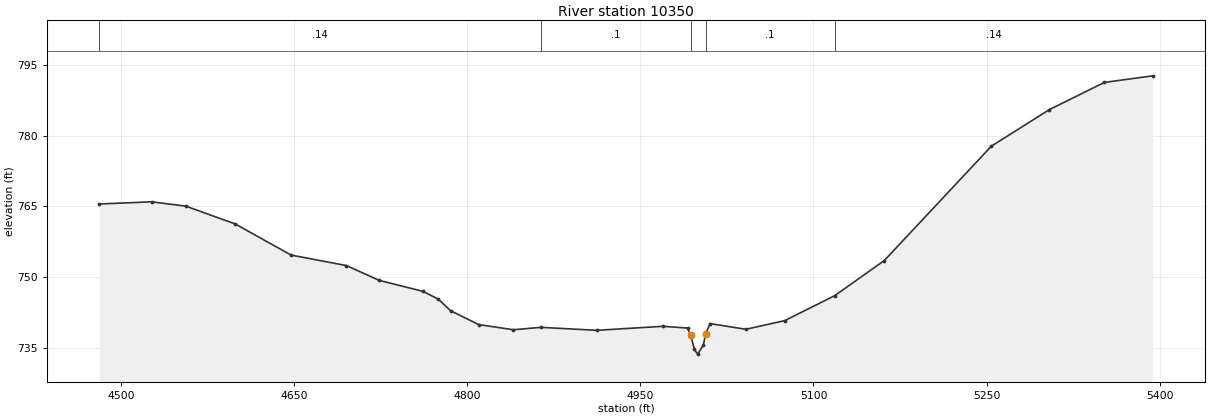
Type RM Length L Ch R = 1,10350,0,0,0
BEGIN DESCRIPTION:
Bostian Heights Branch 1.0
END DESCRIPTION:
XS GIS Cut Line= 4
      1543888.84       655489.20      1543610.34       655480.20
      1543259.06       655551.35      1542983.50       655541.42
#Sta/Elev= 30
  4481.2  765.50  4526.5  765.96  4556.2  765.04  4599.0  761.25  4647.4  754.64
  4695.3  752.42  4723.7  749.27  4761.6  746.94  4775.0  745.27  4785.6  742.82
  4809.9  739.88  4839.9  738.78  4863.8  739.29  4912.1  738.66  4969.5  739.51
  4990.9  739.14  4993.5  737.67  4996.9  734.59  4999.6  733.60  5004.6  735.49
  5006.5  737.88  5010.4  740.09  5041.5  738.88  5075.1  740.72  5118.3  746.00
  5161.4  753.49  5254.2  777.79  5304.4  785.55  5352.1  791.33  5394.0  792.73
#Mann=5,-1,0
  4481.2    0.14       0  4863.8     0.1       0  4993.5    0.05       0
  5006.5     0.1       0  5118.3    0.14       0
Bank Sta=4993.5,5006.5
XS Rating Curve= 0
Exp/Cntr=0.3,0.1

Chan Stop Cuts=-1