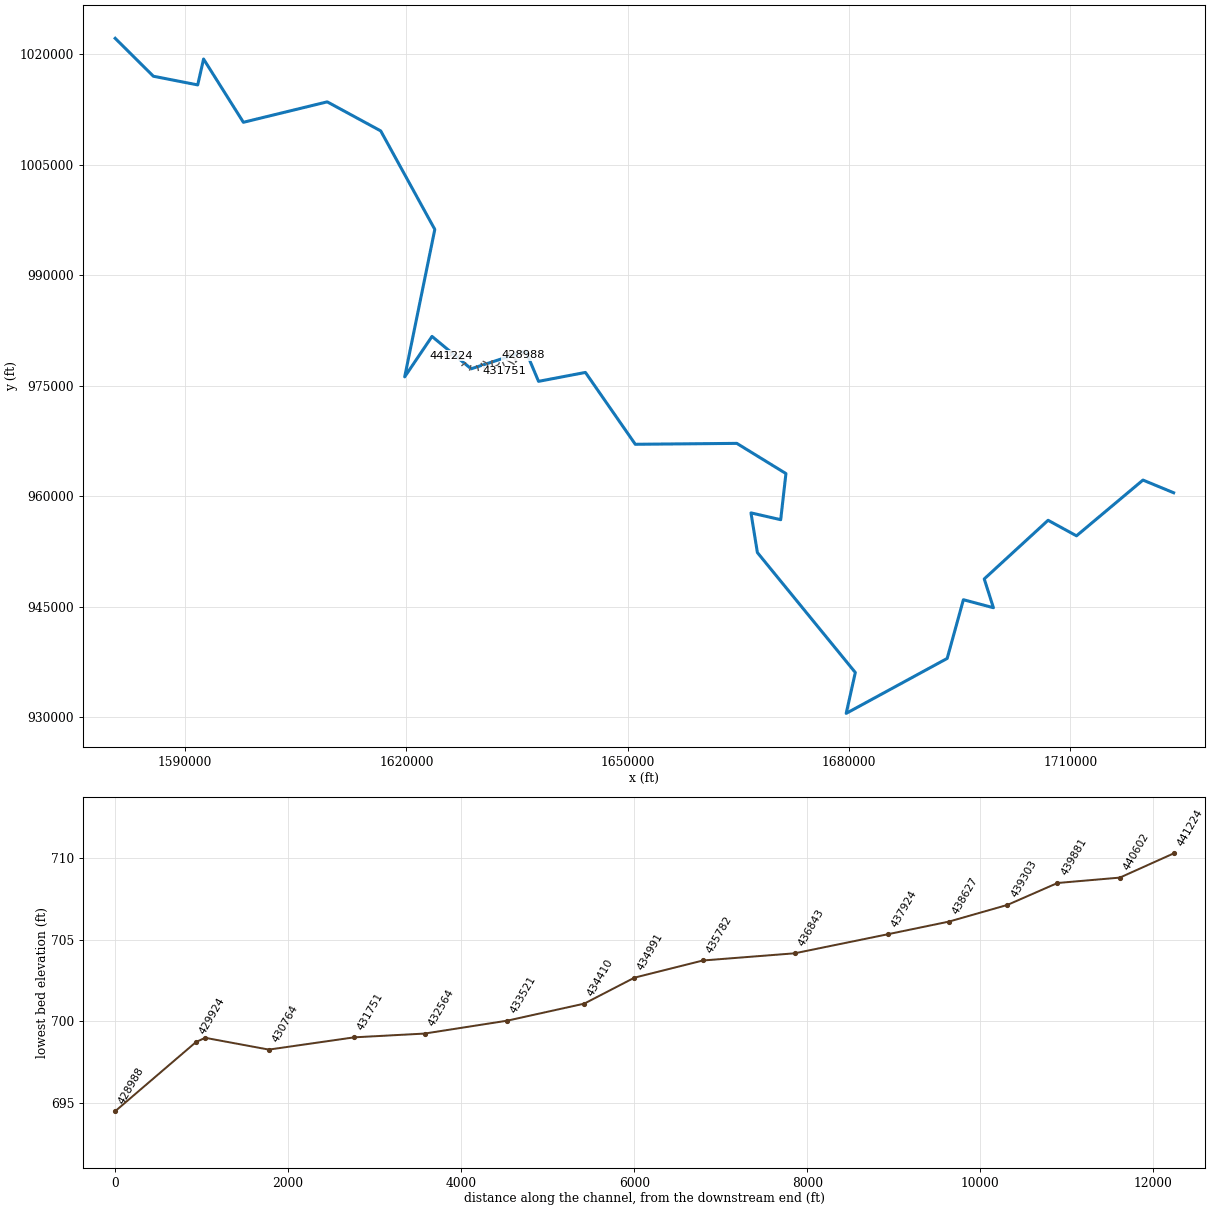
--- lds_dan_rvr_bctfud_lower.prj (project) ---

Proj Title=Dan River Limited Detail Study Lower
Current Plan=p02
Default Exp/Contr=0.3,0.1
English Units
Geom File=g02
Geom File=g01
Flow File=f01
Plan File=p02
Plan File=p01
Y Axis Title=Elevation
X Axis Title(PF)=Main Channel Distance
X Axis Title(XS)=Station
BEGIN DESCRIPTION:
Dan River
END DESCRIPTION:
DSS Export Rating Curves= 0
DSS Export Rating Curve Sorted= 0
DSS Export Volume Flow Curves= 0
DXF OffsetX= 0
DXF OffsetY= 0
DXF ScaleX= 1
DXF ScaleY= 10

--- lds_dan_rvr_bctfud_lower.p02 (plan) ---

Plan Title=REV3/16/06
Program Version=3.12
Short Identifier=REV31606
Geom File=g02
Flow File=f01
Subcritical Flow
K Sum by GR= 0
Std Step Tol= 0.01
Critical Tol= 0.01
Num of Std Step Trials= 20
Max Error Tol= 0.3
Flow Tol Ratio= 0.001
Split Flow NTrial= 30
Split Flow Tol= 0.02
Split Flow Ratio= 0.02
Log Output Level= 0
Friction Slope Method= 1
Unsteady Friction Slope Method= 2
Unsteady Bridges Friction Slope Method= 1
Parabolic Critical Depth
Global Vel Dist= 0 , 0 , 0
Global Log Level= 0
CheckData=True
Encroach Param=-1 ,8,8, 2
Encroach River=Dan River
Encroach Reach=Reach-1
Encroach Node=574629
       4      .7
Encroach Node=574175
       4      .7
Encroach Node=573791
       4      .7
Encroach Node=573141
       4      .7
Encroach Node=572635
       4      .7
Encroach Node=572116
       4      .7
Encroach Node=571714
       4      .7
Encroach Node=571369
       4      .7
Encroach Node=571026
       4      .7
Encroach Node=570586
       4      .7
Encroach Node=570078
       4      .7
Encroach Node=569612
       4      .7
Encroach Node=568971
       4      .7
Encroach Node=568220
       4      .7
Encroach Node=567599
       4      .7
Encroach Node=567070
       1    4870    5080
Encroach Node=566577
       1    4830    5090
Encroach Node=565914
       1  4892.7 5072.05
Encroach Node=565744
       1  4895.5 5080.09
Encroach Node=565068
       4      .7
Encroach Node=563710
       4      .7
Encroach Node=562876
       4      .7
Encroach Node=562463
       4      .7
Encroach Node=561815
       4      .7
Encroach Node=561365
       4      .7
Encroach Node=560712
       4      .7
Encroach Node=560162
       4      .7
Encroach Node=559433
       4      .4
Encroach Node=558871
       4      .7
Encroach Node=558249
       1    4942 5071.59
Encroach Node=558210
       1  4931.8    5068
Encroach Node=557134
       1 4921.48 5022.81
Encroach Node=556236
       4      .7
Encroach Node=554946
       4      .7
Encroach Node=553911
       4      .7
Encroach Node=553319
       4      .7
Encroach Node=552603
       4      .7
Encroach Node=551904
       4      .7
Encroach Node=551230
       4      .7
Encroach Node=550682
       4      .7
Encroach Node=550309
       4      .7
Encroach Node=549773
       4      .7
Encroach Node=549116
       4      .7
Encroach Node=548791
       4      .7
Encroach Node=548384
       4      .7
Encroach Node=547846
       4      .7
Encroach Node=547372
       1  4921.9 5076.97
Encroach Node=546022
       4      .7
Encroach Node=544967
       4      .7
Encroach Node=543744
       4      .7
Encroach Node=542950
       4      .7
Encroach Node=542632
       4      .7
Encroach Node=542102
       4      .7
Encroach Node=541254
       4      .7
Encroach Node=540791
       4      .7
Encroach Node=540311
       4      .7
Encroach Node=539793
       4      .7
Encroach Node=539278
       4      .7
Encroach Node=538503
       4      .7
Encroach Node=537558
       4      .7
Encroach Node=536794
       4      .7
Encroach Node=535975
       4      .7
Encroach Node=535757
       4      .7
Encroach Node=535484
       4      .7
Encroach Node=534622
       4      .7
Encroach Node=533939
       4      .7
Encroach Node=533092
       4      .7
Encroach Node=532293
       1    4914  5106.1
Encroach Node=532163
       1  4900.5  5100.2
Encroach Node=530855
       4      .7
Encroach Node=529594
       4      .7
Encroach Node=528816
       4      .7
Encroach Node=527979
       4      .7
Encroach Node=527580
       4      .7
Encroach Node=526873
       4      .7
Encroach Node=525969
       4      .7
Encroach Node=525387
       4      .7
Encroach Node=524345
       4      .7
Encroach Node=523616
       4      .7
Encroach Node=522720
       4      .7
Encroach Node=521955
       4      .7
Encroach Node=521268
       4      .7
Encroach Node=520255
       4      .7
Encroach Node=519463
       4      .7
Encroach Node=518820
       4      .7
Encroach Node=518217
       4      .7
Encroach Node=517743
       4      .7
Encroach Node=517425
       4      .7
Encroach Node=517282
       4      .7
Encroach Node=516980
       4      .7
Encroach Node=516649
       4      .7
Encroach Node=515896
       4      .7
Encroach Node=515404
       4      .7
Encroach Node=514829
       4      .7
Encroach Node=514341
       4      .7
Encroach Node=513667
       4      .7
Encroach Node=513044
       4      .7
Encroach Node=512504
       4      .7
Encroach Node=511413
       4      .7
Encroach Node=510917
       4      .7
Encroach Node=510489
       4      .7
Encroach Node=509760
       4      .7
Encroach Node=509056
       4      .7
Encroach Node=508419
       4      .7
Encroach Node=507668
       4      .7
Encroach Node=506793
       4      .7
Encroach Node=506032
       4      .7
Encroach Node=505646
       4      .7
Encroach Node=505056
       4      .7
Encroach Node=504171
       4      .7
Encroach Node=503589
       4      .7
Encroach Node=502892
       4      .7
Encroach Node=502137
       4      .7
Encroach Node=501451
       4      .7
Encroach Node=500449
       4      .7
Encroach Node=499997
       1 4888.82    5120
Encroach Node=499820
       1  4823.7  5124.9
Encroach Node=499094
       4      .7
Encroach Node=498389
       4      .7
Encroach Node=497890
       4      .7
Encroach Node=497376
       4      .7
Encroach Node=496761
       4      .7
Encroach Node=496234
       4      .7
Encroach Node=495660
       4      .7
Encroach Node=494901
       4      .7
Encroach Node=493674
       4      .7
Encroach Node=493008
       4      .7
Encroach Node=492039
       4      .7
Encroach Node=491158
       4      .7
Encroach Node=490299
       4      .7
Encroach Node=489339
       4      .7
Encroach Node=488638
       4      .7
Encroach Node=487947
       4      .7
Encroach Node=487204
       4      .7
Encroach Node=486671
       4      .7
Encroach Node=485838
       4      .7
Encroach Node=485108
       4      .7
Encroach Node=484435
       4      .7
Encroach Node=483697
       4      .7
Encroach Node=482591
       4      .7
Encroach Node=482029
       4      .7
Encroach Node=481347
       4      .7
Encroach Node=480768
       4      .7
Encroach Node=480223
       4      .7
Encroach Node=479852
       4      .7
Encroach Node=479493
       4      .7
Encroach Node=478977
       4      .7
Encroach Node=478424
       4      .7
Encroach Node=477940
       4      .7
Encroach Node=477400
       4      .7
Encroach Node=476672
       4      .7
Encroach Node=475450
       4      .7
Encroach Node=474574
       4      .7
Encroach Node=473767
       4      .7
Encroach Node=473103
       4      .7
Encroach Node=472431
       4      .7
Encroach Node=471797
       4      .7
Encroach Node=471197
       4      .7
Encroach Node=470390
       4      .7
Encroach Node=469583
       4      .7
Encroach Node=469231
       4      .7
Encroach Node=468609
       4      .7
Encroach Node=467766
       4      .7
Encroach Node=466701
       4      .7
Encroach Node=465755
       4      .7
Encroach Node=465125
       1  4806.1  5222.8
Encroach Node=465004
       1 4843.37    5222
Encroach Node=464258
       4      .7
Encroach Node=463776
       4      .7
Encroach Node=463035
       4      .7
Encroach Node=462312
       4      .7
Encroach Node=461542
       4      .7
Encroach Node=460438
       4      .7
Encroach Node=459626
       4      .7
Encroach Node=458755
       4      .7
Encroach Node=457989
       4      .7
Encroach Node=457417
       4      .7
Encroach Node=456894
       4      .7
Encroach Node=455986
       4      .7
Encroach Node=455399
       4      .7
Encroach Node=454580
       4      .7
Encroach Node=454050
       4      .7
Encroach Node=453308
       4      .7
Encroach Node=452742
       1 4935.78 5054.04
Encroach Node=451655
       4      .7
Encroach Node=450824
       4      .7
Encroach Node=449798
       4      .7
Encroach Node=449327
       4      .7
Encroach Node=448886
       4      .7
Encroach Node=448301
       4      .7
Encroach Node=447590
       4      .7
Encroach Node=446780
       4      .7
Encroach Node=446199
       4      .7
Encroach Node=445684
       4      .7
Encroach Node=445466
       4      .7
Encroach Node=444719
       4      .7
Encroach Node=443868
       4      .7
Encroach Node=443402
       1  4931.8 5060.56
Encroach Node=442875
       1  4931.8 5065.55
Encroach Node=442344
       4      .7
Encroach Node=441904
       4      .7
Encroach Node=441224
       4      .7
Encroach Node=440602
       4      .7
Encroach Node=439881
       4      .7
Encroach Node=439303
       4      .7
Encroach Node=438627
       4      .7
Encroach Node=437924
       4      .7
Encroach Node=436843
       4      .7
Encroach Node=435782
       4      .7
Encroach Node=434991
       4      .7
Encroach Node=434410
       4      .7
Encroach Node=433521
       4      .7
Encroach Node=432564
       4      .7
Encroach Node=431751
       4      .7
Encroach Node=430764
       4      .7
Encroach Node=430029
       1    4796    5204
Encroach Node=429924
       1    4811    5189
Encroach Node=428988
       4      .7
Encroach Node=428060
       4      .7
Encroach Node=427309
       4      .7
Encroach Node=426705
       4      .7
Encroach Node=426001
       4      .7
Encroach Node=425232
       4      .7
Encroach Node=423864
       4      .7
Encroach Node=423384
       4      .7
Encroach Node=422621
       4      .7
Encroach Node=421488
       4      .7
Encroach Node=420480
       4      .7
Encroach Node=419300
       4      .7
Encroach Node=418706
       4      .7
Encroach Node=417732
       1    4823    5177
Encroach Node=417664
       1    4833    5167
Encroach Node=416820
       4      .7
Encroach Node=416323
       4      .7
Encroach Node=415842
       4      .7
Encroach Node=415123
       4      .7
Encroach Node=414039
       4      .7
Encroach Node=413015
       4      .7
Encroach Node=412105
       4      .7
Encroach Node=411294
       4      .7
Encroach Node=410460
       4      .7
Encroach Node=409894
       4      .7
Encroach Node=409319
       4      .7
Encroach Node=408756
       4      .7
Encroach Node=408058
       4      .7
Encroach Node=407379
       4      .7
Encroach Node=406555
       1    4793  5120.9
Encroach Node=406440
       1  4774.5  5198.4
Encroach Node=405921
       4      .7
Encroach Node=405422
       4      .7
Encroach Node=404748
       4      .7
Encroach Node=403949
       4      .7
Encroach Node=402820
       4      .7
Encroach Node=401720
       4      .7
Encroach Node=400839
       4      .7
Encroach Node=400081
       4      .7
Encroach Node=399188
       4      .7
Encroach Node=398346
       4      .7
Encroach Node=397169
       4      .7
Encroach Node=396036
       4      .7
Encroach Node=394997
       4      .7
Encroach Node=394532
       4      .7
Encroach Node=393666
       4      .7
Encroach Node=392244
       4      .7
Encroach Node=391289
       4      .7
Encroach Node=389646
       4      .7
Encroach Node=388538
       4      .7
Encroach Node=386539
       4      .7
Encroach Node=385386
       4      .7
Encroach Node=384257
       4      .7
Encroach Node=383730
       1  4901.5    5265
Encroach Node=383577
       1    4778    5222
Encroach Node=382682
       4      .7
Encroach Node=381417
       4      .7
Encroach Node=380248
       4      .7
Encroach Node=378915
       4      .7
Encroach Node=377544
       4      .7
Encroach Node=376303
       4      .7
Encroach Node=374785
       4      .7
Encroach Node=373520
       4      .7
Encroach Node=372725
       4      .7
Encroach Node=371296
       4      .7
Encroach Node=370406
       4      .7
Encroach Node=369119
       4      .7
Encroach Node=368239
       4      .7
Encroach Node=367026
       4      .7
Encroach Node=365954
       4      .7
Encroach Node=365042
       4      .7
Encroach Node=364000
       4      .7
Encroach Node=362796
       4      .7
Encroach Node=361395
       4      .7
Encroach Node=360733
       4      .7
Encroach Node=359991
       4      .7
Encroach Node=359058
       4      .7
Encroach Node=357572
       4      .7
Encroach Node=356718
       4      .7
Encroach Node=355400
       4      .7
Encroach Node=354450
       4      .7
Encroach Node=353213
       4      .7
Encroach Node=352223
       4      .7
Encroach Node=351164
       4      .7
Encroach Node=350129
       4      .7
Encroach Node=349050
       4      .7
Encroach Node=347672
       4      .7
Encroach Node=346401
       4      .7
Encroach Node=345087
       4      .7
Encroach Node=342838
       4      .7
Encroach Node=340985
       4      .7
Encroach Node=339183
       4      .7
Encroach Node=336918
       1  4920.2  5214.5
Encroach Node=336677
       1  4834.3  5181.2
Encroach Node=334859
       4      .7
Encroach Node=331391
       4      .7
Encroach Node=329278
       1 4921.33  7082.7
Encroach Node=327799
       4      .7
Encroach Node=326382
       4      .7
Encroach Node=325429
       4      .7
Encroach Node=324559
       4      .7
Encroach Node=323826
       4      .7
Encroach Node=322784
       4      .7
Encroach Node=320926
       4      .7
Encroach Node=319426
       4      .7
Encroach Node=318554
       1    4500    5300
Encroach Node=318440
       1    4500    5300
Encroach Node=317535
       4      .7
Encroach Node=315908
       4      .7
Encroach Node=314823
       4      .7
Encroach Node=313351
       4      .7
Encroach Node=311574
       4      .7
Encroach Node=310633
       1    4739    5261
Encroach Node=310503
       1  4780.4  5217.1
Encroach Node=308897
       4      .3
Encroach Node=307504
       4      .3
Encroach Node=306300
       4      .4
Encroach Node=305452
       4      .7
Encroach Node=304509
       4      .7
Encroach Node=303061
       4      .7
Encroach Node=301931
       4      .7
Encroach Node=300857
       4      .7
Encroach Node=299894
       4      .7
Encroach Node=298009
       4      .7
Encroach Node=297343
       4      .7
Encroach Node=296814
       4      .7
Encroach Node=295674
       4      .7
Encroach Node=294427
       4      .7
Encroach Node=293189
       4      .7
Encroach Node=291879
       4      .7
Encroach Node=291301
       4      .7
Encroach Node=290691
       4      .7
Encroach Node=290039
       4      .7
Encroach Node=288772
       4      .7
Encroach Node=287244
       4      .7
Encroach Node=285689
       4      .7
Encroach Node=284736
       4      .7
Encroach Node=283249
       4      .7
Encroach Node=282154
       1  4888.7  5698.1
Encroach Node=281083
       4      .7
Encroach Node=279422
       4      .7
Encroach Node=278352
       4      .7
Encroach Node=277574
       4      .7
Encroach Node=276546
       4      .8
BEGIN DESCRIPTION:
Floodway Run
END DESCRIPTION:
Computation Interval=1HOUR
Output Interval=1HOUR
Run HTab= 0
Run UNet= 0
Run PostProcess= 0
UNET Theta= 1
UNET Theta Warmup= 1
UNET ZTol= 0.02
UNET ZSATol= 0.05
UNET MxIter= 20
UNET MaxInSteps= 0
UNET DtIC= 0
UNET DtMin= 0
UNET MaxCRTS= 20
UNET WFStab= 2
UNET SFStab= 1
UNET WFX= 1
UNET SFX= 1
UNET DSS MLevel= 4
UNET DZMax Abort= 100
UNET Convert EG Bridges=-1
UNET Use Existing IB Tables=-1
UNET Froude Reduction=False
UNET Froude Limit= 1
UNET Froude Power= 10
Instantaneous Interval=1HOUR
Write IC File= 0
Echo Input=False
Echo Output=False
Write Detailed= 0
Detailed Automatic Start=False, 10

--- lds_dan_rvr_bctfud_lower.p01 (plan) ---

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Plan Title=Floodway Run
Short Identifier=Floodway
Geom File=g01
Flow File=f01

--- lds_dan_rvr_bctfud_lower.f01 (steady flow) ---

Flow Title=Floodway
Program Version=3.12
Number of Profiles= 2
Profile Names=100-year,100-FW
River Rch & RM=Dan River,Reach-1         ,441224
   23262   23262
River Rch & RM=Dan River,Reach-1         ,438627
   23290   23290
River Rch & RM=Dan River,Reach-1         ,434991
   23320   23320
River Rch & RM=Dan River,Reach-1         ,431751
   23445   23445
River Rch & RM=Dan River,Reach-1         ,428988
   23878   23878
River Rch & RM=Dan River,Reach-1         ,423864
   23937   23937
River Rch & RM=Dan River,Reach-1         ,422621
   23945   23945
River Rch & RM=Dan River,Reach-1         ,420480
   24049   24049
River Rch & RM=Dan River,Reach-1         ,417732
   24296   24296
River Rch & RM=Dan River,Reach-1         ,414039
   24405   24405
River Rch & RM=Dan River,Reach-1         ,411294
   24494   24494
River Rch & RM=Dan River,Reach-1         ,406555
   24544   24544
River Rch & RM=Dan River,Reach-1         ,405921
   24801   24801
River Rch & RM=Dan River,Reach-1         ,400081
   24839   24839
River Rch & RM=Dan River,Reach-1         ,399188
   25241   25241
River Rch & RM=Dan River,Reach-1         ,394532
   25303   25303
River Rch & RM=Dan River,Reach-1         ,389646
   25366   25366
River Rch & RM=Dan River,Reach-1         ,386539
   25420   25420
River Rch & RM=Dan River,Reach-1         ,384257
   27816   27816
River Rch & RM=Dan River,Reach-1         ,381417
   27942   27942
River Rch & RM=Dan River,Reach-1         ,377544
   27978   27978
River Rch & RM=Dan River,Reach-1         ,376303
   28002   28002
River Rch & RM=Dan River,Reach-1         ,374785
   28179   28179
River Rch & RM=Dan River,Reach-1         ,372725
   28230   28230
River Rch & RM=Dan River,Reach-1         ,365954
   28256   28256
River Rch & RM=Dan River,Reach-1         ,365042
   28282   28282
River Rch & RM=Dan River,Reach-1         ,361395
   28293   28293
River Rch & RM=Dan River,Reach-1         ,357572
   28507   28507
River Rch & RM=Dan River,Reach-1         ,353213
   28533   28533
River Rch & RM=Dan River,Reach-1         ,352223
   28546   28546
River Rch & RM=Dan River,Reach-1         ,350129
   28649   28649
River Rch & RM=Dan River,Reach-1         ,345087
   28682   28682
River Rch & RM=Dan River,Reach-1         ,342838
   28737   28737
River Rch & RM=Dan River,Reach-1         ,340985
   28815   28815
River Rch & RM=Dan River,Reach-1         ,336918
   28859   28859
River Rch & RM=Dan River,Reach-1         ,331391
   29168   29168
River Rch & RM=Dan River,Reach-1         ,326382
   29194   29194
River Rch & RM=Dan River,Reach-1         ,324559
   35756   35756
River Rch & RM=Dan River,Reach-1         ,320926
   35833   35833
River Rch & RM=Dan River,Reach-1         ,317535
   35853   35853
River Rch & RM=Dan River,Reach-1         ,314823
   35877   35877
River Rch & RM=Dan River,Reach-1         ,313351
   35892   35892
River Rch & RM=Dan River,Reach-1         ,311574
   35937   35937
River Rch & RM=Dan River,Reach-1         ,307504
   35955   35955
River Rch & RM=Dan River,Reach-1         ,305452
   35969   35969
River Rch & RM=Dan River,Reach-1         ,303061
   36265   36265
River Rch & RM=Dan River,Reach-1         ,301931
   38952   38952
River Rch & RM=Dan River,Reach-1         ,298009
   38982   38982
River Rch & RM=Dan River,Reach-1         ,297343
   39058   39058
River Rch & RM=Dan River,Reach-1         ,290039
   39078   39078
River Rch & RM=Dan River,Reach-1         ,284736
   39121   39121
River Rch & RM=Dan River,Reach-1         ,282154
   39145   39145
River Rch & RM=Dan River,Reach-1         ,279422
   39158   39158
River Rch & RM=Dan River,Reach-1         ,278352
   39167   39167
River Rch & RM=Dan River,Reach-1         ,277574
   39179   39179
Boundary for River Rch & Prof#=Dan River,Reach-1         , 1
Up Type= 0
Dn Type= 1
Dn Known WS=583.81
Boundary for River Rch & Prof#=Dan River,Reach-1         , 2
Up Type= 0
Dn Type= 1
Dn Known WS=584.61
DSS Import GetInterval= 0
DSS Import GetPeak= 0
DSS Import FillOption= 0

--- lds_dan_rvr_bctfud_lower.g02 (geometry) ---

Geom Title=Existing Conditions REV 3/16/06
Program Version=3.12

River Reach=Dan River       ,Reach-1
Reach XY= 30
      1580530.93      1022140.02      1585703.88      1016998.06
       1591713.6      1015819.18      1592508.38       1019330.5
      1597903.63      1010748.19      1609271.63      1013522.13
      1616520.74      1009580.38      1623851.13       996212.13
      1619770.13       976208.56      1623471.13       981694.38
        1628775.       977301.94      1636180.38       979717.75
      1637912.63       975598.75        1644269.       976809.31
       1651027.5       967060.06      1664789.25       967183.31
        1671445.        963087.5      1670736.25       956829.06
      1666707.13       957750.94      1667576.63       952367.88
      1680849.38       936094.56        1679614.       930549.44
      1693301.63       938004.19        1695500.       945971.75
      1699568.88       944883.75        1698325.       948791.44
      1706980.25       956748.06      1710830.13       954639.31
      1719839.75       962204.19      1723995.37       960485.23

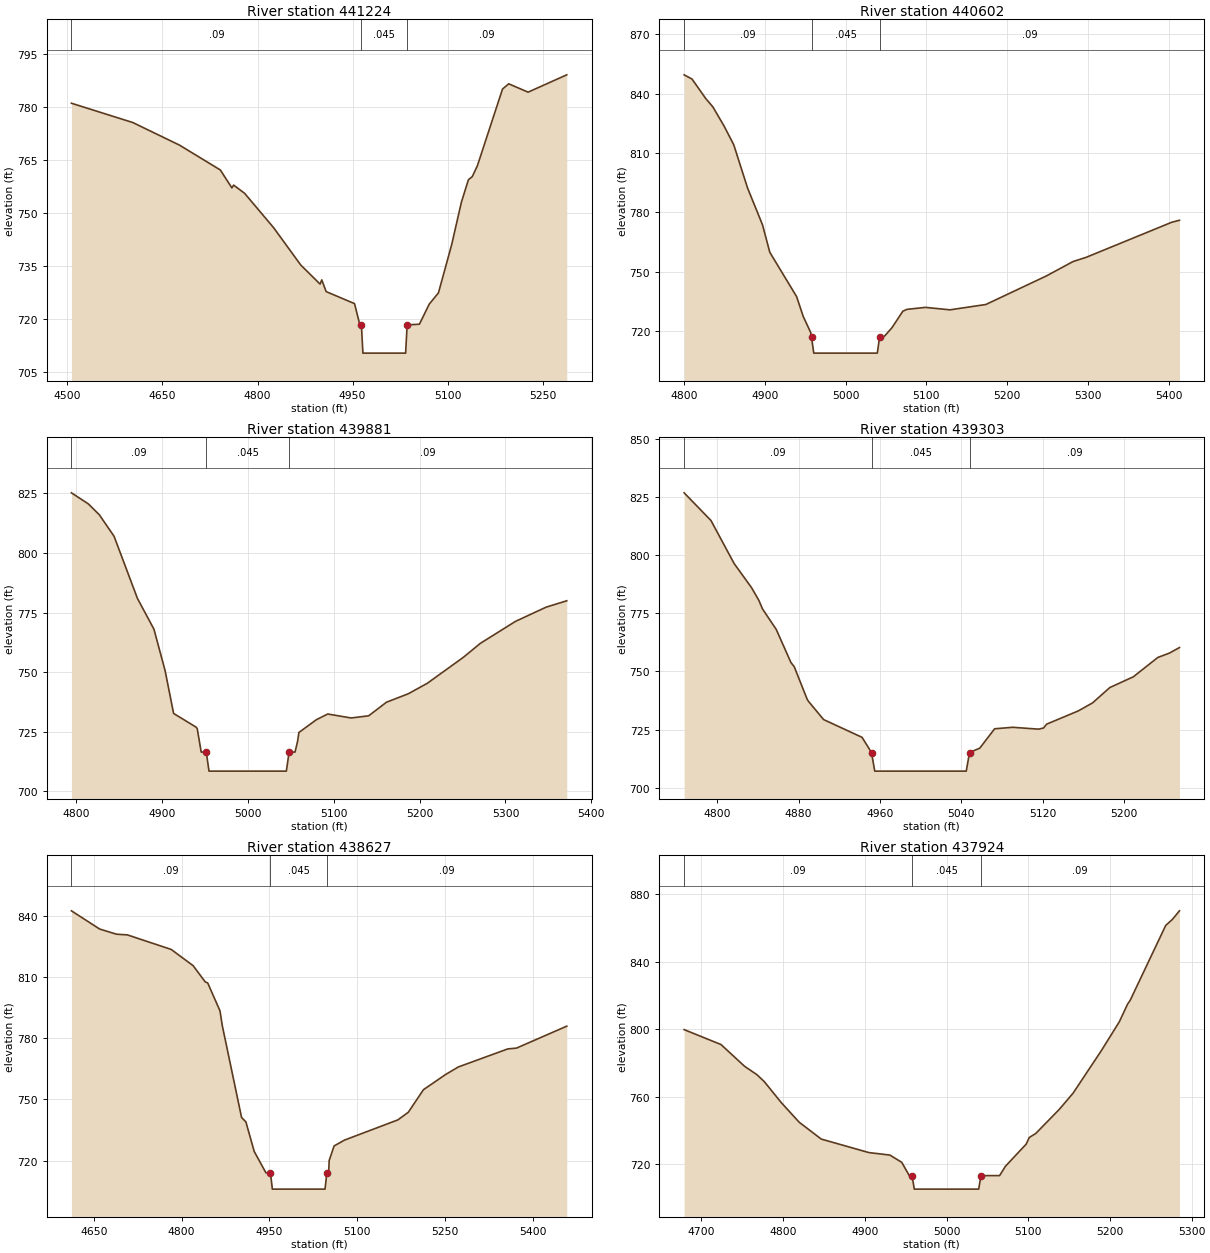
Type RM Length L Ch R = 1 ,441224  ,622,622,622
BEGIN DESCRIPTION:
Dan River 159.0
END DESCRIPTION:
XS GIS Cut Line= 5
      1625268.75       978941.95      1625420.96       978949.56
      1625531.31       978949.56      1625881.39        979052.3
      1626034.42       979070.39
#Sta/Elev= 30
  4506.3  781.12  4603.1  775.65  4676.8  769.25  4741.3   762.2  4759.5  757.12
  4762.3  757.91  4779.6  755.58  4825.6  745.79  4868.2  735.26  4898.7  729.85
  4901.4  731.04  4908.3  727.72  4953.1  724.31  4961.5  718.28  4963.9  718.28
  4966.3  710.28  5033.7  710.28  5036.1  718.28  5055.5  718.48  5070.9  724.15
  5085.5  727.36  5106.4  741.04  5121.7  753.06  5132.8  759.43  5138.9  760.32
  5146.9  763.37  5186.6  785.13  5196.4  786.62    5227  784.26    5288  789.17
#Mann= 3 ,-1 , 0
  4506.3     .09       0  4963.9    .045       0  5036.1     .09       0
Bank Sta=4963.9,5036.1
Exp/Cntr=0.3,0.1

Type RM Length L Ch R = 1 ,440602  ,721,721,721
BEGIN DESCRIPTION:
Dan River 158.0
END DESCRIPTION:
XS GIS Cut Line= 3
      1625844.89       979727.42      1625941.39       979554.04
      1626066.01       979158.84
#Sta/Elev= 30
  4800.3  849.57  4810.1  847.42  4827.1  837.55    4836  833.28  4849.9  823.53
  4861.7  814.19  4878.8  792.31  4897.3  773.68  4906.3  759.81  4939.5  737.37
  4947.7   727.3    4957  719.14  4957.3  716.96  4957.9   716.8  4960.7   708.8
  5039.3   708.8  5042.1   716.8  5046.6  716.91  5049.3  717.88  5057.5   721.7
  5070.9  730.02  5076.1  730.95    5099  731.94  5129.2   730.7  5173.6   733.4
  5248.5  747.85  5281.4  755.12  5297.4  757.21  5403.6     775  5413.1     776
#Mann= 3 ,-1 , 0
  4800.3     .09       0  4957.9    .045       0  5042.1     .09       0
Bank Sta=4957.9,5042.1
Exp/Cntr=0.3,0.1

Type RM Length L Ch R = 1 ,439881  ,578,578,578
BEGIN DESCRIPTION:
Dan River 157.0
END DESCRIPTION:
XS GIS Cut Line= 3
      1626688.29       979474.72      1626602.92       979293.01
      1626407.16       978972.47
#Sta/Elev= 30
  4794.9  825.21  4814.5  820.59  4827.4  815.99  4844.5     807  4871.7  780.93
  4890.9  768.03  4903.9  750.63  4913.8  732.67  4940.2  726.87  4941.3  726.29
  4945.9  716.47  4951.8  716.47    4955  708.47    5045  708.47  5048.2  716.47
  5055.1  716.47  5058.1  721.05  5059.6  724.69  5079.8     730  5093.1  732.43
  5120.4  730.77  5140.8  731.68  5161.5  737.38    5187  740.94    5209  745.31
  5250.8  756.17  5270.7  762.06  5311.7   771.3  5347.4  777.27  5371.3  779.93
#Mann= 3 ,-1 , 0
  4794.9     .09       0  4951.8    .045       0  5048.2     .09       0
Bank Sta=4951.8,5048.2
Exp/Cntr=0.3,0.1

Type RM Length L Ch R = 1 ,439303  ,676,676,676
BEGIN DESCRIPTION:
Dan River 156.0
END DESCRIPTION:
XS GIS Cut Line= 3
      1627282.15       979275.71      1627142.88       979089.18
      1627016.81       978868.23
#Sta/Elev= 30
  4767.5  826.87  4793.9  814.96  4816.8  796.37  4833.8  786.08  4841.1  780.53
  4844.6  776.92  4858.1   768.1  4872.6  753.82  4875.8  752.07  4888.5  738.07
  4889.9   737.1  4904.7  729.31  4942.5  721.67  4951.8  715.13    4955  707.13
    5045  707.13  5048.2  715.13  5058.3  717.02  5072.9  725.35  5090.7  725.99
  5116.2  725.19    5121  725.68  5124.1  727.35  5155.2  733.04  5169.3  736.51
  5186.2  743.09  5209.3  747.71  5233.4  756.03  5244.6  757.87  5254.7  760.29
#Mann= 3 ,-1 , 0
  4767.5     .09       0  4951.8    .045       0  5048.2     .09       0
Bank Sta=4951.8,5048.2
Exp/Cntr=0.3,0.1

Type RM Length L Ch R = 1 ,438627  ,703,703,703
BEGIN DESCRIPTION:
Dan River 155.0
END DESCRIPTION:
XS GIS Cut Line= 5
      1627882.32       978672.38      1627787.56       978634.47
      1627500.11        978571.3      1627237.93       978583.93
      1627054.72         978625.
#Sta/Elev= 30
  4611.6  842.37  4659.8  833.46  4688.6  830.93  4707.2  830.59  4782.1  823.47
  4819.6  815.52  4840.3  807.57  4844.5  807.07  4865.5  793.42  4869.5  786.09
  4902.4   741.2  4909.8  739.02    4924  724.56    4944  714.11  4951.8  714.11
    4955  706.11    5045  706.11  5048.2  714.11  5051.3  714.14  5052.1  720.09
  5060.5  727.24  5078.1  730.09  5169.5  740.01  5187.4  743.75  5213.3  754.81
  5250.8  762.17  5272.8  765.92  5357.3  774.75  5372.4  775.17  5458.2   785.9
#Mann= 3 ,-1 , 0
  4611.6     .09       0  4951.8    .045       0  5048.2     .09       0
Bank Sta=4951.8,5048.2
Exp/Cntr=0.3,0.1

Type RM Length L Ch R = 1 ,437924  ,1081,1081,1081
BEGIN DESCRIPTION:
Dan River 154.0
END DESCRIPTION:
XS GIS Cut Line= 3
      1628024.47       978097.48      1627757.93       977927.03
      1627528.54       977750.01
#Sta/Elev= 30
  4678.9  799.88    4724  791.04  4752.9  778.14    4768  773.16  4776.9  769.13
    4798   756.5  4819.7     745  4846.7  735.01    4905     727  4930.7  725.53
  4945.2  721.24  4954.5  713.34  4957.8  713.34  4960.6  705.34  5039.4  705.34
  5042.2  713.34    5065  713.35    5072  718.82  5097.5  732.01  5101.3  735.94
  5109.2  738.31  5137.9  752.54  5154.9  762.19  5189.6  787.49  5211.5  804.52
  5221.7  815.06  5224.7  817.15  5268.3  861.64  5276.4  865.17  5285.1  870.28
#Mann= 3 ,-1 , 0
  4678.9     .09       0  4957.8    .045       0  5042.2     .09       0
Bank Sta=4957.8,5042.2
Exp/Cntr=0.3,0.1

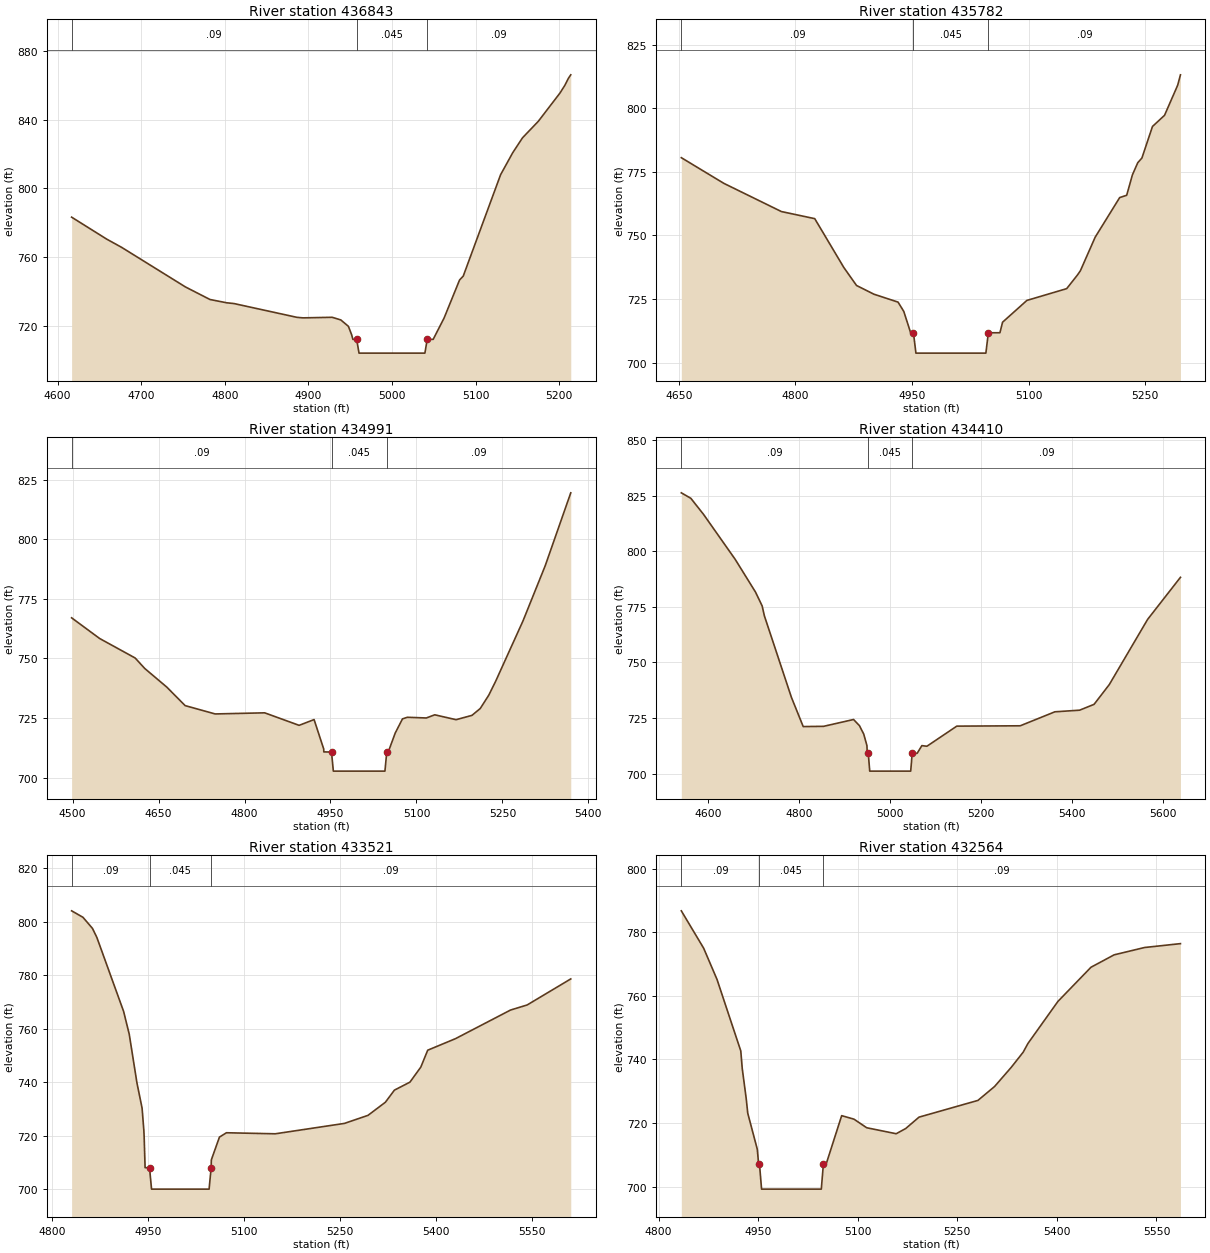
Type RM Length L Ch R = 1 ,436843  ,1061,1061,1061
BEGIN DESCRIPTION:
Dan River 152.0
END DESCRIPTION:
XS GIS Cut Line= 3
      1628722.57       977715.26      1628651.89       977344.16
      1628570.95       977140.35
#Sta/Elev= 30
  4616.8  783.29  4658.8   770.5  4676.7   765.7    4753  742.67  4782.3  735.38
  4802.3  733.46  4811.1  733.01  4886.4  724.99  4893.7  724.69  4928.5  725.02
  4938.8  723.49  4947.9  719.76  4951.7  714.98  4953.3  712.17  4957.8  712.17
  4960.6  704.17  5039.4  704.17  5042.2  712.17  5049.3  712.17  5062.4  724.63
  5080.9  746.74  5085.3  749.02    5130  808.03  5144.5  820.81  5156.2  829.48
  5175.1  839.08  5201.1  855.59  5206.9  860.06    5211  864.02  5213.9  866.12
#Mann= 3 ,-1 , 0
  4616.8     .09       0  4957.8    .045       0  5042.2     .09       0
Bank Sta=4957.8,5042.2
Exp/Cntr=0.3,0.1

Type RM Length L Ch R = 1 ,435782  ,791,791,791
BEGIN DESCRIPTION:
Dan River 150.0
END DESCRIPTION:
XS GIS Cut Line= 4
      1629528.07       977686.83      1629673.37       977427.81
      1629704.96       977358.31      1629749.18       977092.97
#Sta/Elev= 30
  4653.1  780.56  4707.8  770.47  4781.9  759.38  4824.8  756.59  4862.2   737.4
  4878.6  730.31  4900.9   726.9    4932  723.78  4939.4  720.11  4948.2  711.74
  4951.8  711.73    4955  703.73    5045  703.73  5048.2  711.73  5063.1  711.74
  5066.5  715.89  5097.8  724.45    5149  729.08    5163   734.5  5166.6   736.1
  5185.7  749.33  5217.2  764.88  5226.2  765.78  5233.6  773.83  5240.5   778.6
  5245.8  780.42  5259.4  792.83  5274.9  797.21  5291.8  809.03  5295.4  813.13
#Mann= 3 ,-1 , 0
  4653.1     .09       0  4951.8    .045       0  5048.2     .09       0
Bank Sta=4951.8,5048.2
Exp/Cntr=0.3,0.1

Type RM Length L Ch R = 1 ,434991  ,581,581,581
BEGIN DESCRIPTION:
Dan River 149.0
END DESCRIPTION:
XS GIS Cut Line= 4
      1630144.03       978027.98      1630432.68       977626.65
      1630526.25       977538.37      1630573.63       977295.14
#Sta/Elev= 30
  4498.4     767  4547.3  758.32  4609.2  750.15  4626.1  745.72  4664.3  737.96
  4696.5  730.16  4748.8  726.67  4835.2  727.14  4895.3  721.89  4921.4  724.31
  4938.2  711.96  4938.4  710.75  4951.8  710.68    4955  702.68    5045  702.68
  5048.2  710.68  5052.2  711.64  5062.9  718.62  5075.6   724.6  5084.1  725.27
  5117.2  724.98  5131.9  726.31  5169.1  724.26  5196.9  726.08  5211.3  728.96
  5226.1  734.52  5237.8  740.19  5285.9  765.72  5324.5  788.77  5369.2  819.44
#Mann= 3 ,-1 , 0
  4498.4     .09       0  4951.8    .045       0  5048.2     .09       0
Bank Sta=4951.8,5048.2
Exp/Cntr=0.3,0.1

Type RM Length L Ch R = 1 ,434410  ,889,889,889
BEGIN DESCRIPTION:
Dan River 148.0
END DESCRIPTION:
XS GIS Cut Line= 5
      1630422.01       978305.96      1630687.35       978189.08
      1630797.41       978073.64      1630962.17       977952.17
      1631066.41       977522.57
#Sta/Elev= 30
  4541.2  826.22  4562.1  823.76  4590.2  816.48  4659.5  796.32  4704.1  781.61
  4718.7  775.39  4723.7  770.87    4783  734.27  4808.9  721.12  4853.6  721.23
  4919.5   724.3  4932.4  721.54  4941.9   717.7  4948.8  712.62  4949.6  709.14
  4951.8  709.09    4955  701.09    5045  701.09  5048.2  709.09  5059.1  709.09
  5069.5  712.56  5080.6  712.28  5146.2  721.32  5285.5  721.47  5361.6  727.76
  5415.9  728.49  5447.7  731.12  5481.1     740  5565.3  769.32  5637.4  788.23
#Mann= 3 ,-1 , 0
  4541.2     .09       0  4951.8    .045       0  5048.2     .09       0
Bank Sta=4951.8,5048.2
Exp/Cntr=0.3,0.1

Type RM Length L Ch R = 1 ,433521  ,957,957,957
BEGIN DESCRIPTION:
Dan River 147.0
END DESCRIPTION:
XS GIS Cut Line= 4
      1631622.36        978394.4      1631605.56        978227.4
      1631587.61       978050.09      1631685.53       977626.81
#Sta/Elev= 30
    4830  804.02  4847.7  801.61  4862.6  797.46  4869.5  794.07  4911.3  766.45
  4920.1  757.94  4932.2  739.68  4940.2  730.31  4942.9  722.15  4943.4  719.82
  4944.9  708.06  4951.8  708.05    4955  700.05    5045  700.05  5048.2  708.05
  5048.5  710.98  5061.2  719.49  5072.1  721.11  5148.5  720.72  5256.6   724.6
  5293.5  727.61  5320.7  732.51  5334.8  737.03  5359.1  740.02  5376.1  745.64
  5386.9  751.95  5430.3  756.26  5516.4  766.95  5542.4  768.85  5610.6  778.58
#Mann= 3 ,-1 , 0
    4830     .09       0  4951.8    .045       0  5048.2     .09       0
Bank Sta=4951.8,5048.2
Exp/Cntr=0.3,0.1

Type RM Length L Ch R = 1 ,432564  ,813,813,813
BEGIN DESCRIPTION:
Dan River 146.0
END DESCRIPTION:
XS GIS Cut Line= 4
      1632582.64         978088.      1632510.25       977941.33
      1632412.06       977835.29      1632023.53       977620.49
#Sta/Elev= 30
  4834.1  786.72  4867.8  774.96  4887.9  765.15  4923.7  742.68  4925.9  737.15
  4931.8  727.84  4934.2  723.12  4948.6  711.75  4950.5  707.27  4951.8  707.26
    4955  699.26    5045  699.26  5048.2  707.26  5052.5  707.26  5075.7  722.35
  5094.2  721.25  5113.4  718.55  5157.8  716.67  5172.2  718.31  5192.2  721.88
    5281  727.14  5306.1  731.52  5331.4  737.59  5349.2  742.31  5356.4  745.06
  5401.5  758.25  5451.3  768.99  5486.2  772.89    5532  775.19  5586.1  776.41
#Mann= 3 ,-1 , 0
  4834.1     .09       0  4951.8    .045       0  5048.2     .09       0
Bank Sta=4951.8,5048.2
Exp/Cntr=0.3,0.1

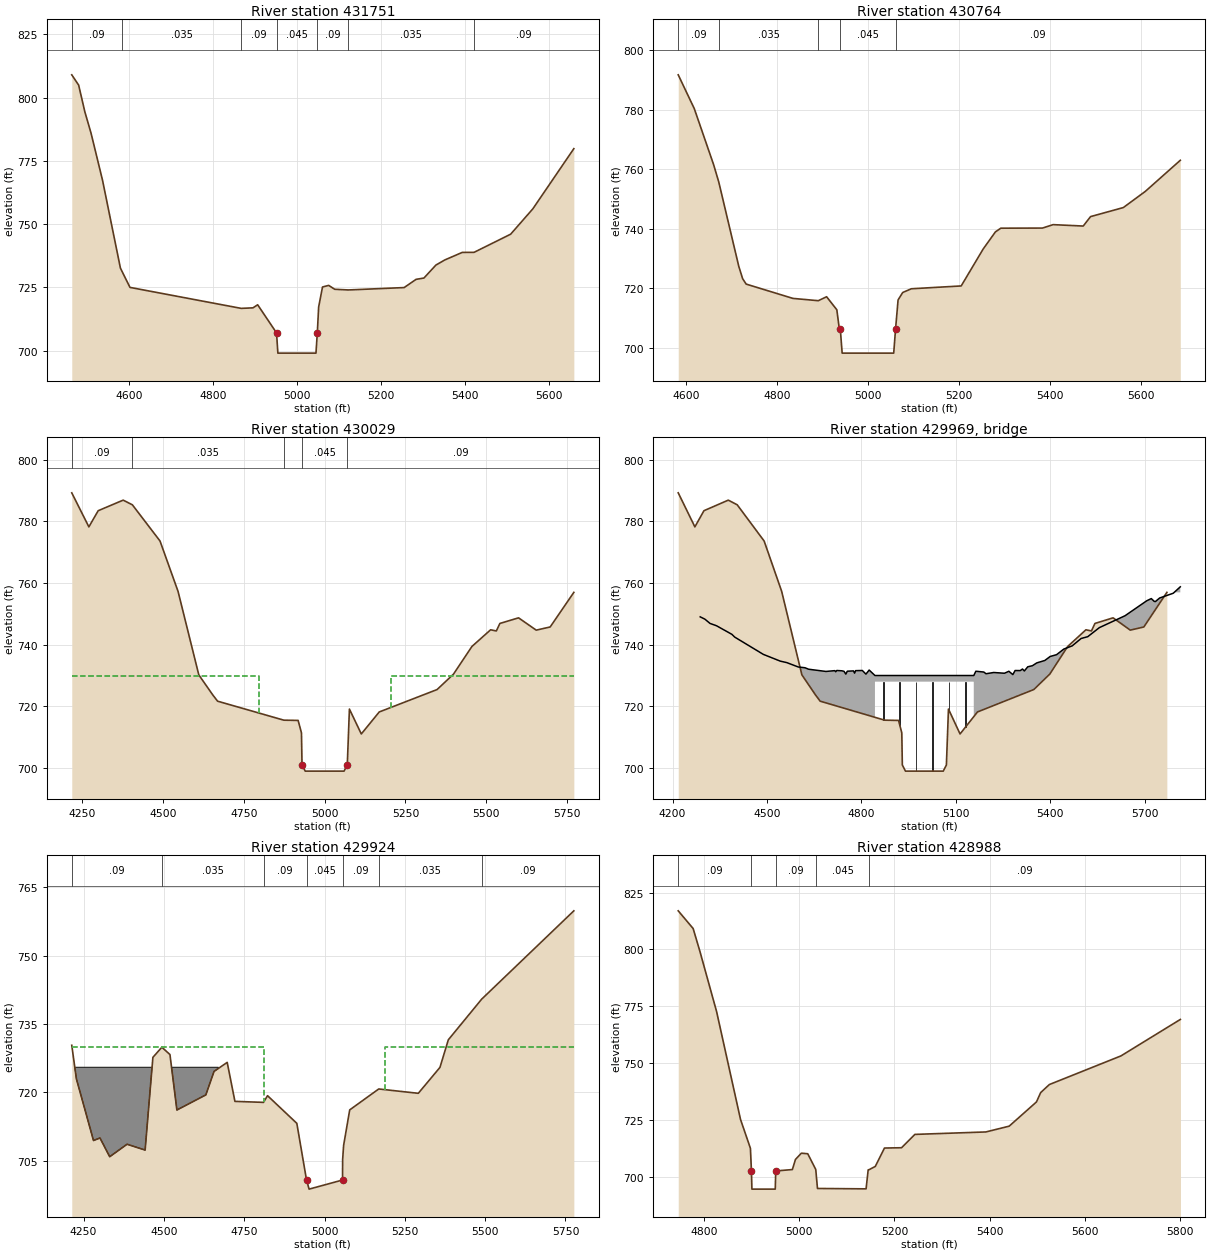
Type RM Length L Ch R = 1 ,431751  ,987,987,987
BEGIN DESCRIPTION:
Dan River 145.0
END DESCRIPTION:
XS GIS Cut Line= 4
      1633075.41       978138.54      1633233.35       977800.55
      1633252.31       977642.61      1633331.28       976982.41
#Sta/Elev= 30
  4463.2  808.99  4479.6  804.93  4494.4  794.37  4509.2  785.91  4536.5  767.37
  4579.2  732.63  4582.3  731.58    4602     725  4867.2  716.71  4895.2  716.92
  4906.4  718.13  4951.4  707.03  4954.6  699.03  5045.4  699.03  5048.6  707.03
  5051.8  717.25    5061  725.16  5075.7  725.79  5090.1  724.26  5122.5  723.99
  5255.6  724.93  5284.1  728.18  5302.8   728.7  5331.3  733.82  5352.7  735.86
  5394.2  738.83  5422.3  738.85  5509.6  746.03  5562.3  756.01  5660.2  779.82
#Mann= 7 ,-1 , 0
  4463.2     .09       0  4582.3    .035       0  4867.2     .09       0
  4951.4    .045       0  5048.6     .09       0  5122.5    .035       0
  5422.3     .09       0
Bank Sta=4951.4,5048.6
Exp/Cntr=0.3,0.1

Type RM Length L Ch R = 1 ,430764  ,735,735,735
BEGIN DESCRIPTION:
Dan River 143.0
END DESCRIPTION:
XS GIS Cut Line= 5
      1633637.68       978473.37      1633994.63       978258.57
      1634108.34       978185.92      1634282.08        978125.9
      1634588.48       977920.58
#Sta/Elev= 30
  4582.8  791.81  4618.1  780.45  4660.5  761.68    4672  755.76    4716  727.42
  4724.5  723.28  4732.2  721.48  4835.1  716.67  4890.9   715.9  4909.1  717.23
  4931.6  712.85  4937.2  706.29  4939.3  706.28  4943.3  698.28  5056.7  698.28
  5060.7  706.28  5066.3  716.16  5076.5  718.66  5095.5  719.91  5205.1  720.86
  5253.6  733.31  5280.4  739.03  5292.3  740.27  5383.9  740.31  5407.2  741.46
  5473.5  740.99  5489.6  744.16  5561.7   747.2    5610  752.63    5687  763.09
#Mann= 5 ,-1 , 0
  4582.8     .09       0    4672    .035       0  4890.9     .09       0
  4939.3    .045       0  5060.7     .09       0
Bank Sta=4939.3,5060.7
Exp/Cntr=0.5,0.3

Type RM Length L Ch R = 1 ,430029  ,105,105,105
BEGIN DESCRIPTION:
NC 8 & 89 HWYN - US
END DESCRIPTION:
XS GIS Cut Line= 6
      1633833.53       979335.73       1634019.9       979177.79
      1634177.84       979064.07       1634648.5       978675.54
      1634774.85       978479.69      1634806.44       978211.19
#Sta/Elev= 30
  4217.9  789.23  4270.8  778.19  4299.6  783.43  4376.9  786.86  4405.4  785.34
  4490.9   773.6  4546.6  757.28  4610.8  730.21  4653.7  723.75  4668.9  721.68
  4873.8  715.52    4918  715.44  4928.3   711.4    4930     701    4940     699
    5060     699    5070     701  5076.6  719.12  5113.4  711.05  5168.8  718.18
  5347.8  725.45  5398.5  730.45  5455.4  739.41  5513.3  744.82    5531  744.45
    5542  746.88  5599.7   748.7  5654.3  744.71  5697.5  745.74  5770.7  756.96
#Mann= 5 ,-1 , 0
  4217.9     .09       0  4405.4    .035       0  4873.8     .09       0
    4930    .045       0    5070     .09       0
#XS Ineff= 2 , 0
       0    4796     730    5204       0     730
Permanent Ineff=
       F       F
Bank Sta=4930,5070
Exp/Cntr=0.5,0.3

Type RM Length L Ch R = 3 ,429969  ,,,
BEGIN DESCRIPTION:
NC 8 & 89 HWYN
Structure ID: NC 8 & 89 HWYN
Approximate Survey Structure
END DESCRIPTION:
Bridge Culvert--1,0,-1,-1, 0
Deck Dist Width WeirC Skew NumUp NumDn MinLoCord MaxHiCord MaxSubmerge Is_Ogee
47,28,3,0, 60, 60, , , , 0, 0.5,0.5,,
  4287.7  4302.7  4318.8  4339.4  4388.5  4397.6  4488.3  4542.2  4562.9  4599.4
  4620.7  4632.2  4687.1  4715.5  4718.2  4721.5  4737.9  4744.7  4750.4  4755.1
  4774.6  4778.3  4781.4  4802.9  4814.3  4824.6    4843    4843    5157    5157
  5163.6  5188.8  5195.8  5220.4  5254.6  5268.5  5281.1  5288.3  5304.6  5311.8
  5317.6  5328.6  5343.3  5357.3  5382.8  5399.7  5420.1  5443.2  5469.7    5498
  5519.2  5556.1  5637.6  5706.7  5721.1  5730.4  5734.1  5747.7  5790.8  5813.3
  749.02  748.26  746.89  746.14  743.34  742.44  736.85  734.66  734.18  732.76
  732.52  732.04  731.32  731.58  731.22  731.63  731.53  731.36  730.45   731.4
   731.5  730.77  731.58  731.63  730.45  731.77     730     730     730     730
  731.39  731.13  730.58  730.98  730.74  731.38   730.3  731.62   731.6  732.11
  731.47  732.83  733.18   734.1  734.88  736.17  736.76  738.58  739.61     742
  742.59  745.53  749.38  754.24  754.94  754.04  753.98  755.14  756.67  758.76
     679     679     679     679     679     679     679     679     679     679
     679     679     679     679     679     679     679     679     679     679
     679     679     679     679     679     679     679     728     728     679
     679     679     679     679     679     679     679     679     679     679
     679     679     679     679     679     679     679     679     679     679
     679     679     679     679     679     679     679     679     679     679
  4287.7  4302.7  4318.8  4339.4  4388.5  4397.6  4488.3  4542.2  4562.9  4599.4
  4620.7  4632.2  4687.1  4715.5  4718.2  4721.5  4737.9  4744.7  4750.4  4755.1
  4774.6  4778.3  4781.4  4802.9  4814.3  4824.6    4843    4843    5157    5157
  5163.6  5188.8  5195.8  5220.4  5254.6  5268.5  5281.1  5288.3  5304.6  5311.8
  5317.6  5328.6  5343.3  5357.3  5382.8  5399.7  5420.1  5443.2  5469.7    5498
  5519.2  5556.1  5637.6  5706.7  5721.1  5730.4  5734.1  5747.7  5790.8  5813.3
  749.02  748.26  746.89  746.14  743.34  742.44  736.85  734.66  734.18  732.76
  732.52  732.04  731.32  731.58  731.22  731.63  731.53  731.36  730.45   731.4
   731.5  730.77  731.58  731.63  730.45  731.77     730     730     730     730
  731.39  731.13  730.58  730.98  730.74  731.38   730.3  731.62   731.6  732.11
  731.47  732.83  733.18   734.1  734.88  736.17  736.76  738.58  739.61     742
  742.59  745.53  749.38  754.24  754.94  754.04  753.98  755.14  756.67  758.76
     679     679     679     679     679     679     679     679     679     679
     679     679     679     679     679     679     679     679     679     679
     679     679     679     679     679     679     679     728     728     679
     679     679     679     679     679     679     679     679     679     679
     679     679     679     679     679     679     679     679     679     679
     679     679     679     679     679     679     679     679     679     679
Pier Skew, UpSta & Num, DnSta & Num=  ,4869.2, 2 ,4869.2, 2 , 0 , 0 , 0 ,0,0
       2       2
  715.65     728
       2       2
  715.24     728
Pier Skew, UpSta & Num, DnSta & Num=  ,4921.5, 2 ,4921.5, 2 , 0 , 0 , 0 ,0,0
       2       2
  714.07     728
       2       2
   709.9     728
Pier Skew, UpSta & Num, DnSta & Num=  ,4973.8, 2 ,4973.8, 2 , 0 , 0 , 0 ,0,0
       2       2
     699     728
       2       2
  698.75     728
Pier Skew, UpSta & Num, DnSta & Num=  ,5026.2, 2 ,5026.2, 2 , 0 , 0 , 0 ,0,0
       2       2
     699     728
       2       2
  698.75     728
Pier Skew, UpSta & Num, DnSta & Num=  ,5078.5, 2 ,5078.5, 2 , 0 , 0 , 0 ,0,0
       2       2
  718.84     728
       2       2
  716.15     728
Pier Skew, UpSta & Num, DnSta & Num=  ,5130.8, 2 ,5130.8, 2 , 0 , 0 , 0 ,0,0
       2       2
  713.76     728
       2       2
  719.21     728
Abutment Skew #Up #Dn= , 2 , 2
    4843  4877.5
     728  715.34
    4843  4877.5
     728   714.7
Abutment Skew #Up #Dn= , 2 , 2
  5122.5    5157
  712.44     728
  5122.5    5157
  718.76     728
BR Coef= 1 , 1 , 0 ,1.25, 0 ,,,0.8,0,2,0,
WSPro=,,,, 1 ,,,, 0 ,,,, 0 ,,,,-1 ,-1 ,-1 , 0 , 0 , 0 , 0 , 0
BC Design=,, 0 ,, 0 ,,,,,,
BC HTab HWMax=789.24

Type RM Length L Ch R = 1 ,429924  ,936,936,936
BEGIN DESCRIPTION:
NC 8 & 89 HWYN - DS
END DESCRIPTION:
XS GIS Cut Line= 6
      1633899.86       979417.86      1634177.84       979256.76
      1634228.38       979155.68      1634743.26       978719.76
      1634828.55       978621.84      1634920.16       978312.27
#Sta/Elev= 30
  4213.3  730.32  4227.7  722.95  4280.9  709.42  4301.1  709.97  4331.4  705.86
  4385.4   708.6  4441.6  707.32  4465.8  727.67  4493.7  729.89  4518.9  728.29
  4540.5  716.11  4630.6  719.43  4656.1  724.58  4697.1  726.57  4721.1  718.01
  4810.1  717.79  4822.6  719.26  4913.8  713.19    4944  700.75    4952  698.75
    5056  700.75  5056.4  705.22  5059.4  708.34  5078.4  716.14  5168.7  720.73
  5291.9  719.78  5359.3  725.47  5385.3  731.52  5489.2  740.45    5776  759.83
#Mann= 7 ,-1 , 0
  4213.3     .09       0  4493.7    .035       0  4810.1     .09       0
    4944    .045       0    5056     .09       0  5168.7    .035       0
  5489.2     .09       0
#XS Ineff= 2 , 0
       0    4811     730    5189       0     730
Permanent Ineff=
       F       F
#Block Obstruct= 1 ,-1
  4222.5  4669.4   725.5
Bank Sta=4944,5056
Exp/Cntr=0.5,0.3

Type RM Length L Ch R = 1 ,428988  ,928,928,928
BEGIN DESCRIPTION:
Dan River 141.0
END DESCRIPTION:
XS GIS Cut Line= 4
      1635021.24        979790.6      1635157.07       979566.32
      1635198.13       979518.94      1635841.96       979177.76
#Sta/Elev= 30
  4746.4  817.02  4777.7  809.22  4791.8  799.24  4826.9  772.68  4877.1   725.2
  4897.9  712.46    4900  702.51    4901  694.51    4950  694.51    4951  702.51
  4985.9  703.12  4992.4  707.58  5004.8  710.33  5018.2  710.08    5035  703.16
  5038.6   694.8  5140.6  694.63    5145  703.01    5147  703.08  5159.9   704.5
  5179.2   712.6  5215.1  712.73    5243   718.6    5392  719.68  5440.9  722.23
  5498.1  732.88    5507  737.01  5525.2  740.55  5675.5  753.16    5800   769.2
#Mann= 5 ,-1 , 0
  4746.4     .09       0    4900    .045       0    4951     .09       0
    5035    .045       0    5147     .09       0
Bank Sta=4900,4951
Exp/Cntr=0.3,0.1