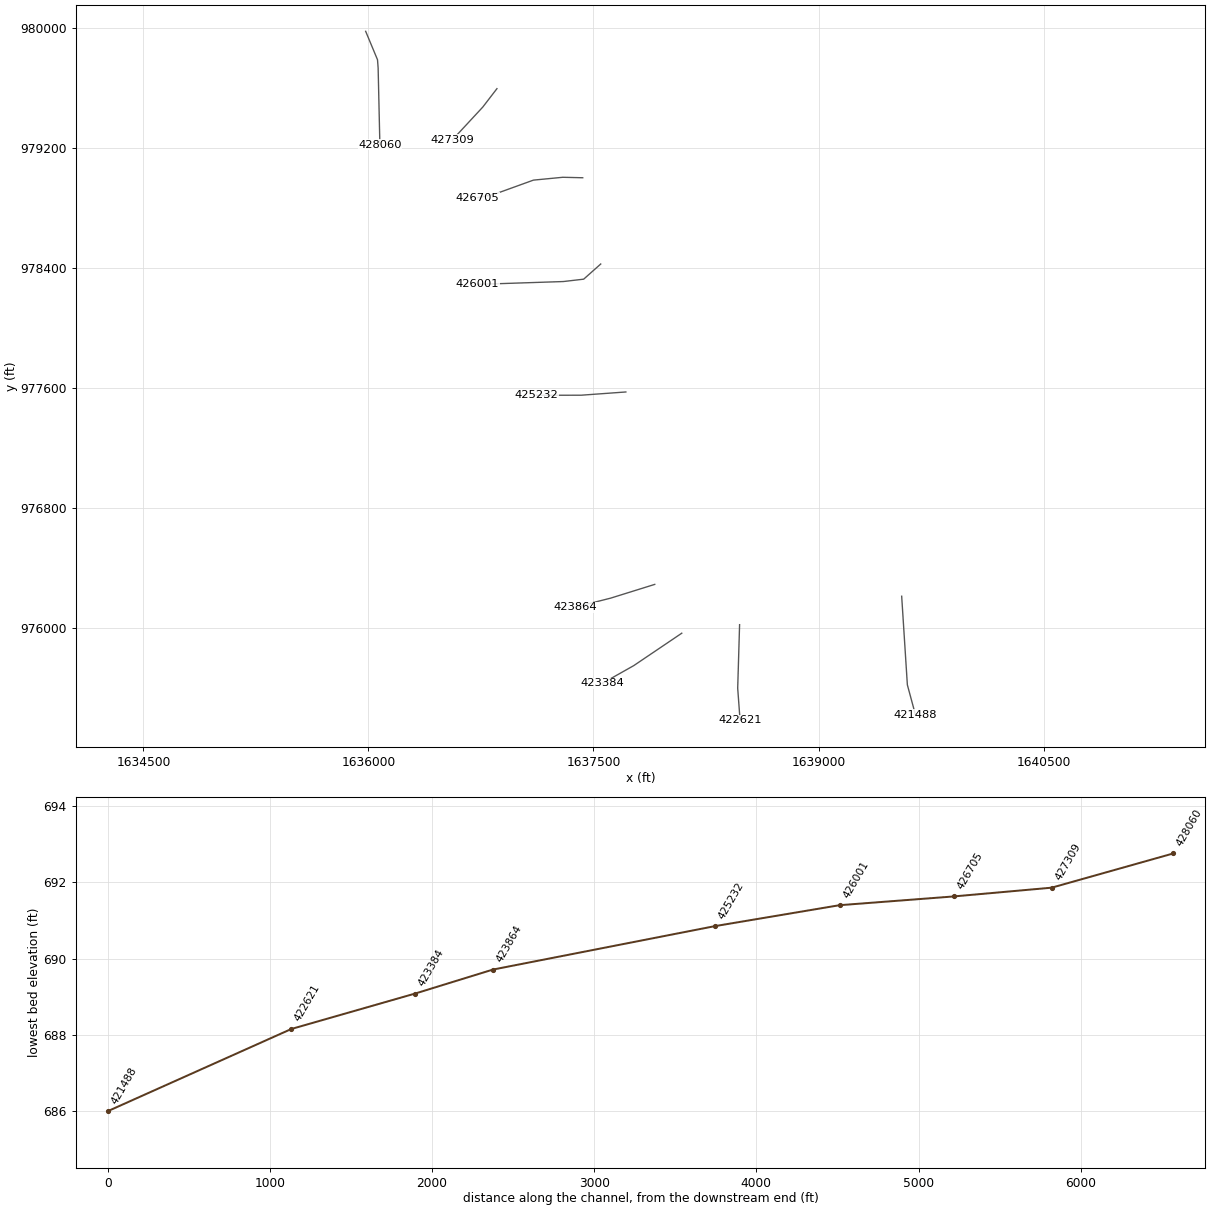
HEC-RAS study lds_dan_rvr_bctfud_lower.prj: Dan River Limited Detail Study Lower

--- lds_dan_rvr_bctfud_lower.g02 (geometry) --- (continued)

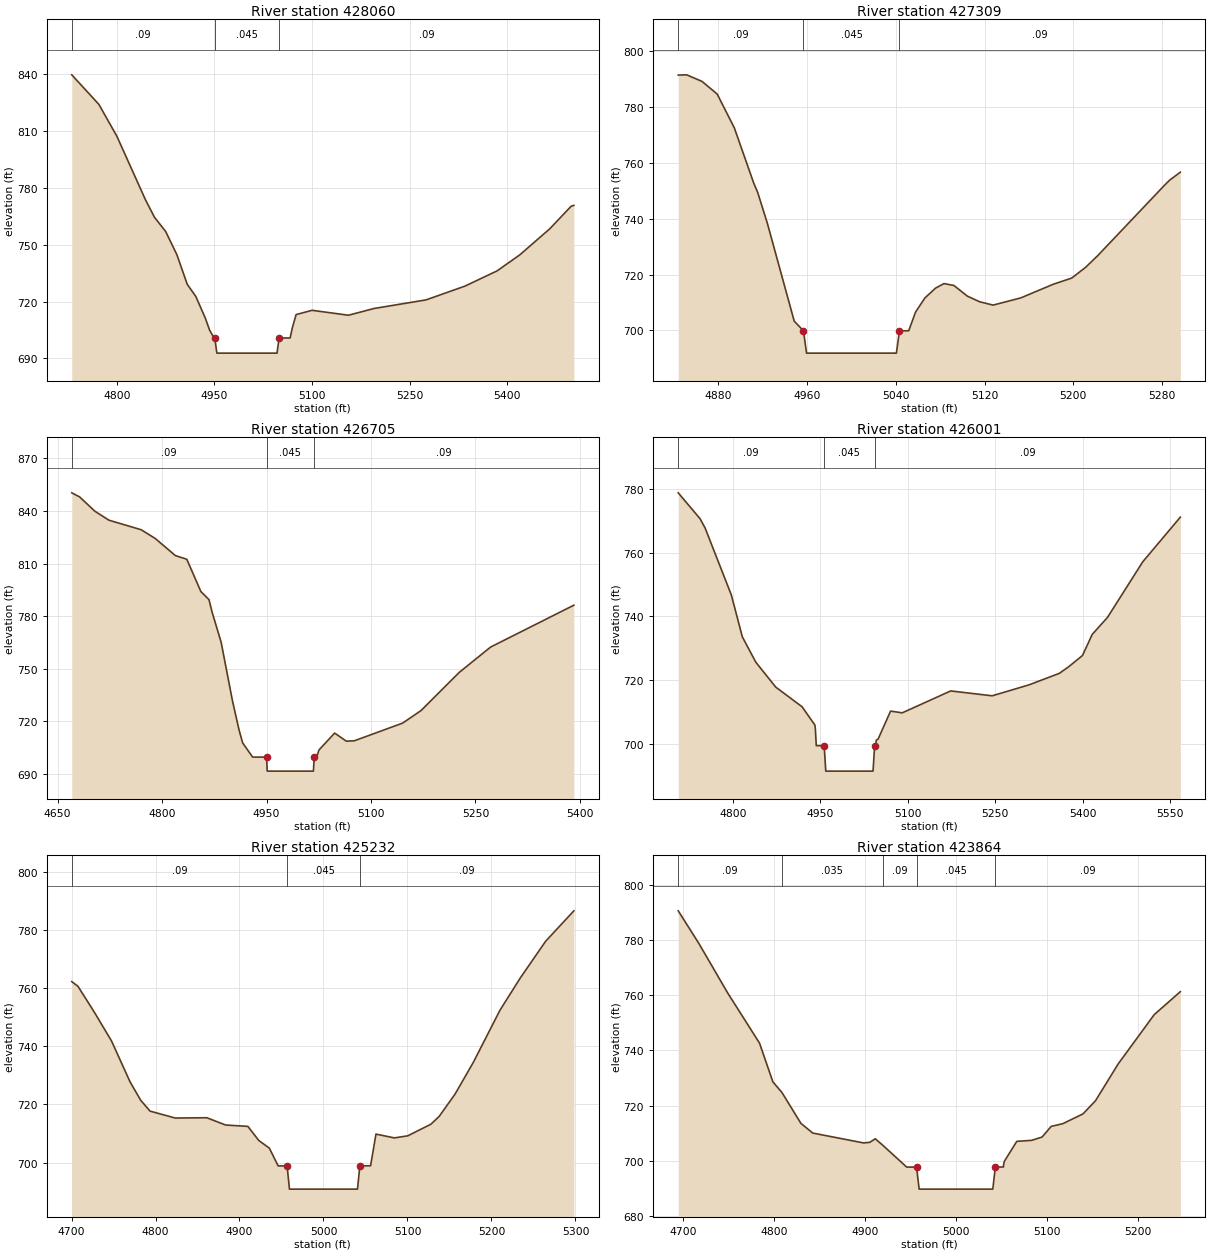
Type RM Length L Ch R = 1 ,428060  ,751,751,751
BEGIN DESCRIPTION:
Dan River 140.0
END DESCRIPTION:
XS GIS Cut Line= 4
      1635981.52       979976.97      1636060.49       979787.44
      1636064.66       979732.84      1636076.28       979222.01
#Sta/Elev= 30
    4731  839.63  4772.6  824.05  4800.3  807.21  4844.3  773.61    4858  764.47
  4875.2  756.96  4892.4  744.73  4908.4  729.04  4921.5  722.67  4936.3  711.06
  4942.5  705.02  4947.9  701.73  4948.1  700.77  4950.6  700.76  4953.8  692.76
  5046.2  692.76  5049.4  700.76  5066.3  700.76    5070  706.49  5075.5   713.1
    5100  715.36  5155.9  712.76  5195.2  716.32    5275  720.85  5334.9  728.14
  5384.1  736.16  5419.2  744.67  5465.1   758.4  5497.9   770.3    5502  770.75
#Mann= 3 ,-1 , 0
    4731     .09       0  4950.6    .045       0  5049.4     .09       0
Bank Sta=4950.6,5049.4
Exp/Cntr=0.3,0.1

Type RM Length L Ch R = 1 ,427309  ,604,604,604
BEGIN DESCRIPTION:
Dan River 139.0
END DESCRIPTION:
XS GIS Cut Line= 3
      1636856.51       979594.75      1636761.75       979471.56
      1636559.58        979253.6
#Sta/Elev= 30
  4843.8  791.48  4851.4  791.56  4865.2  789.22  4878.9  784.69  4894.4  772.54
  4911.9  752.75  4915.5  749.36  4924.2  738.32  4948.4  703.31  4956.7  699.86
  4959.5  691.86  5040.5  691.86  5043.3  699.86  5051.6  699.86  5057.8  706.58
  5066.2  711.62  5075.8  715.14  5083.4  716.78  5092.4  716.09  5104.4   712.3
  5115.5  710.27  5127.7  709.06  5152.7  711.65    5182  716.54  5198.6  718.75
  5211.1  722.59    5222  726.77  5281.8  751.81  5286.9  753.83  5296.5  756.68
#Mann= 3 ,-1 , 0
  4843.8     .09       0  4956.7    .045       0  5043.3     .09       0
Bank Sta=4956.7,5043.3
Exp/Cntr=0.3,0.1

Type RM Length L Ch R = 1 ,426705  ,704,704,704
BEGIN DESCRIPTION:
Dan River 138.0
END DESCRIPTION:
XS GIS Cut Line= 5
      1637428.26        979000.9      1637295.59       979004.05
      1637099.74        978985.1      1636837.56       978890.34
        1636727.       978868.23
#Sta/Elev= 30
  4670.3  850.31  4681.5     848  4703.6   839.8  4723.6  834.72    4770  829.26
  4790.2  824.27    4819  814.55  4835.5  812.43  4855.7  794.03  4867.4   789.4
  4871.6  782.58  4884.8  765.13  4901.2  731.49  4910.6     715  4915.7  707.74
    4930  699.63    4950  699.63    4951  691.63  5017.3  691.63  5018.5  699.63
  5022.2  699.83  5025.2  703.64  5047.8  713.33  5064.6  708.71  5076.2  708.94
  5145.4  719.01  5171.8  726.14  5226.6  747.88  5271.8  762.38  5391.3  786.24
#Mann= 3 ,-1 , 0
  4670.3     .09       0    4950    .045       0  5018.5     .09       0
Bank Sta=4950,5018.5
Exp/Cntr=0.3,0.1

Type RM Length L Ch R = 1 ,426001  ,769,769,769
BEGIN DESCRIPTION:
Dan River 137.0
END DESCRIPTION:
XS GIS Cut Line= 4
      1637548.29       978425.99      1637434.57       978324.91
      1637298.74       978309.12        1636727.       978290.16
#Sta/Elev= 30
  4706.5  778.82  4744.1  770.65  4752.7  767.72  4797.6  746.72  4816.4  733.59
  4839.6   725.6  4873.8  717.77  4918.8  711.63  4940.8  705.88  4941.6  704.78
  4943.2  699.41  4956.7   699.4  4959.5   691.4  5040.5   691.4  5043.3   699.4
  5045.2   699.4  5046.1  701.14  5049.2  701.46  5070.6  710.26  5090.6  709.71
  5173.7  716.59  5244.8  715.06  5308.2  718.51    5360  722.12    5376  724.19
  5399.6  727.71  5416.4  734.35  5442.7  739.73    5503  757.15  5567.4  771.17
#Mann= 3 ,-1 , 0
  4706.5     .09       0  4956.7    .045       0  5043.3     .09       0
Bank Sta=4956.7,5043.3
Exp/Cntr=0.3,0.1

Type RM Length L Ch R = 1 ,425232  ,1368,1368,1368
BEGIN DESCRIPTION:
Dan River 136.0
END DESCRIPTION:
XS GIS Cut Line= 3
      1637715.71       977573.11      1637418.13       977551.56
      1637118.69         977551.
#Sta/Elev= 30
  4700.3  762.26  4707.6  760.69  4727.3  751.69  4747.6  741.86  4769.8  727.71
  4782.3  721.47  4793.5   717.7  4823.6  715.31  4861.1  715.42  4883.4  712.92
    4910  712.44    4923  707.59  4935.6  704.94    4946  698.85  4956.7  698.85
  4959.5  690.85  5040.5  690.85  5043.3  698.85  5056.1  698.89  5062.5  709.79
  5084.4  708.48  5100.3  709.19  5127.9  713.19  5137.8  715.89  5156.6  723.53
  5178.4  734.47  5210.1   752.4  5234.3  763.51  5264.5  776.15  5298.1  786.63
#Mann= 3 ,-1 , 0
  4700.3     .09       0  4956.7    .045       0  5043.3     .09       0
Bank Sta=4956.7,5043.3
Exp/Cntr=0.3,0.1

Type RM Length L Ch R = 1 ,423864  ,480,480,480
BEGIN DESCRIPTION:
Dan River 134.0
END DESCRIPTION:
XS GIS Cut Line= 3
       1637908.4       976290.63      1637614.63       976199.03
      1637377.71       976139.01
#Sta/Elev= 30
  4694.6  790.66  4717.2  778.88  4749.1   760.8    4784  742.67  4798.7  728.61
  4808.6  724.79  4829.5  713.57  4842.5  710.05  4898.4  706.47  4905.2  706.69
  4911.3  707.97  4919.4  705.67  4945.8  697.71  4956.7  697.71  4959.5  689.71
  5040.5  689.71  5043.3  697.71  5052.2  697.74  5052.5  698.87  5053.4   699.9
  5066.9  707.04  5083.1   707.4  5094.7   708.6  5104.7  712.47  5117.4  713.44
  5139.7     717  5153.5   721.8  5178.5  735.18    5218     753  5246.7  761.33
#Mann= 5 ,-1 , 0
  4694.6     .09       0  4808.6    .035       0  4919.4     .09       0
  4956.7    .045       0  5043.3     .09       0
Bank Sta=4956.7,5043.3
Exp/Cntr=0.3,0.1

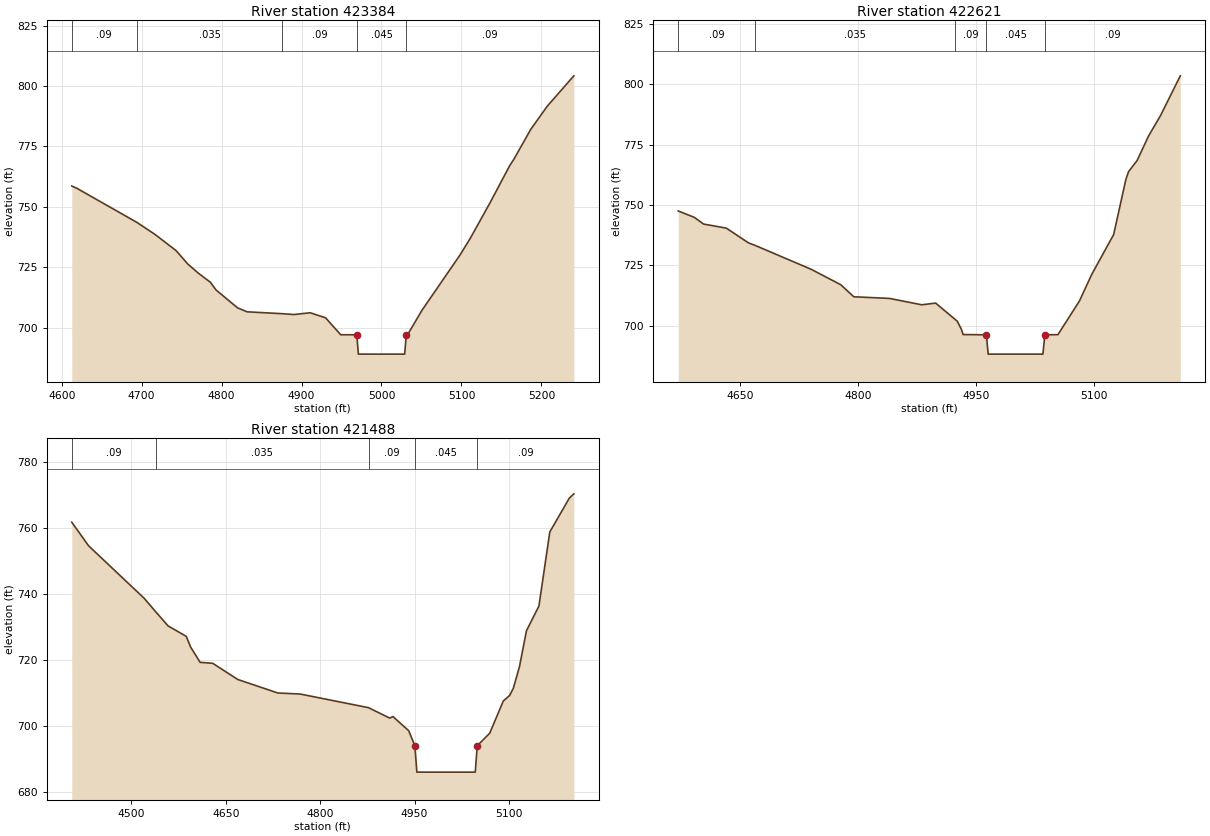
Type RM Length L Ch R = 1 ,423384  ,763,763,763
BEGIN DESCRIPTION:
Dan River 133.0
END DESCRIPTION:
XS GIS Cut Line= 3
      1638088.45       975965.28      1637768.56       975749.32
      1637557.77       975630.44
#Sta/Elev= 30
  4612.6  758.63    4619   757.7    4694  743.61  4716.8  738.59  4743.2  731.89
  4757.7  726.37  4770.9  722.59  4786.1  718.79    4793  715.66  4819.9  708.24
  4831.8  706.59  4875.7  705.81  4890.4  705.47  4910.9  706.19  4930.1  704.11
    4949   697.1  4969.1  697.08  4971.1  689.08    5029  689.08    5031  697.08
  5033.2  697.44  5050.7  707.25    5098  729.99    5111  736.96  5135.6   751.6
  5160.3  767.03  5165.9  769.89  5186.6  782.03  5207.3  791.66  5240.6  804.24
#Mann= 5 ,-1 , 0
  4612.6     .09       0    4694    .035       0  4875.7     .09       0
  4969.1    .045       0    5031     .09       0
Bank Sta=4969.1,5031
Exp/Cntr=0.3,0.1

Type RM Length L Ch R = 1 ,422621  ,1133,1133,1133
BEGIN DESCRIPTION:
Dan River 132.0
END DESCRIPTION:
XS GIS Cut Line= 3
      1638473.82       976022.14      1638461.19       975598.85
      1638476.98       975384.06
#Sta/Elev= 30
  4570.8  747.51  4591.3  744.86  4603.1  742.08    4632   740.4  4660.1   734.3
  4668.8  733.21    4740  723.32  4777.6  716.93  4794.2  711.93  4839.7  711.25
  4880.7   708.6  4898.3  709.31  4922.5  702.71  4925.8  701.81  4931.1  698.43
  4933.3  696.27  4962.8  696.15  4965.2  688.15  5034.8  688.15  5037.2  696.15
  5053.9  696.23  5081.3  710.21  5096.8  721.14  5124.8  737.74  5140.4  760.67
  5143.8  763.84  5154.6   768.4  5169.3  778.65  5184.4  787.06  5209.6  803.55
#Mann= 5 ,-1 , 0
  4570.8     .09       0  4668.8    .035       0  4922.5     .09       0
  4962.8    .045       0  5037.2     .09       0
Bank Sta=4962.8,5037.2
Exp/Cntr=0.3,0.1

Type RM Length L Ch R = 1 ,421488  ,1008,1008,1008
BEGIN DESCRIPTION:
Dan River 130.0
END DESCRIPTION:
XS GIS Cut Line= 3
      1639554.14       976211.66      1639592.04       975620.97
      1639645.74       975421.96
#Sta/Elev= 30
  4405.1  761.66  4431.8  754.51  4520.1  738.63  4538.4  734.56  4558.2  730.25
  4587.1  727.09  4594.2  723.78  4609.2  719.22  4629.2  718.93  4668.9  714.04
  4732.6  709.95  4768.2  709.63  4876.8   705.5  4910.4  702.35  4915.6  702.81
  4940.7  698.51  4950.4  693.99  4953.6  685.99  5046.4  685.99  5049.6  693.99
  5069.4  697.77    5091  707.53  5101.2  709.22    5107  711.42  5116.7  717.93
  5127.8  728.79  5147.6  736.26  5164.9   758.7  5195.9  768.94  5203.1  770.24
#Mann= 5 ,-1 , 0
  4405.1     .09       0  4538.4    .035       0  4876.8     .09       0
  4950.4    .045       0  5049.6     .09       0
Bank Sta=4950.4,5049.6
Exp/Cntr=0.3,0.1