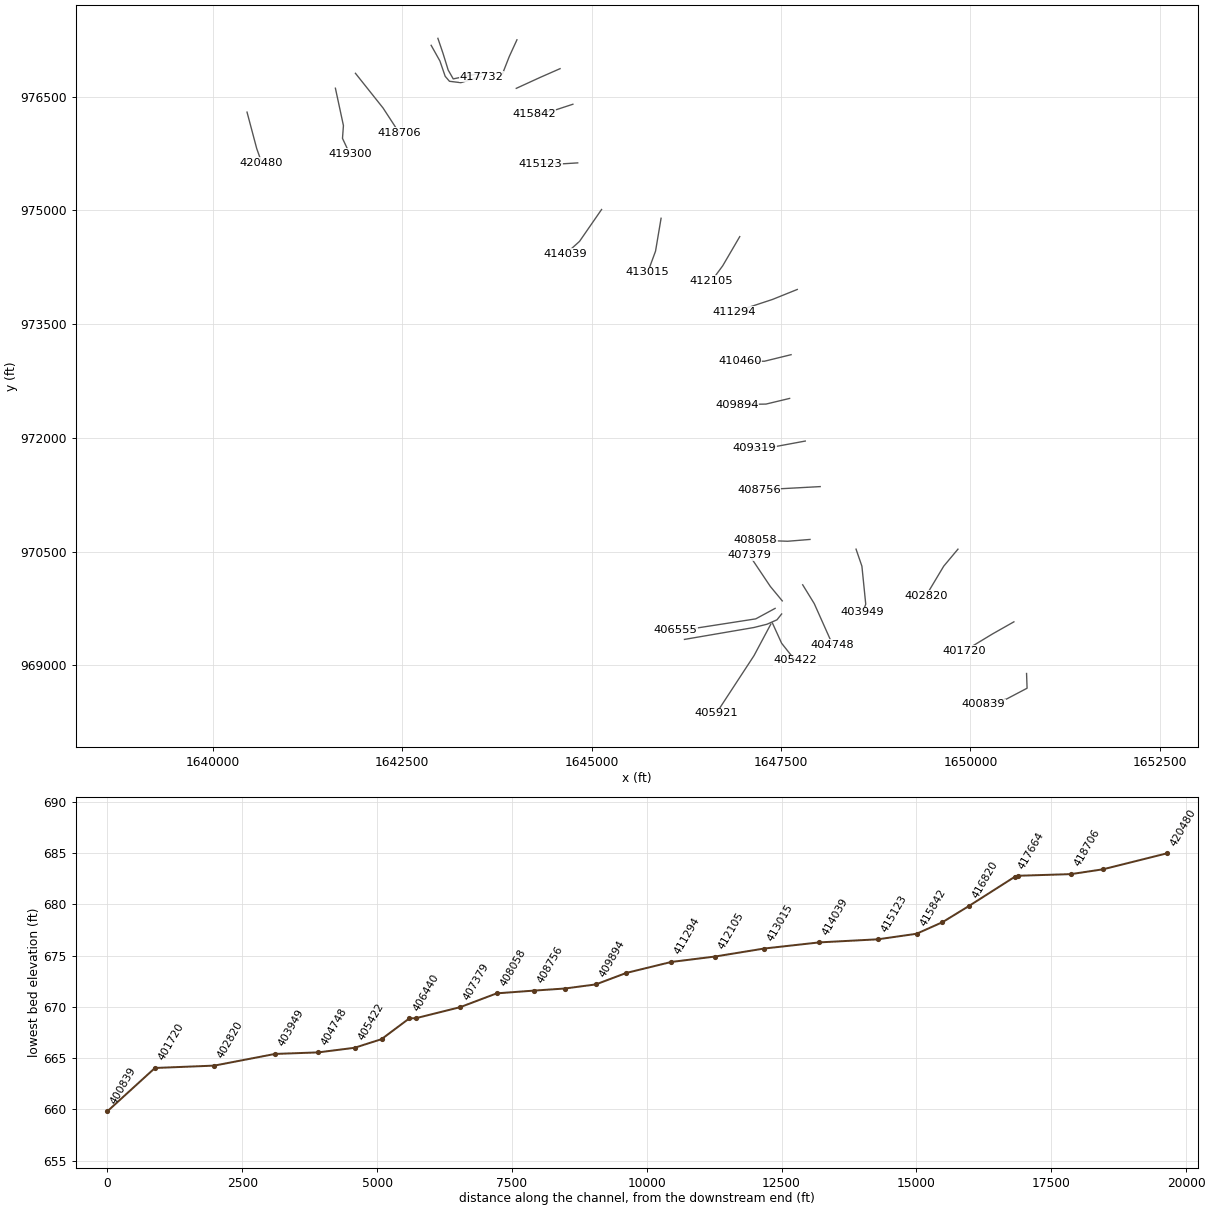
HEC-RAS study lds_dan_rvr_bctfud_lower.prj: Dan River Limited Detail Study Lower

--- lds_dan_rvr_bctfud_lower.g02 (geometry) --- (continued)

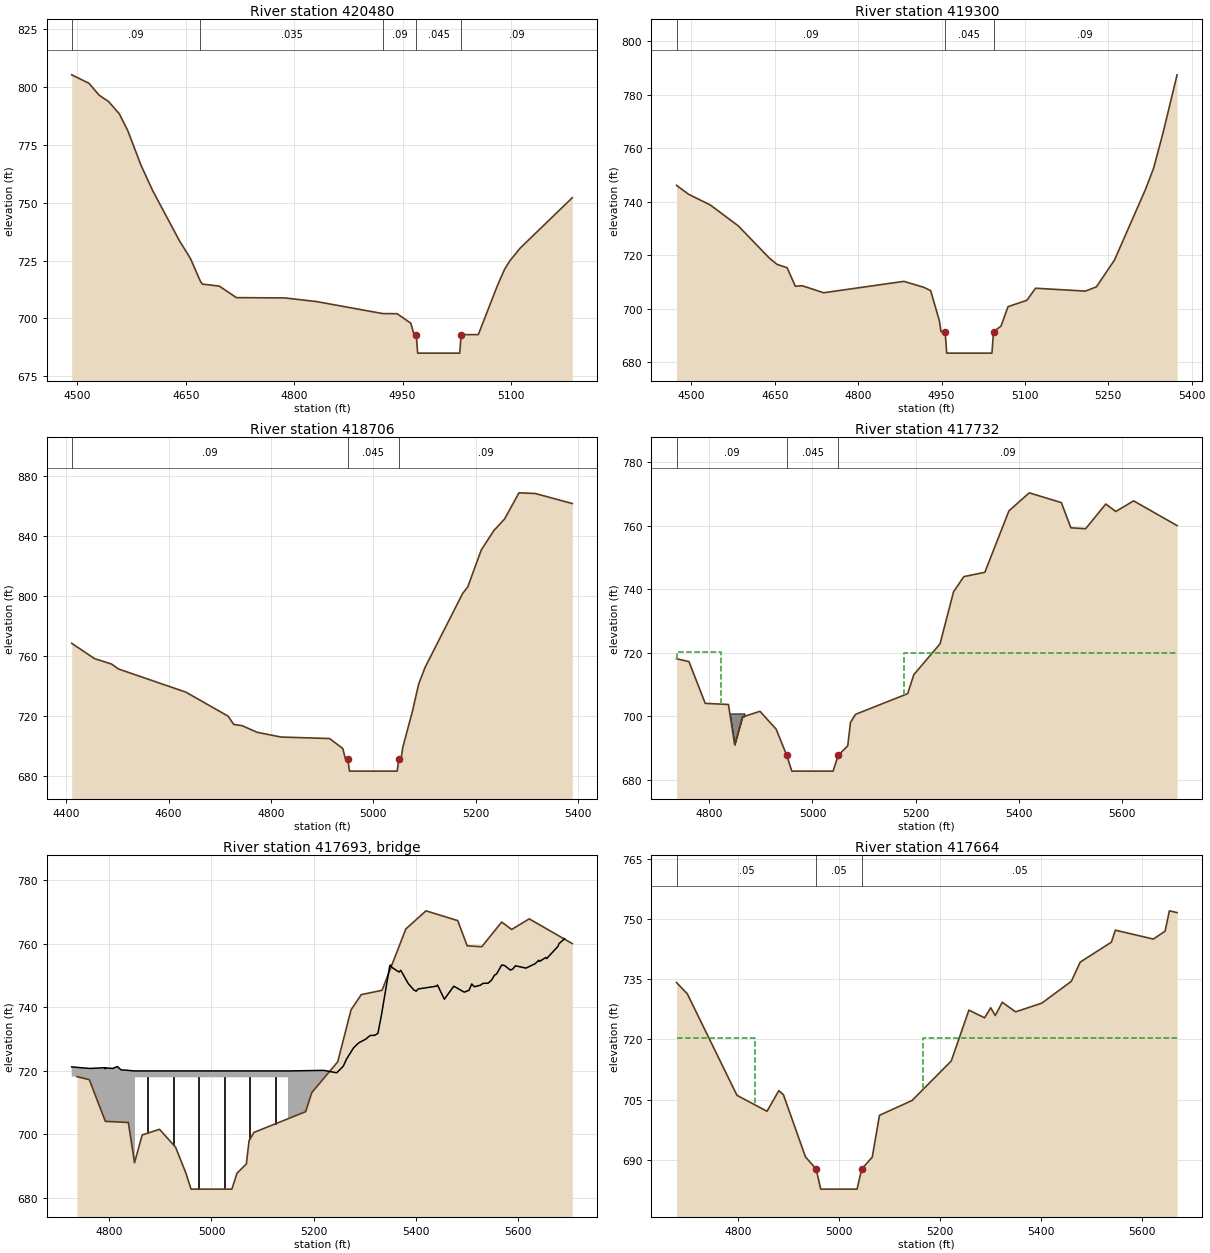
Type RM Length L Ch R = 1 ,420480  ,1180,1180,1180
BEGIN DESCRIPTION:
Dan River 128.0
END DESCRIPTION:
XS GIS Cut Line= 3
       1640449.3       976296.02      1640577.22       975815.54
      1640642.74       975631.46
#Sta/Elev= 30
  4492.2   805.3  4516.1  801.65  4530.1  796.52  4543.2  793.76    4558  788.49
  4569.8  781.18    4588  766.29  4604.1  755.34  4640.8  733.84  4656.6  725.82
  4670.2   716.1    4673  714.83  4696.5  713.96  4720.1  708.97  4786.8  708.85
  4830.6  707.29  4922.6  702.08  4942.5  702.02  4961.4  697.91  4965.9  692.99
  4968.9  692.98  4970.9  684.98  5029.1  684.98  5031.1  692.98  5054.8  692.98
  5080.9  713.92  5091.1   721.2  5098.7  724.99  5112.8   730.4  5184.8  752.16
#Mann= 5 ,-1 , 0
  4492.2     .09       0  4670.2    .035       0  4922.6     .09       0
  4968.9    .045       0  5031.1     .09       0
Bank Sta=4968.9,5031.1
Exp/Cntr=0.3,0.1

Type RM Length L Ch R = 1 ,419300  ,594,594,594
BEGIN DESCRIPTION:
Dan River 126.0
END DESCRIPTION:
XS GIS Cut Line= 4
      1641616.18       976611.13      1641722.26       976118.18
      1641709.78        975949.7       1641806.5       975743.78
#Sta/Elev= 30
  4473.1  746.13  4494.6  742.82  4533.8   738.8  4584.4  730.96  4640.4  718.88
  4654.3  716.57  4672.1  715.34  4686.9  708.43  4699.3  708.61  4737.9  705.99
  4882.2  710.25  4917.9  708.04  4930.4  706.78  4946.1  695.52    4949  691.46
  4956.5  691.43  4959.3  683.43  5040.7  683.43  5043.5  691.43    5057  693.52
  5069.6  700.79  5103.5  703.16  5119.1  707.68  5208.9  706.61  5228.6  708.19
  5261.2  718.22  5316.7  744.49  5331.6  752.57  5348.5  765.72  5373.8  787.42
#Mann= 3 ,-1 , 0
  4473.1     .09       0  4956.5    .045       0  5043.5     .09       0
Bank Sta=4956.5,5043.5
Exp/Cntr=0.3,0.1

Type RM Length L Ch R = 1 ,418706  ,974,974,974
BEGIN DESCRIPTION:
Dan River 125.0
END DESCRIPTION:
XS GIS Cut Line= 3
      1641880.81       976807.78      1642245.55       976350.07
       1642460.1       976021.09
#Sta/Elev= 30
  4410.7  768.39  4455.5  758.13  4488.5  754.54  4502.1  751.24  4633.9  735.74
  4716.5  719.65  4727.2  714.21  4744.1  713.29  4772.9  708.92  4819.5  705.75
  4914.5  704.74  4940.3  698.13  4945.3  691.34  4950.2  690.96  4953.4  682.96
  5046.6  682.96  5049.8  690.96  5054.1  690.96  5057.5  698.75  5076.2  722.67
  5088.6  741.15    5101  752.22  5174.6  801.76  5184.4     806    5211  830.85
  5235.4  843.69  5256.5  851.52  5284.6  868.97  5316.2  868.54  5388.7  861.82
#Mann= 3 ,-1 , 0
  4410.7     .09       0  4950.2    .045       0  5049.8     .09       0
Bank Sta=4950.2,5049.8
Exp/Cntr=0.5,0.3

Type RM Length L Ch R = 1 ,417732  ,68,68,68
BEGIN DESCRIPTION:
Seven Island Rd. SR-1668 - US
END DESCRIPTION:
XS GIS Cut Line= 6
       1642880.4       977177.02      1642996.01       976970.75
      1643065.64       976768.43      1643122.13       976702.74
       1643271.9       976684.35      1643542.54        976765.8
#Sta/Elev= 30
  4736.4   718.2  4760.6  717.25  4792.1  704.13  4837.1  703.78  4849.2  691.11
  4864.2  699.85  4898.2  701.63  4929.7     696    4950   687.8    4960   682.8
    5040   682.8    5050   687.8  5068.4  690.75  5073.7  698.11  5083.5  700.67
 5184.63  707.18  5196.5  713.15  5247.4  722.88  5273.5  739.22  5293.5  744.02
  5334.3  745.39  5380.9  764.71  5420.4   770.4  5482.6  767.32  5501.1  759.39
  5529.7   759.1  5568.7  766.87  5588.2  764.53  5622.7  767.87    5707  760.09
#Mann= 3 ,-1 , 0
  4736.4     .09       0    4950    .045       0    5050     .09       0
#XS Ineff= 2 , 0
       0    4823  720.23    5177       0  720.14
Permanent Ineff=
       F       F
#Block Obstruct= 1 ,-1
  4836.9    4868  700.96
Bank Sta=4950,5050
Exp/Cntr=0.5,0.3

Type RM Length L Ch R = 3 ,417693  ,,,
BEGIN DESCRIPTION:
Seven Island Rd. SR-1668
Structure ID: Seven Island Road
Approximate Survey Structure
END DESCRIPTION:
Bridge Culvert--1,0,-1,-1, 0
Deck Dist Width WeirC Skew NumUp NumDn MinLoCord MaxHiCord MaxSubmerge Is_Ogee
27,14,3,0, 60, 60, , , , 0, 0.5,0.5,,
  4726.1  4761.5  4790.2  4791.9  4792.7  4806.4  4815.7  4822.6    4850    4850
    5150    5150  5220.2  5245.4  5258.2  5264.7  5278.6  5288.6    5302  5310.7
  5320.1  5326.1  5332.5  5349.3    5351  5353.2  5367.5  5370.9  5385.7  5396.5
  5401.2  5404.9  5439.8    5443  5456.3  5474.8  5495.4  5504.7    5510  5514.9
    5527  5531.8  5542.2  5549.1  5554.6  5558.7  5568.7  5574.2  5585.8  5590.5
  5595.6  5616.3  5634.5  5641.5  5643.1  5655.1  5656.8  5679.1  5680.6  5692.1
  721.28  720.78  721.02  720.67  720.97  720.79  721.39  720.36     720     720
     720     720  720.18  719.42  721.47  723.74  727.32  728.85  729.97  731.15
  731.23  731.82  737.06  753.09  753.37  752.62  751.13  751.68  747.47   745.5
   745.1   745.8  746.66  747.03  742.57  746.67   744.8   745.4  747.38   746.5
  746.98  747.56  747.63  748.63  750.15  750.52  753.35  753.19  751.75  752.09
   753.1  752.37  753.78  754.85  754.49  755.71  755.36  759.24     760  761.64
   662.8   662.8   662.8   662.8   662.8   662.8   662.8   662.8   662.8     718
     718   662.8   662.8   662.8   662.8   662.8   662.8   662.8   662.8   662.8
   662.8   662.8   662.8   662.8   662.8   662.8   662.8   662.8   662.8   662.8
   662.8   662.8   662.8   662.8   662.8   662.8   662.8   662.8   662.8   662.8
   662.8   662.8   662.8   662.8   662.8   662.8   662.8   662.8   662.8   662.8
   662.8   662.8   662.8   662.8   662.8   662.8   662.8   662.8   662.8   662.8
  4726.1  4761.5  4790.2  4791.9  4792.7  4806.4  4815.7  4822.6    4850    4850
    5150    5150  5220.2  5245.4  5258.2  5264.7  5278.6  5288.6    5302  5310.7
  5320.1  5326.1  5332.5  5349.3    5351  5353.2  5367.5  5370.9  5385.7  5396.5
  5401.2  5404.9  5439.8    5443  5456.3  5474.8  5495.4  5504.7    5510  5514.9
    5527  5531.8  5542.2  5549.1  5554.6  5558.7  5568.7  5574.2  5585.8  5590.5
  5595.6  5616.3  5634.5  5641.5  5643.1  5655.1  5656.8  5679.1  5680.6  5692.1
  721.28  720.78  721.02  720.67  720.97  720.79  721.39  720.36     720     720
     720     720  720.18  719.42  721.47  723.74  727.32  728.85  729.97  731.15
  731.23  731.82  737.06  753.09  753.37  752.62  751.13  751.68  747.47   745.5
   745.1   745.8  746.66  747.03  742.57  746.67   744.8   745.4  747.38   746.5
  746.98  747.56  747.63  748.63  750.15  750.52  753.35  753.19  751.75  752.09
   753.1  752.37  753.78  754.85  754.49  755.71  755.36  759.24     760  761.64
   662.8   662.8   662.8   662.8   662.8   662.8   662.8   662.8   662.8     718
     718   662.8   662.8   662.8   662.8   662.8   662.8   662.8   662.8   662.8
   662.8   662.8   662.8   662.8   662.8   662.8   662.8   662.8   662.8   662.8
   662.8   662.8   662.8   662.8   662.8   662.8   662.8   662.8   662.8   662.8
   662.8   662.8   662.8   662.8   662.8   662.8   662.8   662.8   662.8   662.8
   662.8   662.8   662.8   662.8   662.8   662.8   662.8   662.8   662.8   662.8
Pier Skew, UpSta & Num, DnSta & Num=  ,4875, 2 ,4875, 2 , 0 , 0 , 0 ,0,0
       2       2
  700.25     718
       2       2
  706.09     718
Pier Skew, UpSta & Num, DnSta & Num=  ,4925, 2 ,4925, 2 , 0 , 0 , 0 ,0,0
       2       2
  696.57     718
       2       2
  694.06     718
Pier Skew, UpSta & Num, DnSta & Num=  ,4975, 2 ,4975, 2 , 0 , 0 , 0 ,0,0
       2       2
     659     718
       2       2
  658.75     718
Pier Skew, UpSta & Num, DnSta & Num=  ,5025, 2 ,5025, 2 , 0 , 0 , 0 ,0,0
       2       2
     659     718
       2       2
  658.75     718
Pier Skew, UpSta & Num, DnSta & Num=  ,5075, 2 ,5075, 2 , 0 , 0 , 0 ,0,0
       2       2
  698.45     718
       2       2
  698.05     718
Pier Skew, UpSta & Num, DnSta & Num=  ,5125, 2 ,5125, 2 , 0 , 0 , 0 ,0,0
       2       2
  704.54     718
       2       2
   704.5     718
Abutment Skew #Up #Dn= , 2 , 2
    4850  4862.5
     718  698.35
    4850  4862.5
     718  703.21
Abutment Skew #Up #Dn= , 2 , 2
  5137.5    5150
  704.59     718
  5137.5    5150
  704.59     718
BR Coef= 1 , 1 , 0 ,1.25, 0 ,,,0.8,0,2,0,
WSPro=,,,, 1 ,,,, 0 ,,,, 0 ,,,,-1 ,-1 ,-1 , 0 , 0 , 0 , 0 , 0
BC Design=,, 0 ,, 0 ,,,,,,
BC HTab HWMax=770.49

Type RM Length L Ch R = 1 ,417664  ,844,844,844
BEGIN DESCRIPTION:
Seven Island Rd. SR-1668 - DS
END DESCRIPTION:
XS GIS Cut Line= 6
      1642969.32       977269.19      1643036.74       977071.92
      1643105.05        976851.2      1643172.06       976734.27
      1643526.78       976807.85      1643580.64        976813.1
#Sta/Elev= 30
  4678.6  734.19  4699.9   731.4  4798.3  706.08  4857.7   702.1  4881.1  707.25
  4890.2  706.23  4933.8  690.75    4955   687.7    4964   682.7    5036   682.7
    5045   687.7    5066  690.67  5080.3   701.1  5144.9   704.8  5222.4  714.65
  5257.3  727.32  5288.3   725.4  5300.5   727.9  5309.5  725.97  5323.3  729.28
  5349.7  726.89  5401.7  729.07  5460.1  734.51  5477.6  739.29  5539.3  744.26
  5547.2  747.25  5622.4  745.03  5645.6  747.01  5654.1  752.07  5669.3  751.63
#Mann= 3 ,-1 , 0
  4678.6     .05       0    4955     .05       0    5045     .05       0
#XS Ineff= 2 , 0
       0    4833  720.47    5167       0  720.47
Permanent Ineff=
       F       F
Bank Sta=4955,5045
Exp/Cntr=0.5,0.3

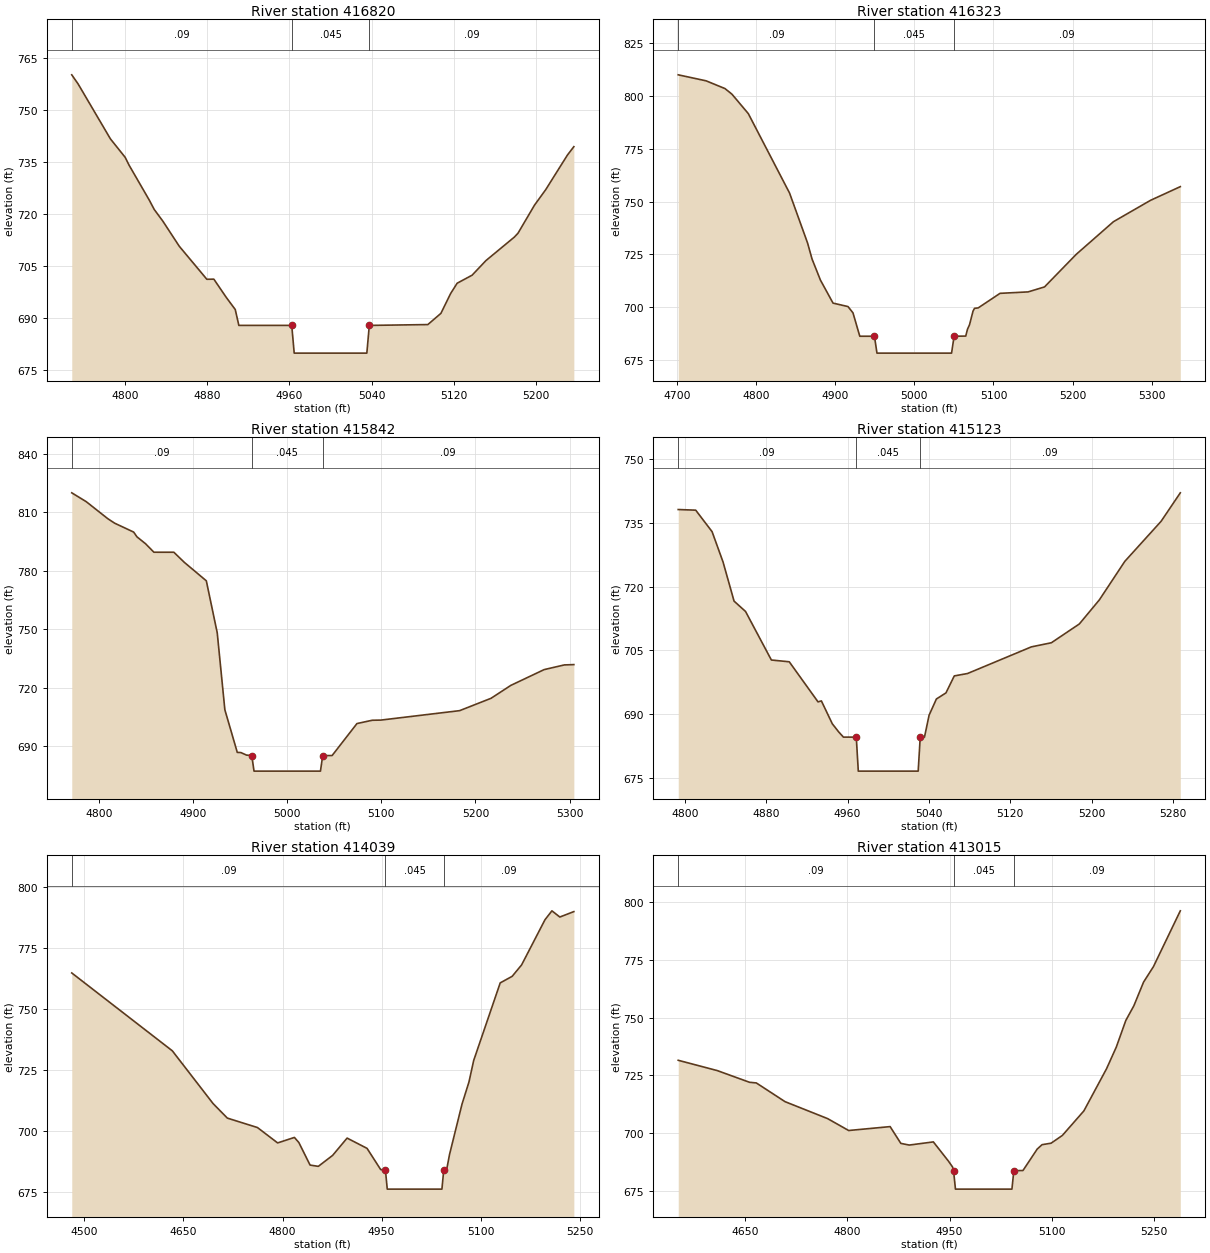
Type RM Length L Ch R = 1 ,416820  ,497,497,497
BEGIN DESCRIPTION:
Dan River 123.0
END DESCRIPTION:
XS GIS Cut Line= 3
      1644013.13       977249.81       1643911.9       977029.48
      1643822.14       976800.97
#Sta/Elev= 30
  4748.5  760.19  4754.7  757.54  4786.1  741.69  4800.4  736.38  4804.2  734.12
  4823.9     724  4828.7  721.31  4837.1  717.93    4853  710.71  4879.8  701.18
  4886.6  701.22  4898.7  695.94  4907.4  692.46  4910.9  687.87  4962.3  687.87
  4964.7  679.87  5035.3  679.87  5037.7  687.87  5094.6  688.11  5107.3  691.35
  5116.7  697.05  5123.1  700.05  5137.6  702.36  5151.1  706.59  5178.6  713.34
  5182.2  714.47  5198.3   722.6  5209.1  727.02  5230.3  737.05  5236.5  739.45
#Mann= 3 ,-1 , 0
  4748.5     .09       0  4962.3    .045       0  5037.7     .09       0
Bank Sta=4962.3,5037.7
Exp/Cntr=0.3,0.1

Type RM Length L Ch R = 1 ,416323  ,481,481,481
BEGIN DESCRIPTION:
Dan River 122.5
END DESCRIPTION:
XS GIS Cut Line= 3
      1644582.57       976869.28      1644324.55       976756.11
       1644004.2       976609.43
#Sta/Elev= 30
  4701.9  810.02  4737.1  807.18  4760.9  803.52  4769.7  800.87  4790.4  791.66
  4842.5  754.05  4865.2  730.45  4870.9  722.82  4881.5  712.84  4897.4  701.95
  4916.3  700.31  4922.6  697.33  4931.2  686.27  4949.7  686.27  4952.9  678.27
  5047.1  678.27  5050.3  686.27    5065  686.34  5067.2  689.56  5069.8  691.73
  5074.2  698.15  5076.1  699.47  5080.7  699.67  5108.3  706.57  5143.8  707.26
  5164.5  709.61  5204.6  725.05  5251.6   740.5  5298.4  750.61    5336  757.08
#Mann= 3 ,-1 , 0
  4701.9     .09       0  4949.7    .045       0  5050.3     .09       0
Bank Sta=4949.7,5050.3
Exp/Cntr=0.3,0.1

Type RM Length L Ch R = 1 ,415842  ,719,719,719
BEGIN DESCRIPTION:
Dan River 122.0
END DESCRIPTION:
XS GIS Cut Line= 3
      1644751.64       976399.89       1644534.1       976328.61
      1644235.96       976266.19
#Sta/Elev= 30
    4771  819.95  4786.4  815.41  4809.2  806.71  4816.5  804.39  4836.8   799.8
  4840.2  797.41  4849.5  793.78  4858.3  789.47  4879.5  789.46  4890.7  784.24
    4914   774.8  4925.6  748.12  4933.7  708.65  4946.9  686.77  4950.7  686.67
  4956.7  685.37  4962.3  685.14  4964.7  677.14  5035.3  677.14  5037.7  685.14
  5047.7  685.14  5074.1  701.55  5090.3  703.24  5099.5  703.33  5183.2  708.17
  5216.6  714.51  5237.6  721.13    5273  729.23  5294.5  731.64  5304.6   731.8
#Mann= 3 ,-1 , 0
    4771     .09       0  4962.3    .045       0  5037.7     .09       0
Bank Sta=4962.3,5037.7
Exp/Cntr=0.3,0.1

Type RM Length L Ch R = 1 ,415123  ,1084,1084,1084
BEGIN DESCRIPTION:
Dan River 121.0
END DESCRIPTION:
XS GIS Cut Line= 3
       1644815.3       975626.37      1644605.62       975613.44
       1644321.9       975616.82
#Sta/Elev= 30
  4793.5  738.14  4810.7  737.99  4826.8  732.93  4837.6  725.78  4848.4   716.6
  4859.7  714.16  4885.1  702.74  4902.7  702.32    4931  692.89  4934.3  693.12
    4945  687.75  4951.4   685.8    4956   684.6  4968.6   684.6  4970.6   676.6
  5029.5   676.6  5031.5   684.6  5035.7  684.61  5040.2  689.74  5047.4  693.57
  5056.8     695    5065     699    5078  699.56  5140.8  705.83  5160.5   706.8
    5188  711.22  5207.7  716.89  5232.7  725.94  5268.4  735.37  5287.3  742.07
#Mann= 3 ,-1 , 0
  4793.5     .09       0  4968.6    .045       0  5031.5     .09       0
Bank Sta=4968.6,5031.5
Exp/Cntr=0.3,0.1

Type RM Length L Ch R = 1 ,414039  ,1024,1024,1024
BEGIN DESCRIPTION:
Dan River 120.0
END DESCRIPTION:
XS GIS Cut Line= 3
      1645130.45       975011.57      1644839.25       974590.94
      1644654.36       974424.54
#Sta/Elev= 30
  4480.8  764.95  4633.1  733.02  4694.8  711.39  4716.4  705.43    4762  701.56
  4792.6  695.25    4818   697.5  4824.7  695.42  4841.7  686.17  4854.2  685.64
  4875.9  690.14  4897.8  697.23    4928  693.02  4948.7   684.3  4955.8   684.3
  4958.6   676.3  5041.4   676.3  5044.2   684.3  5048.8  684.63    5053  690.59
  5071.8  711.13  5082.4  720.29  5089.5  729.05  5129.7  760.88  5147.8  763.57
  5162.1  768.26  5197.5  786.78    5208  790.43    5220  787.89  5241.2  790.11
#Mann= 3 ,-1 , 0
  4480.8     .09       0  4955.8    .045       0  5044.2     .09       0
Bank Sta=4955.8,5044.2
Exp/Cntr=0.3,0.1

Type RM Length L Ch R = 1 ,413015  ,910,910,910
BEGIN DESCRIPTION:
Dan River 119.0
END DESCRIPTION:
XS GIS Cut Line= 3
      1645916.23       974896.01      1645842.87       974462.01
      1645740.59       974184.19
#Sta/Elev= 30
  4552.1  731.55  4609.4  727.08  4656.7  722.01  4666.6  721.73  4708.7  713.62
  4771.2  706.26    4802  701.11  4862.8   702.8  4878.5  695.53  4890.8   694.8
  4926.2  696.17  4948.4  687.81  4954.4  685.26  4955.8   683.7  4958.6   675.7
  5041.4   675.7  5044.2   683.7  5057.6  683.77  5078.5  693.08  5085.6  694.97
  5098.9  695.62  5115.4  698.99  5146.9  709.61  5180.2  727.92  5194.5  737.32
  5208.4  748.82  5220.2  755.19  5234.4  765.43  5248.9  772.15  5288.3  796.34
#Mann= 3 ,-1 , 0
  4552.1     .09       0  4955.8    .045       0  5044.2     .09       0
Bank Sta=4955.8,5044.2
Exp/Cntr=0.3,0.1

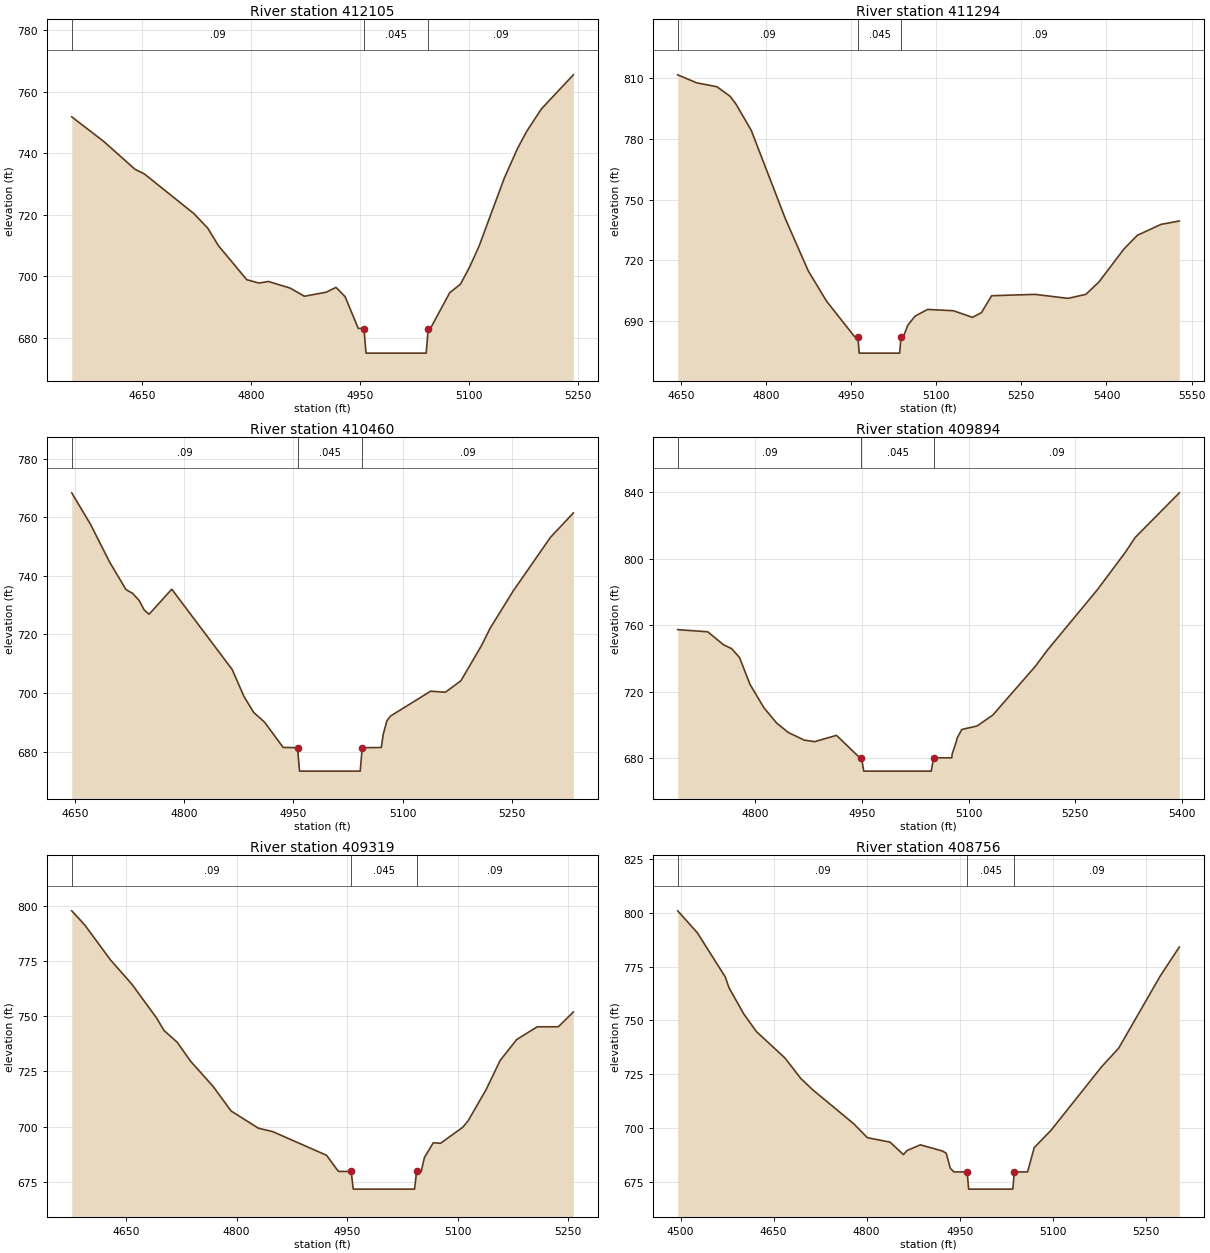
Type RM Length L Ch R = 1 ,412105  ,811,811,811
BEGIN DESCRIPTION:
Dan River 118.0
END DESCRIPTION:
XS GIS Cut Line= 3
       1646954.8       974653.77      1646729.68       974268.91
      1646584.71       974072.21
#Sta/Elev= 30
  4553.7  751.87  4597.6  743.89  4640.6  734.83  4653.9  733.24  4721.5  720.42
  4740.7  715.67  4755.5  709.93  4794.5  698.84  4811.3  697.74  4824.2  698.26
  4854.2  696.11  4873.8  693.44    4904  694.78  4917.3  696.33  4929.8  693.32
  4947.9  682.99  4955.8  682.92  4958.6  674.92  5041.4  674.92  5044.2  682.92
  5048.1  683.33  5073.8   694.6  5088.6  697.39  5101.4  703.09  5114.2  709.79
  5148.8  731.87    5167  741.56  5179.6  747.11  5199.8  754.42  5243.9  765.56
#Mann= 3 ,-1 , 0
  4553.7     .09       0  4955.8    .045       0  5044.2     .09       0
Bank Sta=4955.8,5044.2
Exp/Cntr=0.3,0.1

Type RM Length L Ch R = 1 ,411294  ,834,834,834
BEGIN DESCRIPTION:
Dan River 117.0
END DESCRIPTION:
XS GIS Cut Line= 3
      1647714.19       973956.86      1647387.64       973825.51
       1646882.7       973658.87
#Sta/Elev= 30
  4644.6   811.4  4678.1  807.46  4713.6  805.55    4737  800.82  4747.3  796.99
  4774.1   784.1  4834.7  740.26  4874.6   714.9  4906.7  700.03  4956.5   682.4
    4962  682.39  4964.4  674.39  5035.6  674.39    5038  682.39  5042.1  682.41
    5050  688.16  5062.9  692.62  5084.9  695.91  5130.6  695.25  5163.8  692.01
  5179.8  694.33  5197.6  702.65  5274.1  703.32  5332.3  701.35  5363.7  703.34
  5386.6  709.38  5430.6  725.61  5454.4  732.41  5496.1  737.78  5528.3  739.44
#Mann= 3 ,-1 , 0
  4644.6     .09       0    4962    .045       0    5038     .09       0
Bank Sta=4962,5038
Exp/Cntr=0.3,0.1

Type RM Length L Ch R = 1 ,410460  ,566,566,566
BEGIN DESCRIPTION:
Dan River 116.0
END DESCRIPTION:
XS GIS Cut Line= 3
      1647632.48       973096.53      1647280.37       973010.21
       1646954.8       973010.02
#Sta/Elev= 30
  4645.9  768.34  4671.6  757.61  4697.8  744.73  4720.3  735.31  4729.4  734.02
  4738.5  731.54  4745.4   728.3    4752  726.88  4783.1  735.44    4866  708.01
  4882.1  698.84  4895.4  693.39  4910.4  690.05  4935.9  681.41  4955.6  681.32
  4958.4  673.32  5041.6  673.32  5044.4  681.32  5070.5  681.38  5073.3     686
  5078.2  690.52  5083.2  692.13  5138.2  700.61  5158.5  700.26  5179.8  704.19
  5207.8  716.11  5219.9  722.13  5251.3  734.77  5302.7  753.18    5334  761.46
#Mann= 3 ,-1 , 0
  4645.9     .09       0  4955.6    .045       0  5044.4     .09       0
Bank Sta=4955.6,5044.4
Exp/Cntr=0.3,0.1

Type RM Length L Ch R = 1 ,409894  ,575,575,575
BEGIN DESCRIPTION:
Dan River 115.0
END DESCRIPTION:
XS GIS Cut Line= 3
      1647613.26       972519.78      1647301.82       972445.22
      1646916.35       972438.07
#Sta/Elev= 30
  4690.7  757.37  4732.9  756.07  4755.4   748.2  4766.5  745.95  4777.7  740.59
  4792.4  724.43  4812.2  710.24  4830.2  701.01  4846.6  695.39  4868.9  690.85
  4883.4  689.94  4914.1  693.73  4946.9  680.24  4949.3   680.2  4952.5   672.2
  5047.5   672.2  5050.7   680.2  5076.3   680.2    5077  682.61  5083.2  690.62
  5083.6  691.87  5090.4  697.29  5111.8  699.34    5134  705.91  5194.6  735.65
  5210.7  744.94  5281.7  781.67  5320.7  804.02  5334.4  812.83  5396.5  839.72
#Mann= 3 ,-1 , 0
  4690.7     .09       0  4949.3    .045       0  5050.7     .09       0
Bank Sta=4949.3,5050.7
Exp/Cntr=0.3,0.1

Type RM Length L Ch R = 1 ,409319  ,563,563,563
BEGIN DESCRIPTION:
Dan River 114.0
END DESCRIPTION:
XS GIS Cut Line= 3
      1647819.93       971957.44      1647401.95       971880.24
      1647147.05       971861.32
#Sta/Elev= 30
  4576.4  797.63  4594.1  791.22    4629  775.42    4658  764.47  4691.7  749.09
  4701.5  743.56  4719.5  738.22  4737.5   729.7  4768.2  718.26  4792.6  707.15
  4829.6  699.36    4849  697.82  4922.1  687.12  4938.3  679.81  4955.6   679.8
  4958.4   671.8  5041.6   671.8  5044.4   679.8  5050.6   679.8    5055  686.11
    5067  692.76  5076.9  692.53  5107.2  699.81  5114.5  702.81  5138.9  716.92
  5157.7  729.95  5180.2  739.44  5208.1  745.19  5236.7  745.21  5257.1  751.89
#Mann= 3 ,-1 , 0
  4576.4     .09       0  4955.6    .045       0  5044.4     .09       0
Bank Sta=4955.6,5044.4
Exp/Cntr=0.3,0.1

Type RM Length L Ch R = 1 ,408756  ,698,698,698
BEGIN DESCRIPTION:
Dan River 113.0
END DESCRIPTION:
XS GIS Cut Line= 3
      1648016.99       971356.66      1647516.38       971329.55
      1647209.53        971313.4
#Sta/Elev= 30
  4495.4  800.91  4526.9  790.78  4572.1  770.19    4578  765.22  4601.6  753.13
  4622.3   744.8  4668.5  732.48  4693.7  723.06  4713.2  717.72  4778.8  702.07
  4801.2  695.51  4837.7  693.43  4859.3  687.65  4864.9  689.52  4886.5  692.19
  4922.2  689.31  4928.2  688.31  4934.9  681.28  4940.7   679.6    4962   679.6
  4964.4   671.6  5035.6   671.6    5038   679.6  5059.4  679.61  5070.1  690.88
  5097.2  698.93  5178.6  728.42  5206.2  737.08  5273.3  770.65    5304   784.1
#Mann= 3 ,-1 , 0
  4495.4     .09       0    4962    .045       0    5038     .09       0
Bank Sta=4962,5038
Exp/Cntr=0.3,0.1

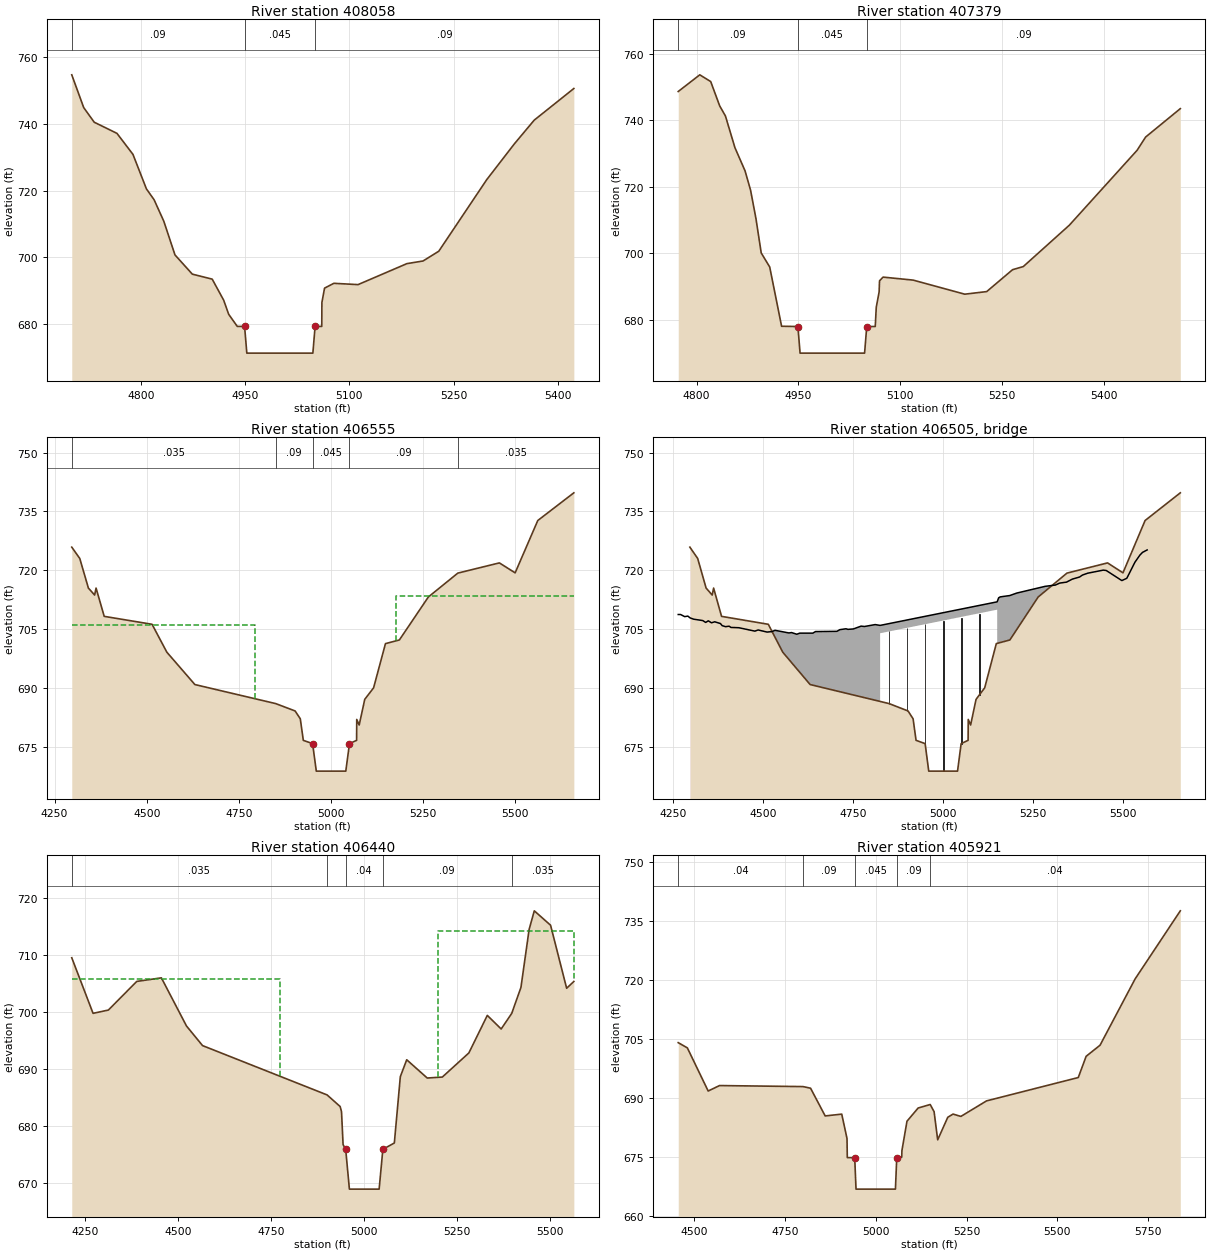
Type RM Length L Ch R = 1 ,408058  ,679,679,679
BEGIN DESCRIPTION:
Dan River 112.0
END DESCRIPTION:
XS GIS Cut Line= 3
      1647882.41       970659.74      1647587.89       970635.84
      1647161.47       970650.13
#Sta/Elev= 30
  4700.7  754.72  4717.9  744.89    4733  740.52  4765.7  737.18  4788.7  730.89
  4808.1  720.54  4819.1   717.3    4833   710.9  4849.2  700.75  4874.1     695
  4902.7   693.5  4919.2   687.2  4926.4  682.97  4938.8  679.33  4949.3  679.33
  4952.5  671.33  5047.5  671.33  5050.7  679.33  5060.3  679.33  5060.5  686.49
  5064.3   690.8  5077.7  692.25  5112.5  691.86  5182.7  698.14    5206  698.94
  5228.6  701.86  5297.6  723.31  5337.4  734.05  5365.9  741.14  5422.9  750.62
#Mann= 3 ,-1 , 0
  4700.7     .09       0  4949.3    .045       0  5050.7     .09       0
Bank Sta=4949.3,5050.7
Exp/Cntr=0.3,0.1

Type RM Length L Ch R = 1 ,407379  ,824,824,824
BEGIN DESCRIPTION:
Dan River 111.0
END DESCRIPTION:
XS GIS Cut Line= 3
      1647516.38       969849.14      1647358.52       970039.73
      1647084.57       970448.27
#Sta/Elev= 30
  4773.1  748.59  4804.8   753.6  4820.9  751.58  4834.2  744.24  4842.6  741.24
  4856.6  731.71  4871.5  724.74  4879.6  718.96  4887.5  710.46  4895.3  700.08
  4907.8  695.86  4925.3  678.05  4949.3  677.98  4952.5  669.98  5047.5  669.98
  5050.7  677.98  5063.2  677.98  5064.7  683.77  5068.9  688.36  5069.5   691.7
  5074.7  692.82    5119  691.92    5195  687.69  5227.3  688.47  5265.4  695.05
  5281.2  695.99  5348.9   708.4  5448.8  730.93  5461.3   734.9  5512.4  743.44
#Mann= 3 ,-1 , 0
  4773.1     .09       0  4949.3    .045       0  5050.7     .09       0
Bank Sta=4949.3,5050.7
Exp/Cntr=0.5,0.3

Type RM Length L Ch R = 1 ,406555  ,115,115,115
BEGIN DESCRIPTION:
Sheppard Mill Rd. SR-1674 - US
END DESCRIPTION:
XS GIS Cut Line= 4
      1647421.68        969750.3      1647166.55       969612.24
      1646299.76       969477.74      1646105.48       969470.27
#Sta/Elev= 30
  4296.8  725.92  4318.5  723.04  4341.9   715.5  4358.8  713.73  4362.7   715.5
  4384.8   708.3  4514.6  706.28  4554.6  699.19  4630.7  690.94    4850  686.09
  4902.5  684.22  4916.6  682.22  4924.8  676.74    4950   675.9    4960   668.9
    5040   668.9    5050   675.9  5069.3  676.74  5069.7  682.06  5076.3  680.64
  5091.4  687.17  5115.4  690.11  5147.6  701.36  5185.3  702.29  5263.9  713.23
  5343.8  719.31  5456.5  721.91  5499.3  719.38  5560.7   732.7  5658.5  739.75
#Mann= 5 ,-1 , 0
  4296.8    .035       0    4850     .09       0    4950    .045       0
    5050     .09       0  5343.8    .035       0
#XS Ineff= 2 , 0
       0    4793  705.99  5175.2       0   713.6
Permanent Ineff=
       F       F
Bank Sta=4950,5050
Exp/Cntr=0.5,0.3

Type RM Length L Ch R = 3 ,406505  ,,,
BEGIN DESCRIPTION:
Sheppard Mill Rd. SR-1674
Structure ID: Sheppard Mill Road
Approximate Survey Structure
END DESCRIPTION:
Bridge Culvert--1,0,-1,-1, 0
Deck Dist Width WeirC Skew NumUp NumDn MinLoCord MaxHiCord MaxSubmerge Is_Ogee
40,36,3,0, 60, 60, , , , 0, 0.5,0.5,,
  4264.5    4271  4282.5  4291.2  4297.2  4307.4  4332.6  4340.7    4348  4356.9
  4365.7  4381.7  4386.4  4396.2  4405.8  4410.8  4432.6  4477.3  4486.3  4511.1
  4524.9  4533.2  4571.7  4579.1  4593.6  4601.8  4638.2  4645.6    4705  4713.3
  4730.1  4736.1  4750.8  4772.3  4781.4  4811.3    4825    4825    5150    5150
  5154.1  5158.4    5185  5204.3  5283.4  5311.6  5323.6  5342.4  5358.9  5378.9
  5386.9    5401  5444.5  5452.8  5496.1  5509.9  5532.6  5546.3  5553.6  5566.4
  708.77  708.77  708.23  708.37  707.92  707.58  707.23  706.76  707.16  706.66
  706.92  706.47  705.94  705.67   705.8  705.48  705.41  704.54  704.84   704.3
  704.43  704.75  704.08  704.18  703.75  704.03  704.03  704.43  704.49  704.92
  705.14  704.99   705.1  705.82  705.72  706.21     706     706     712     712
  713.02  713.26   713.6  714.23  715.95  716.27  716.77  717.01  717.79  718.32
  718.82  719.28  720.07  719.98  717.41  717.99   722.1   723.9  724.59  725.21
   648.9   648.9   648.9   648.9   648.9   648.9   648.9   648.9   648.9   648.9
   648.9   648.9   648.9   648.9   648.9   648.9   648.9   648.9   648.9   648.9
   648.9   648.9   648.9   648.9   648.9   648.9   648.9   648.9   648.9   648.9
   648.9   648.9   648.9   648.9   648.9   648.9   648.9     704     710   648.9
   648.9   648.9   648.9   648.9   648.9   648.9   648.9   648.9   648.9   648.9
   648.9   648.9   648.9   648.9   648.9   648.9   648.9   648.9   648.9   648.9
  4264.5    4271  4282.5  4291.2  4297.2  4307.4  4332.6  4340.7    4348  4356.9
  4365.7  4381.7  4386.4  4396.2  4405.8  4410.8  4432.6  4477.3  4486.3  4511.1
  4524.9  4533.2  4571.7  4579.1  4593.6  4601.8  4638.2  4645.6    4705  4713.3
  4730.1  4736.1  4750.8  4772.3  4781.4  4811.3    4825    4825    5150    5150
  5154.1  5158.4    5185  5204.3  5283.4  5311.6  5323.6  5342.4  5358.9  5378.9
  5386.9    5401  5444.5  5452.8  5496.1  5509.9  5532.6  5546.3  5553.6  5566.4
  708.77  708.77  708.23  708.37  707.92  707.58  707.23  706.76  707.16  706.66
  706.92  706.47  705.94  705.67   705.8  705.48  705.41  704.54  704.84   704.3
  704.43  704.75  704.08  704.18  703.75  704.03  704.03  704.43  704.49  704.92
  705.14  704.99   705.1  705.82  705.72  706.21     706     706     712     712
  713.02  713.26   713.6  714.23  715.95  716.27  716.77  717.01  717.79  718.32
  718.82  719.28  720.07  719.98  717.41  717.99   722.1   723.9  724.59  725.21
   648.9   648.9   648.9   648.9   648.9   648.9   648.9   648.9   648.9   648.9
   648.9   648.9   648.9   648.9   648.9   648.9   648.9   648.9   648.9   648.9
   648.9   648.9   648.9   648.9   648.9   648.9   648.9   648.9   648.9   648.9
   648.9   648.9   648.9   648.9   648.9   648.9   648.9     704     710   648.9
   648.9   648.9   648.9   648.9   648.9   648.9   648.9   648.9   648.9   648.9
   648.9   648.9   648.9   648.9   648.9   648.9   648.9   648.9   648.9   648.9
Pier Skew, UpSta & Num, DnSta & Num=  ,4850, 2 ,4850, 2 , 0 , 0 , 0 ,0,0
       2       2
  686.09     705
       2       2
  686.45     705
Pier Skew, UpSta & Num, DnSta & Num=  ,4900, 2 ,4900, 2 , 0 , 0 , 0 ,0,0
       2       2
  684.33     707
       2       2
  685.46     706
Pier Skew, UpSta & Num, DnSta & Num=  ,4950, 2 ,4950, 2 , 0 , 0 , 0 ,0,0
       2       2
     647     707
       2       2
  646.75     707
Pier Skew, UpSta & Num, DnSta & Num=  ,5000, 2 ,5000, 2 , 0 , 0 , 0 ,0,0
       2       2
     640     708
       2       2
  639.75     708
Pier Skew, UpSta & Num, DnSta & Num=  ,5050, 2 ,5050, 2 , 0 , 0 , 0 ,0,0
       2       2
     647     708
       2       2
  646.75     709
Pier Skew, UpSta & Num, DnSta & Num=  ,5100, 2 ,5100, 2 , 0 , 0 , 0 ,0,0
       2       2
  688.79     709
       2       2
  689.88     710
Abutment Skew #Up #Dn= , 2 , 2
    4825  4862.5
     704     686
    4825  4862.5
     704  686.06
Abutment Skew #Up #Dn= , 2 , 2
    5120    5150
     690     710
    5120    5150
  691.39     710
BR Coef= 1 , 1 , 0 ,1.25, 0 ,,,0.8,0,2,0,
WSPro=,,,, 1 ,,,, 0 ,,,, 0 ,,,,-1 ,-1 ,-1 , 0 , 0 , 0 , 0 , 0
BC Design=,, 0 ,, 0 ,,,,,,
BC HTab HWMax=739.75

Type RM Length L Ch R = 1 ,406440  ,519,519,519
BEGIN DESCRIPTION:
Sheppard Mill Rd. SR-1674 - DS
END DESCRIPTION:
XS GIS Cut Line= 5
      1647507.81       969676.47      1647446.29       969599.57
      1647314.02       969541.13      1647141.76       969498.07
      1646225.11       969341.19
#Sta/Elev= 30
  4213.1  709.57  4270.4   699.8  4311.6  700.38  4387.9  705.41  4454.2  706.04
  4521.7  697.58  4564.9  694.13    4900  685.46  4935.1  683.42  4938.8  682.51
    4943  676.73    4950   675.9    4960   668.9    5040   668.9    5050   675.9
  5080.9  677.01    5097  688.67  5114.2  691.64  5169.4  688.43    5210   688.6
  5281.4  692.84    5331  699.44  5368.3  697.05  5396.7  699.79  5421.5  704.36
  5443.5  714.55  5457.4  717.82  5501.2  715.29  5544.4  704.21  5563.8   705.4
#Mann= 5 ,-1 , 0
  4213.1    .035       0    4900     .09       0    4950     .04       0
    5050     .09       0  5396.7    .035       0
#XS Ineff= 2 , 0
       0  4774.5  705.76  5198.4       0  714.23
Permanent Ineff=
       F       F
Bank Sta=4950,5050
Exp/Cntr=0.5,0.3

Type RM Length L Ch R = 1 ,405921  ,499,499,499
BEGIN DESCRIPTION:
Dan River 110.5
END DESCRIPTION:
XS GIS Cut Line= 3
      1647365.46       969543.24      1647143.06       969127.01
      1646644.59       968365.54
#Sta/Elev= 30
  4456.4  704.04  4481.5  702.72  4538.8  691.77  4570.1  693.15    4800  692.89
  4820.7  692.48  4860.9  685.44  4906.5   685.9    4921  679.71  4921.8  674.86
  4942.2  674.86  4945.8  666.86  5054.3  666.86  5057.9  674.86  5071.6  674.98
  5072.2  676.67  5086.1   684.1  5116.8  687.45    5150  688.34  5160.7  686.53
  5170.6  679.38  5198.4   685.1  5212.9  685.91  5234.5  685.32  5305.1  689.26
  5557.6  695.19  5579.3  700.58  5617.6   703.4  5714.2  720.24  5838.5  737.51
#Mann= 5 ,-1 , 0
  4456.4     .04       0    4800     .09       0  4942.2    .045       0
  5057.9     .09       0    5150     .04       0
Bank Sta=4942.2,5057.9
Exp/Cntr=0.3,0.1

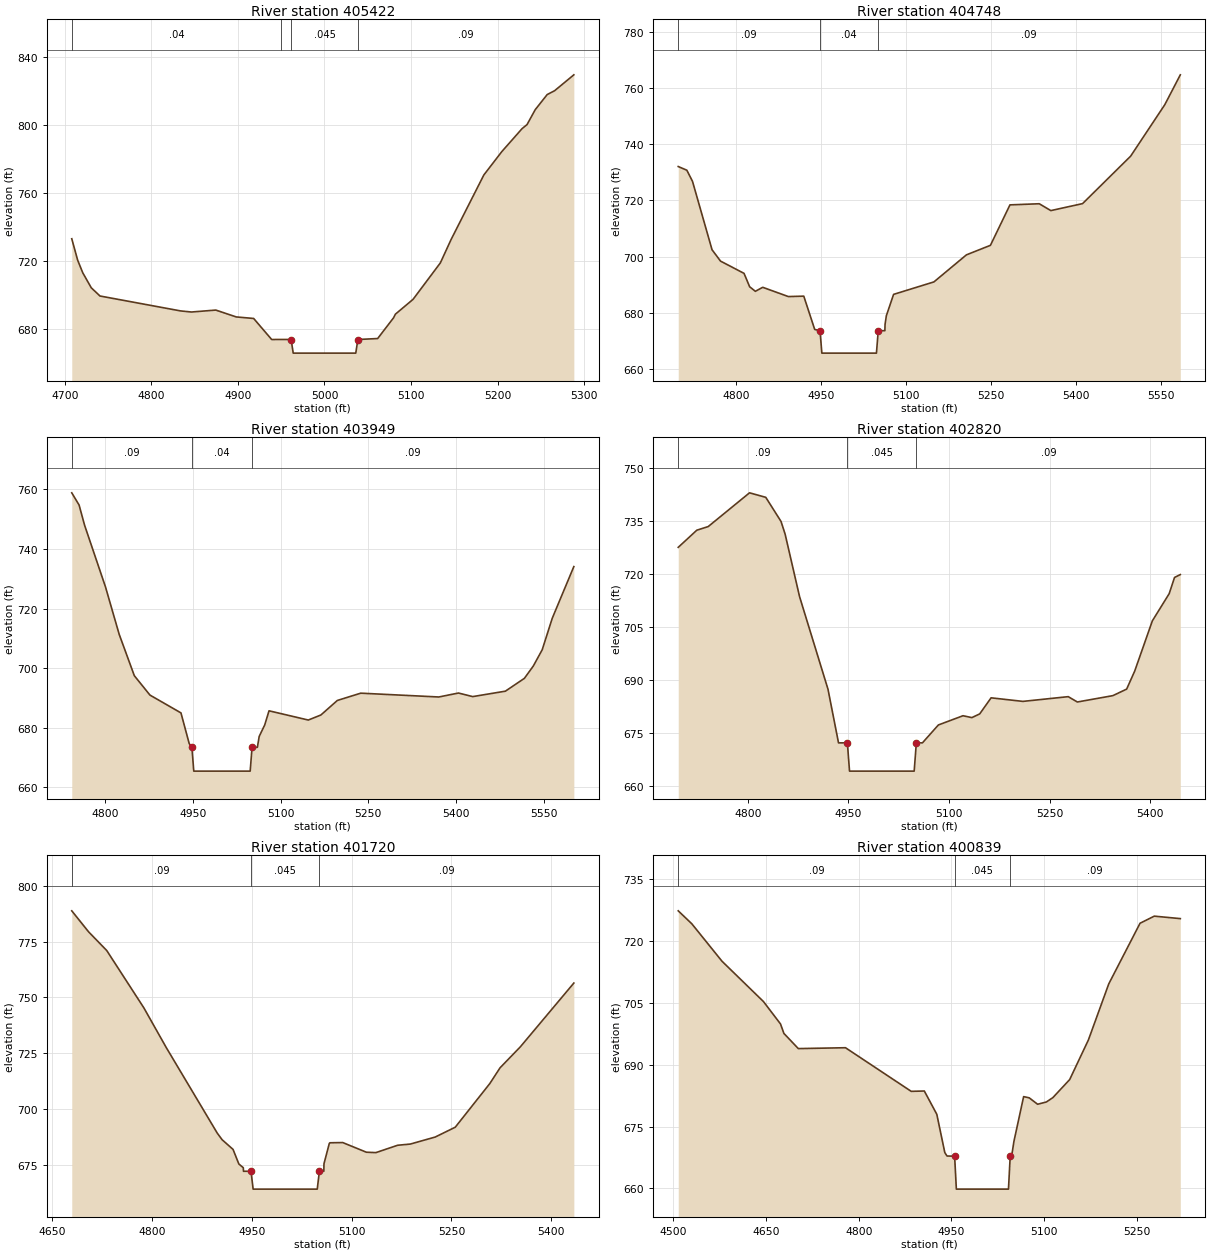
Type RM Length L Ch R = 1 ,405422  ,674,674,674
BEGIN DESCRIPTION:
Dan River 110.0
END DESCRIPTION:
XS GIS Cut Line= 3
      1647385.92       969557.66      1647507.68       969290.46
      1647685.83        969065.5
#Sta/Elev= 30
    4708  733.17  4714.8  720.62  4720.7   713.2  4730.5  704.41  4740.6  699.56
  4833.9  690.79  4846.3  690.16  4874.4   691.3  4898.1  687.27  4918.2  686.37
    4939  674.02    4950  674.03  4961.5  674.02  4963.9  666.02  5036.2  666.02
  5038.6  674.02  5061.5  674.59  5079.8  686.72    5082  688.89  5102.4   697.6
  5133.9  718.97  5146.4  732.77  5184.2  770.63  5205.1  784.43  5228.4  797.84
  5234.1   800.2  5243.6  808.99  5257.4  817.84    5266  820.11  5288.2  829.43
#Mann= 4 ,-1 , 0
    4708     .04       0    4950     .09       0  4961.5    .045       0
  5038.6     .09       0
Bank Sta=4961.5,5038.6
Exp/Cntr=0.3,0.1

Type RM Length L Ch R = 1 ,404748  ,799,799,799
BEGIN DESCRIPTION:
Dan River 109.0
END DESCRIPTION:
XS GIS Cut Line= 3
       1647785.8       970061.36      1647938.33       969813.39
      1648181.49       969269.85
#Sta/Elev= 30
  4698.2   732.1  4713.4  730.79  4723.4  726.82  4757.9  702.43  4772.9  698.38
  4814.4  694.01  4824.3  689.23  4834.4  687.61  4847.4  689.04  4892.6  685.74
  4919.9  685.88  4939.2  674.01  4948.6  673.57  4951.8  665.57  5048.2  665.57
  5051.4  673.57  5063.1  673.57  5063.4  675.78  5065.7   678.9  5078.5  686.52
  5149.7  690.96  5207.1  700.61  5249.5  704.01    5284  718.43  5335.7  718.83
  5356.2  716.39  5412.2  718.88  5497.1   735.8  5557.4  754.15  5584.8   764.8
#Mann= 3 ,-1 , 0
  4698.2     .09       0  4948.6     .04       0  5051.4     .09       0
Bank Sta=4948.6,5051.4
Exp/Cntr=0.3,0.1

Type RM Length L Ch R = 1 ,403949  ,1129,1129,1129
BEGIN DESCRIPTION:
Dan River 108.0
END DESCRIPTION:
XS GIS Cut Line= 4
      1648490.32       970531.63      1648567.68       970306.86
      1648618.23       969806.17      1648578.26       969696.21
#Sta/Elev= 30
  4743.3  758.85  4755.8  754.76  4765.2  747.98  4800.9  727.28  4824.3  711.37
  4850.2  697.46  4876.9  690.95  4929.9  684.97    4944  674.66  4948.6  673.42
  4951.8  665.42  5048.2  665.42  5051.4  673.42  5060.5  673.42  5063.6  677.07
    5073  680.91  5080.4  685.67  5147.5  682.57    5169  684.26  5197.1  689.14
  5237.1  691.59  5370.5  690.31  5404.1  691.64  5428.5  690.44  5484.3  692.26
  5516.8  696.57    5532   700.7  5547.2  706.15  5564.5  716.79  5601.3  734.09
#Mann= 3 ,-1 , 0
  4743.3     .09       0  4948.6     .04       0  5051.4     .09       0
Bank Sta=4948.6,5051.4
Exp/Cntr=0.3,0.1

Type RM Length L Ch R = 1 ,402820  ,1100,1100,1100
BEGIN DESCRIPTION:
Dan River 107.0
END DESCRIPTION:
XS GIS Cut Line= 3
      1649835.79       970531.63      1649647.59       970306.86
      1649413.68       969916.06
#Sta/Elev= 30
  4696.4  727.63  4724.1  732.48  4741.1  733.51  4802.7  743.06  4826.9  741.79
  4849.7  734.95  4855.8  731.35  4877.3  713.68  4919.7  687.46  4935.4  672.28
  4948.6  672.28  4951.8  664.28  5048.2  664.28  5051.4  672.28  5060.5  672.28
  5084.3  677.35    5121  679.96  5134.2  679.43  5145.9  680.48  5162.9  685.03
  5210.3  684.02  5277.9  685.36  5291.5  683.85  5344.5  685.65    5365   687.5
    5377   692.6  5403.3  706.81  5428.4  714.51  5436.4  719.11    5445  719.92
#Mann= 3 ,-1 , 0
  4696.4     .09       0  4948.6    .045       0  5051.4     .09       0
Bank Sta=4948.6,5051.4
Exp/Cntr=0.3,0.1

Type RM Length L Ch R = 1 ,401720  ,881,881,881
BEGIN DESCRIPTION:
Dan River 106.0
END DESCRIPTION:
XS GIS Cut Line= 3
      1650574.48       969573.09      1650291.25       969412.89
      1649923.73       969190.56
#Sta/Elev= 30
  4679.1  788.78  4704.4  779.37  4731.7  770.98  4787.5  745.29  4821.2  727.48
  4897.9  689.13  4905.2  686.18  4921.6  681.85  4930.3  675.33    4937  673.64
  4937.3  672.05  4948.6  672.05  4951.8  664.05  5048.2  664.05  5051.4  672.05
  5058.1  672.05  5058.3  675.42  5066.3  684.51  5067.2  684.82  5086.5  684.92
  5122.1  680.59  5136.4  680.42  5169.1  683.71  5188.2  684.25  5225.6   687.4
  5255.7   691.8  5307.6  711.34  5323.1  718.44  5353.6  727.84    5434  756.41
#Mann= 3 ,-1 , 0
  4679.1     .09       0  4948.6    .045       0  5051.4     .09       0
Bank Sta=4948.6,5051.4
Exp/Cntr=0.3,0.1

Type RM Length L Ch R = 1 ,400839  ,758,758,758
BEGIN DESCRIPTION:
Dan River 105.0
END DESCRIPTION:
XS GIS Cut Line= 4
      1650741.57       968891.56      1650748.44       968697.35
      1650477.19       968554.68      1650174.36       968482.64
#Sta/Elev= 30
  4508.1  727.34  4530.1  724.19  4578.9  715.11    4646  705.32  4673.5   699.9
    4679   697.6  4702.3  693.92  4778.6  694.13  4884.9  683.55  4906.1  683.63
  4926.3  677.98  4939.2  668.71  4942.8  667.86  4955.1  667.83  4957.9  659.83
  5042.2  659.83    5045  667.83  5047.3  667.83    5051   671.4  5066.7  682.27
  5075.8  681.97  5089.3  680.42  5103.5  680.97    5114  682.03  5141.2  686.41
  5171.5  696.03  5204.4  709.62    5255  724.33    5278  726.05  5320.1  725.45
#Mann= 3 ,-1 , 0
  4508.1     .09       0  4955.1    .045       0    5045     .09       0
Bank Sta=4955.1,5045
Exp/Cntr=0.3,0.1