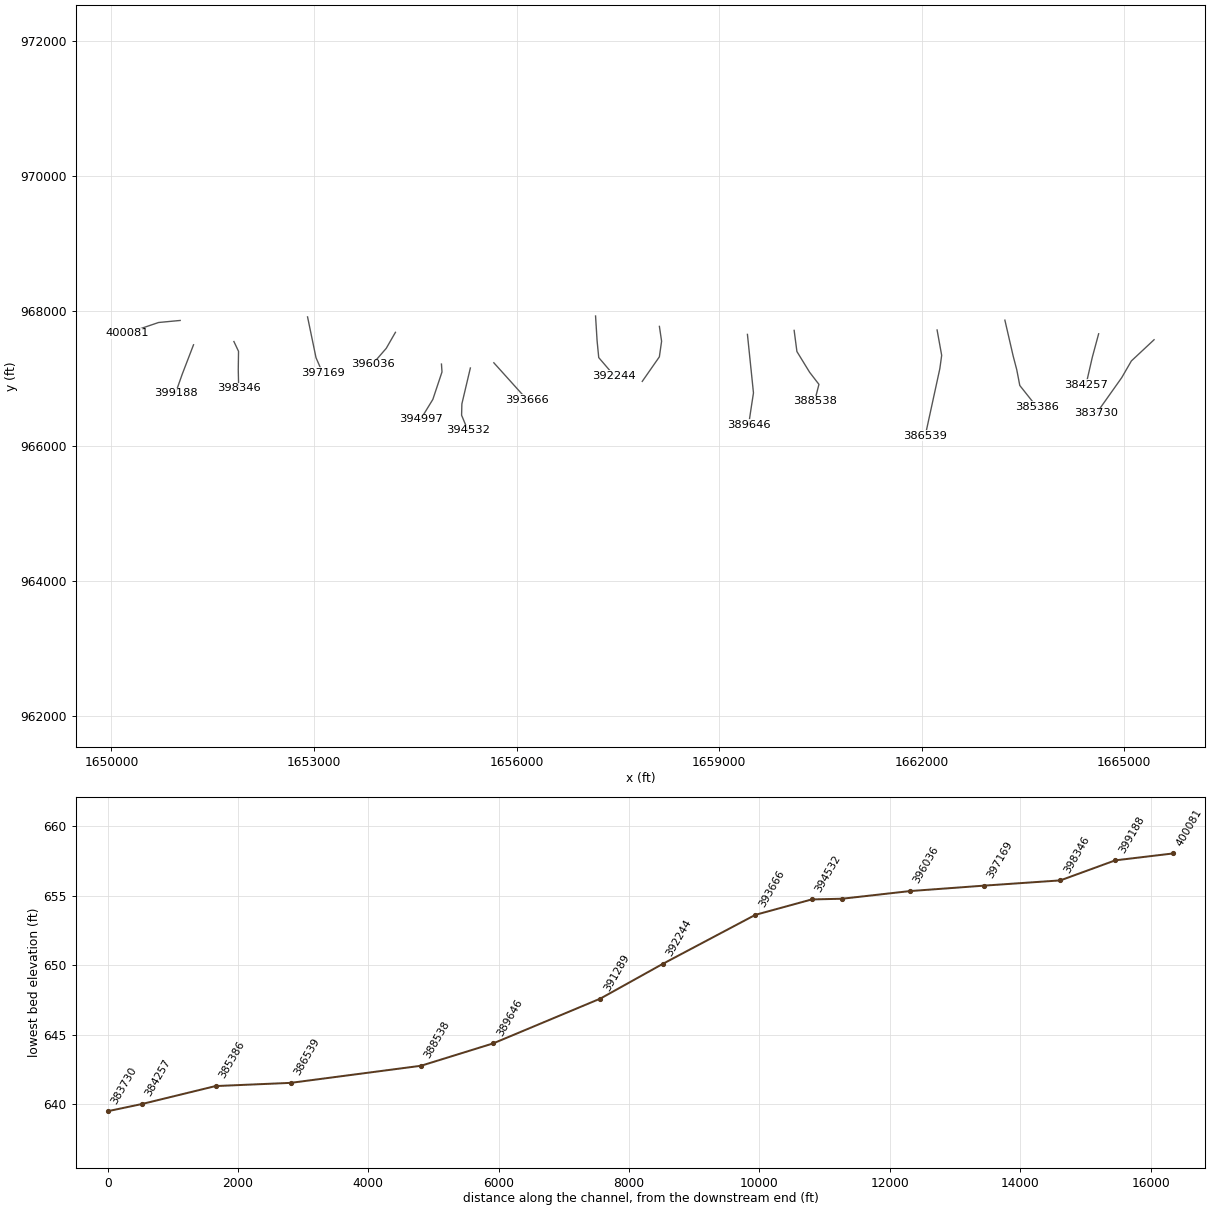
HEC-RAS study lds_dan_rvr_bctfud_lower.prj: Dan River Limited Detail Study Lower

--- lds_dan_rvr_bctfud_lower.g02 (geometry) --- (continued)

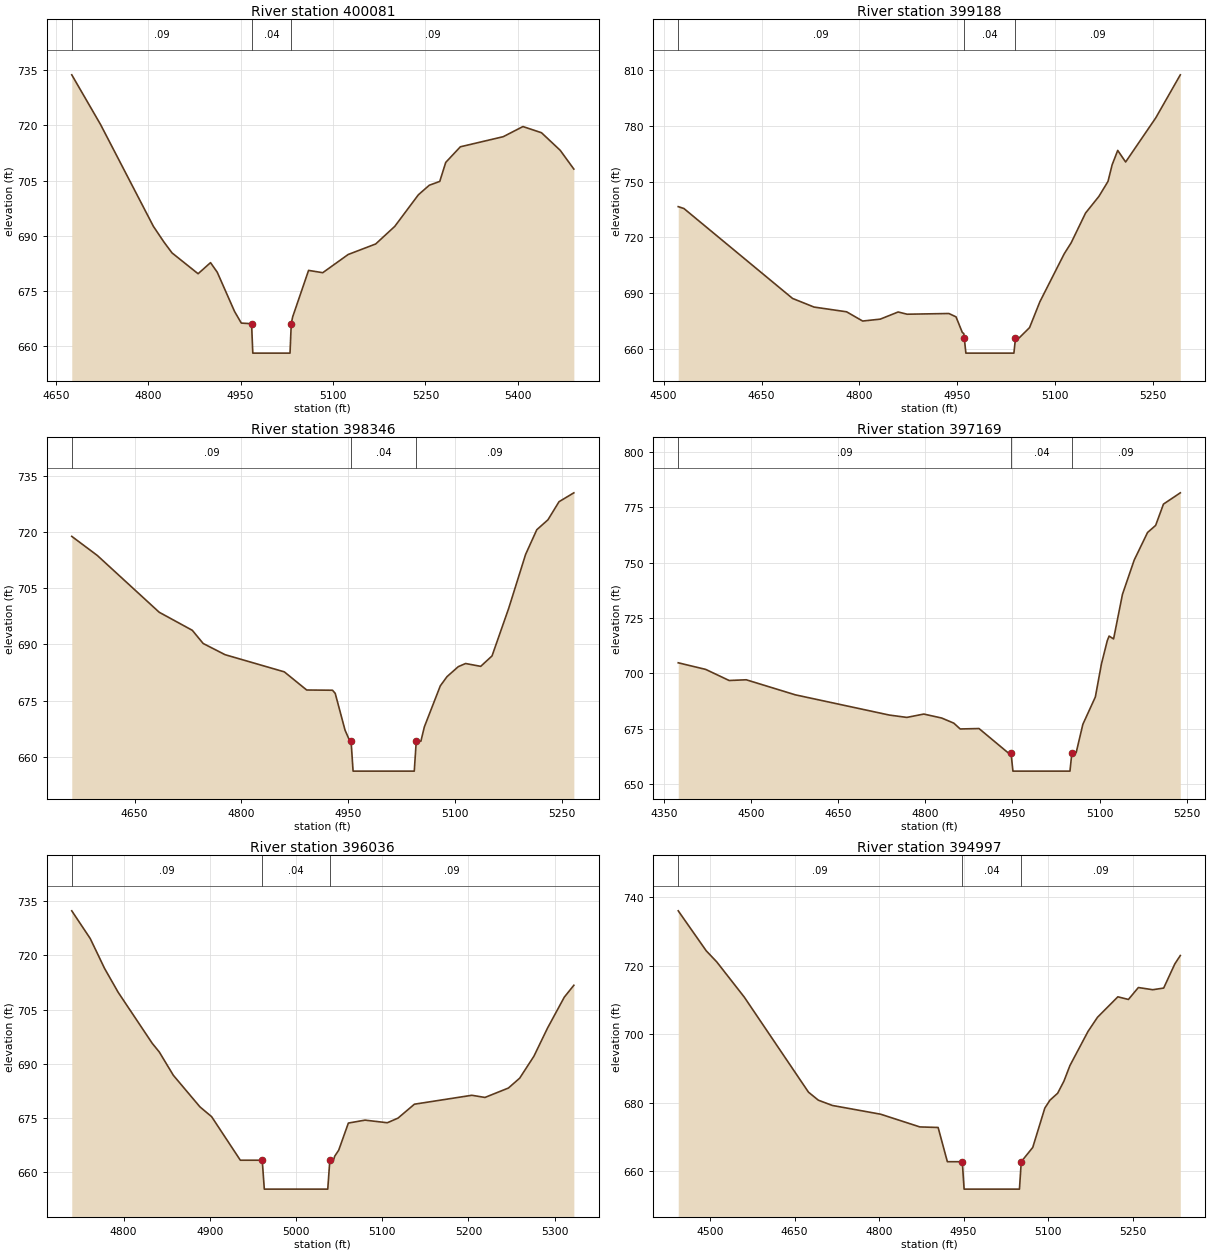
Type RM Length L Ch R = 1 ,400081  ,893,893,893
BEGIN DESCRIPTION:
Dan River 104.0
END DESCRIPTION:
XS GIS Cut Line= 3
      1651018.58       967862.67       1650698.9       967832.36
      1650231.52        967673.6
#Sta/Elev= 30
    4676  733.79  4722.6   720.3  4808.4  692.57  4825.4  688.32  4838.7  685.32
    4881  679.65  4901.2  682.67  4912.1  680.06  4940.2  669.38  4951.1  666.22
  4967.8  666.04  4969.8  658.04  5030.2  658.04  5032.2  666.04  5034.4  667.86
  5060.3  680.56  5083.3  679.93  5124.5  684.88  5169.2  687.75  5200.2  692.54
  5238.5  701.14  5256.2  703.74  5273.2  704.78  5282.9  709.95  5306.6   714.2
  5376.2  716.95  5408.2  719.71  5438.3  718.03  5468.7  713.24  5490.8  708.14
#Mann= 3 ,-1 , 0
    4676     .09       0  4967.8     .04       0  5032.2     .09       0
Bank Sta=4967.8,5032.2
Exp/Cntr=0.3,0.1

Type RM Length L Ch R = 1 ,399188  ,842,842,842
BEGIN DESCRIPTION:
Dan River 103.0
END DESCRIPTION:
XS GIS Cut Line= 3
      1651216.44       967502.12      1651049.33       967067.12
      1650948.22       966781.02
#Sta/Elev= 30
  4522.4  736.49  4531.1  735.48  4697.6  687.01  4730.5  682.37  4780.4  679.81
    4805  674.83    4832  675.86  4859.4  679.71  4873.1  678.51  4937.2  678.89
  4948.1  677.09  4957.7  668.69    4960  668.08  4960.8  665.54  4963.2  657.54
  5036.8  657.54  5039.2  665.54  5045.2  665.87  5060.8   671.3  5076.5  685.16
    5114  711.14  5124.5  716.97  5146.6  733.04  5167.1  742.04    5181   750.1
  5187.3  759.01  5195.9  766.79    5208  760.55  5254.2  784.35  5291.8  807.53
#Mann= 3 ,-1 , 0
  4522.4     .09       0  4960.8     .04       0  5039.2     .09       0
Bank Sta=4960.8,5039.2
Exp/Cntr=0.3,0.1

Type RM Length L Ch R = 1 ,398346  ,1177,1177,1177
BEGIN DESCRIPTION:
Dan River 102.0
END DESCRIPTION:
XS GIS Cut Line= 4
      1651814.43       967550.49      1651882.76       967405.48
      1651878.93       967131.49      1651884.78       966860.16
#Sta/Elev= 30
  4561.6  718.93  4597.6   713.8  4684.5  698.62    4731  693.79  4746.3  690.26
  4777.1  687.26  4860.3  682.67  4891.8  677.81  4928.1  677.75  4931.9  676.91
  4945.7  667.07  4952.5  664.11  4954.2   664.1    4957   656.1    5043   656.1
  5045.8   664.1  5052.3   664.1  5057.2  667.95  5079.6  678.92  5089.1   681.4
  5104.9  684.06  5115.1   684.9  5136.4  684.14  5152.3  686.93  5175.7  699.65
  5199.5   714.1  5215.2   720.7  5230.9  723.36  5246.5  728.21  5267.3  730.58
#Mann= 3 ,-1 , 0
  4561.6     .09       0  4954.2     .04       0  5045.8     .09       0
Bank Sta=4954.2,5045.8
Exp/Cntr=0.3,0.1

Type RM Length L Ch R = 1 ,397169  ,1133,1133,1133
BEGIN DESCRIPTION:
Dan River 101.0
END DESCRIPTION:
XS GIS Cut Line= 3
      1652904.88       967915.44      1653030.36       967310.28
      1653129.12       967084.41
#Sta/Elev= 30
  4374.6  704.72  4421.9  701.73  4462.3  696.71  4491.7  697.04  4576.1  690.24
  4738.1  681.08  4768.2  680.02  4797.4  681.53  4828.2  679.74  4849.1  677.42
  4860.1  674.79  4892.5  674.98  4943.9  663.73  4947.7  663.72  4950.9  655.72
  5049.1  655.72  5052.3  663.72  5059.8  664.11  5071.3  676.89  5092.8  689.25
  5103.3  704.22  5113.3  714.68  5116.5  716.81  5124.2  715.52  5139.5  735.69
  5159.7  751.18  5182.7  763.66  5196.6  766.86  5210.1   776.5  5239.1   781.6
#Mann= 3 ,-1 , 0
  4374.6     .09       0  4947.7     .04       0  5052.3     .09       0
Bank Sta=4947.7,5052.3
Exp/Cntr=0.3,0.1

Type RM Length L Ch R = 1 ,396036  ,1039,1039,1039
BEGIN DESCRIPTION:
Dan River 100.0
END DESCRIPTION:
XS GIS Cut Line= 3
      1654206.38       967686.79      1654070.07       967449.36
      1653867.81       967216.32
#Sta/Elev= 30
  4739.9  732.34  4761.3  724.68  4777.9  716.42  4793.7   709.8  4833.2  695.69
  4841.4  693.28  4857.7  686.83  4888.6  678.08  4902.1  675.38  4935.4  663.33
  4960.8  663.33  4963.2  655.33  5036.8  655.33  5039.2  663.33  5043.4  663.34
  5044.9  664.45  5049.5  666.11  5060.7  673.61    5080  674.42  5105.9   673.7
  5118.2  674.97  5137.3  678.83  5203.9   681.3  5219.1   680.7  5246.3   683.3
  5259.4  686.04  5275.9  692.11  5291.6  699.86  5311.1  708.44  5322.2  711.74
#Mann= 3 ,-1 , 0
  4739.9     .09       0  4960.8     .04       0  5039.2     .09       0
Bank Sta=4960.8,5039.2
Exp/Cntr=0.3,0.1

Type RM Length L Ch R = 1 ,394997  ,465,465,465
BEGIN DESCRIPTION:
Dan River 99.0
END DESCRIPTION:
XS GIS Cut Line= 4
      1654887.91       967216.32      1654895.82       967099.36
       1654760.4       966693.08      1654580.12       966398.48
#Sta/Elev= 30
  4443.7  735.98  4493.4  724.31    4512  721.09  4560.9   710.8  4674.8  683.07
  4692.3  680.73  4717.2  679.19  4802.8  676.64  4872.4  672.93  4904.8  672.77
  4921.2  662.78  4947.7  662.78  4950.9  654.78  5049.1  654.78  5052.3  662.78
  5072.7  666.95  5094.1  678.42  5103.2  680.73  5116.8  682.74    5128  686.28
  5138.7  690.85  5170.7  700.78  5187.6  704.93  5223.7  710.89  5242.4  710.12
  5260.1   713.6  5285.7  712.96    5305  713.45  5324.7  720.47  5334.5  722.94
#Mann= 3 ,-1 , 0
  4443.7     .09       0  4947.7     .04       0  5052.3     .09       0
Bank Sta=4947.7,5052.3
Exp/Cntr=0.3,0.1

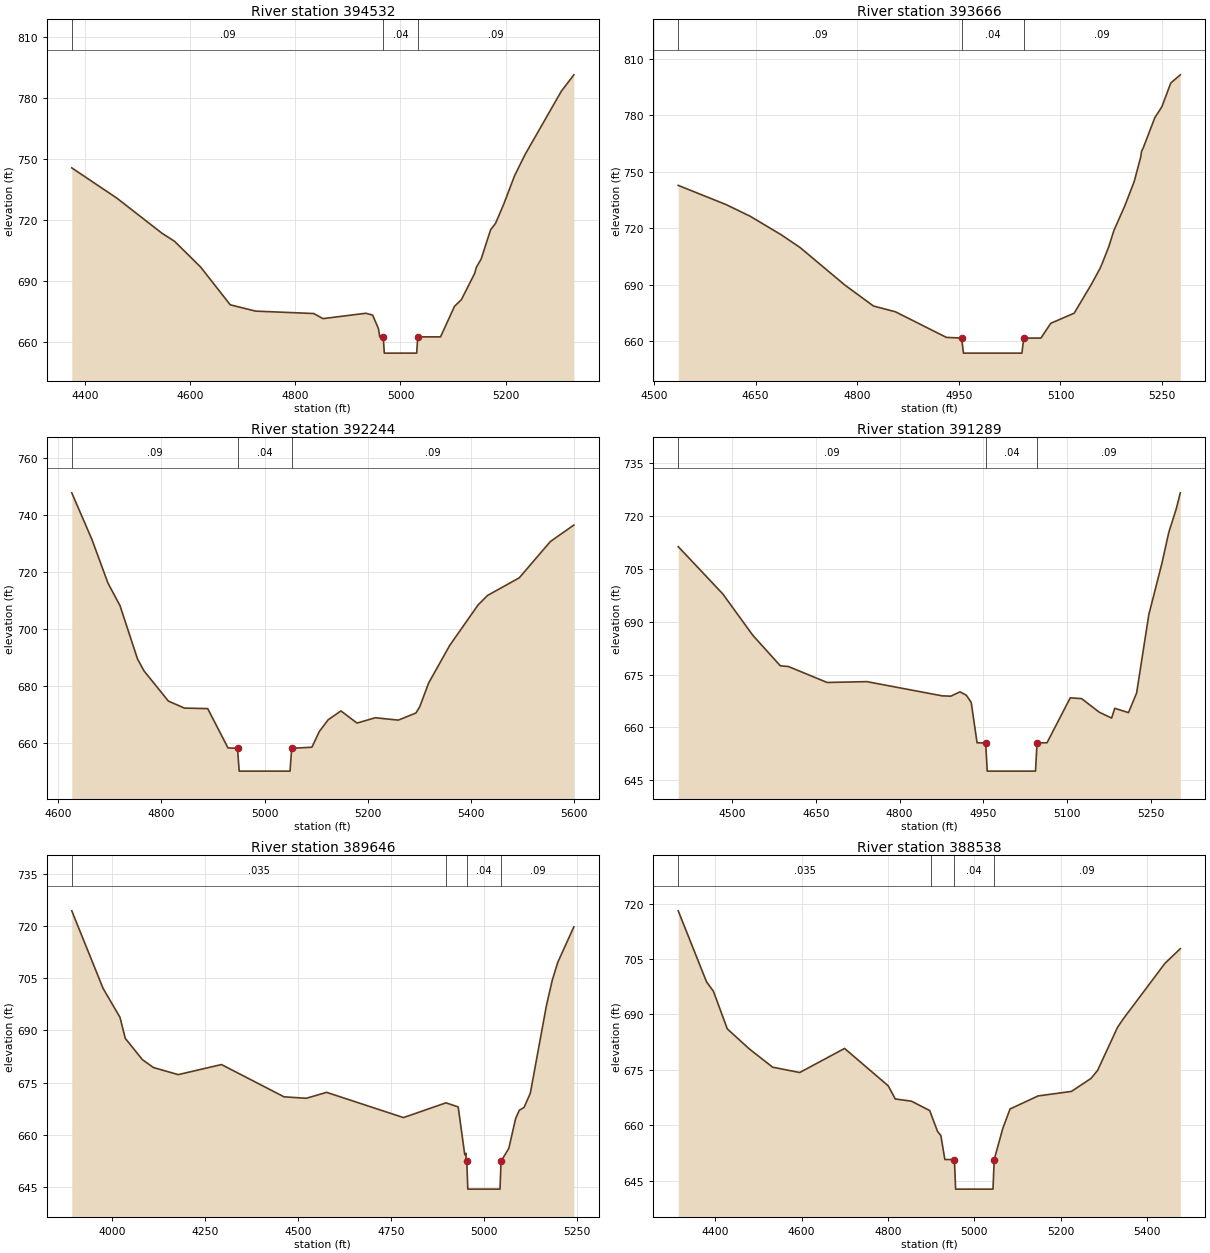
Type RM Length L Ch R = 1 ,394532  ,866,866,866
BEGIN DESCRIPTION:
Dan River 98.5
END DESCRIPTION:
XS GIS Cut Line= 4
      1655315.97       967158.51      1655190.24       966626.24
      1655186.05       966458.59      1655278.25       966236.47
#Sta/Elev= 30
  4374.6  745.86  4460.4  730.97  4546.2  713.72  4570.2  709.72  4619.8  697.06
  4676.1   678.5  4724.3   675.4  4835.1  674.21  4852.5   671.7  4934.1  674.34
    4947  673.44    4958  666.82  4960.6  662.73  4967.2  662.73  4969.2  654.73
  5030.8  654.73  5032.8  662.73  5076.2  662.73  5102.8  677.79  5115.8  681.01
    5141  693.88  5144.3  696.93  5153.5  701.05  5171.5  715.47  5180.8  718.55
  5196.4     728    5217  741.98  5236.8  752.33  5305.9  783.52  5329.8  791.63
#Mann= 3 ,-1 , 0
  4374.6     .09       0  4967.2     .04       0  5032.8     .09       0
Bank Sta=4967.2,5032.8
Exp/Cntr=0.3,0.1

Type RM Length L Ch R = 1 ,393666  ,1422,1422,1422
BEGIN DESCRIPTION:
Dan River 98.0
END DESCRIPTION:
XS GIS Cut Line= 3
      1655663.72       967235.43      1655969.72       966895.48
      1656159.45       966684.62
#Sta/Elev= 30
  4535.9   742.7  4606.5  732.51    4642  726.32  4687.5  716.56  4715.7  709.71
  4781.9  689.75    4824  678.64  4856.5  675.57  4931.7  661.97  4954.1  661.62
  4956.9  653.62  5043.1  653.62  5045.9  661.62  5071.2  661.62  5085.7  669.46
  5120.3  674.85  5145.9  690.32  5158.7   698.8  5162.1  701.69  5171.4  710.21
    5179  718.85  5195.2  732.01  5208.8  744.69  5218.4  757.64  5219.7  760.77
  5222.5  762.89  5239.3  778.67  5249.7  784.44  5262.8  797.05  5276.9  801.41
#Mann= 3 ,-1 , 0
  4535.9     .09       0  4954.1     .04       0  5045.9     .09       0
Bank Sta=4954.1,5045.9
Exp/Cntr=0.3,0.1

Type RM Length L Ch R = 1 ,392244  ,955,955,955
BEGIN DESCRIPTION:
Dan River 97.0
END DESCRIPTION:
XS GIS Cut Line= 4
      1657169.94       967928.63      1657192.67       967560.59
      1657217.01       967312.54      1657448.35       967042.64
#Sta/Elev= 30
  4626.1  747.64  4665.1  731.33  4696.3  715.99  4719.7  708.07  4753.6  689.39
  4766.2  685.23  4813.4  674.65  4844.5  672.19  4889.7     672    4929  658.23
  4947.5  658.09  4950.7  650.09  5049.3  650.09  5052.5  658.09  5091.7  658.47
  5106.2  664.03  5123.4  668.12    5148  671.19  5179.2  666.94  5214.6   668.8
  5259.2  667.97  5293.3  670.45  5300.9  672.68    5318  680.96    5359  694.18
  5413.6  708.27  5432.1  711.65  5493.8  717.85  5553.9  730.54  5599.6  736.35
#Mann= 3 ,-1 , 0
  4626.1     .09       0  4947.5     .04       0  5052.5     .09       0
Bank Sta=4947.5,5052.5
Exp/Cntr=0.3,0.1

Type RM Length L Ch R = 1 ,391289  ,1643,1643,1643
BEGIN DESCRIPTION:
Dan River 96.0
END DESCRIPTION:
XS GIS Cut Line= 4
      1658115.28       967774.73      1658147.88        967554.9
      1658114.83       967323.56      1657861.46       966960.02
#Sta/Elev= 30
  4403.5  711.31  4483.3  697.89  4537.1  686.14  4586.3  677.49  4600.7  677.29
  4670.1  672.76  4741.3     673  4876.2  668.96  4891.7  668.88  4907.9   670.1
  4919.4  669.14  4928.1  667.09  4938.6  655.64    4954   655.6  4956.8   647.6
  5043.2   647.6    5046   655.6  5063.8  655.65  5105.4  668.39  5125.8  668.18
  5157.3  664.33  5179.5  662.65  5185.1  665.43  5209.7  664.21  5224.3  669.78
  5246.1  692.01  5269.5  706.52  5281.8  715.32  5295.4  722.12  5302.5  726.58
#Mann= 3 ,-1 , 0
  4403.5     .09       0    4954     .04       0    5046     .09       0
Bank Sta=4954,5046
Exp/Cntr=0.3,0.1

Type RM Length L Ch R = 1 ,389646  ,1108,1108,1108
BEGIN DESCRIPTION:
Dan River 95.0
END DESCRIPTION:
XS GIS Cut Line= 4
      1659418.94       967656.23      1659508.38       966789.27
      1659474.07        966566.5      1659436.78       966315.57
#Sta/Elev= 30
  3891.3  724.32  3975.6  702.03    4021  693.74  4035.2   687.7  4081.2  681.58
    4111  679.31  4177.6  677.27    4294  680.16  4462.2   670.9    4522  670.47
  4576.8  672.18  4783.6  664.93  4897.9  669.17  4930.8  667.99  4948.5  654.24
  4951.7  654.67  4952.3  652.38  4953.9  652.38  4956.7  644.38  5043.3  644.38
  5046.1  652.38    5067   656.1  5085.3  664.66  5095.1  667.03    5108  667.85
  5124.8  671.92  5168.1  697.08  5183.9   704.4  5198.6  709.51  5241.9  719.72
#Mann= 4 ,-1 , 0
  3891.3    .035       0  4897.9     .09       0  4953.9     .04       0
  5046.1     .09       0
Bank Sta=4953.9,5046.1
Exp/Cntr=0.3,0.1

Type RM Length L Ch R = 1 ,388538  ,1999,1999,1999
BEGIN DESCRIPTION:
Dan River 94.0
END DESCRIPTION:
XS GIS Cut Line= 5
      1660110.66        967715.7      1660151.77       967402.16
      1660339.43       967095.73      1660477.81       966915.96
      1660413.08       966663.31
#Sta/Elev= 30
    4314  718.02  4379.7  698.79  4395.5  696.28  4427.7   686.1  4478.6  680.69
  4532.8  675.74  4595.5   674.3  4699.4  680.81  4800.5  670.71  4816.9  667.15
  4854.3  666.55  4896.8  664.01    4900  662.95  4914.8  658.39  4922.5  657.25
  4931.8  650.77  4953.9  650.77  4956.7  642.77  5043.3  642.77  5046.1  650.77
    5066  659.18  5082.8  664.44  5147.8  667.97    5225  669.19  5270.5  672.71
  5285.6  674.86  5331.8  686.51  5344.1  688.64  5441.7  703.82  5477.3  707.78
#Mann= 4 ,-1 , 0
    4314    .035       0    4900     .09       0  4953.9     .04       0
  5046.1     .09       0
Bank Sta=4953.9,5046.1
Exp/Cntr=0.3,0.1

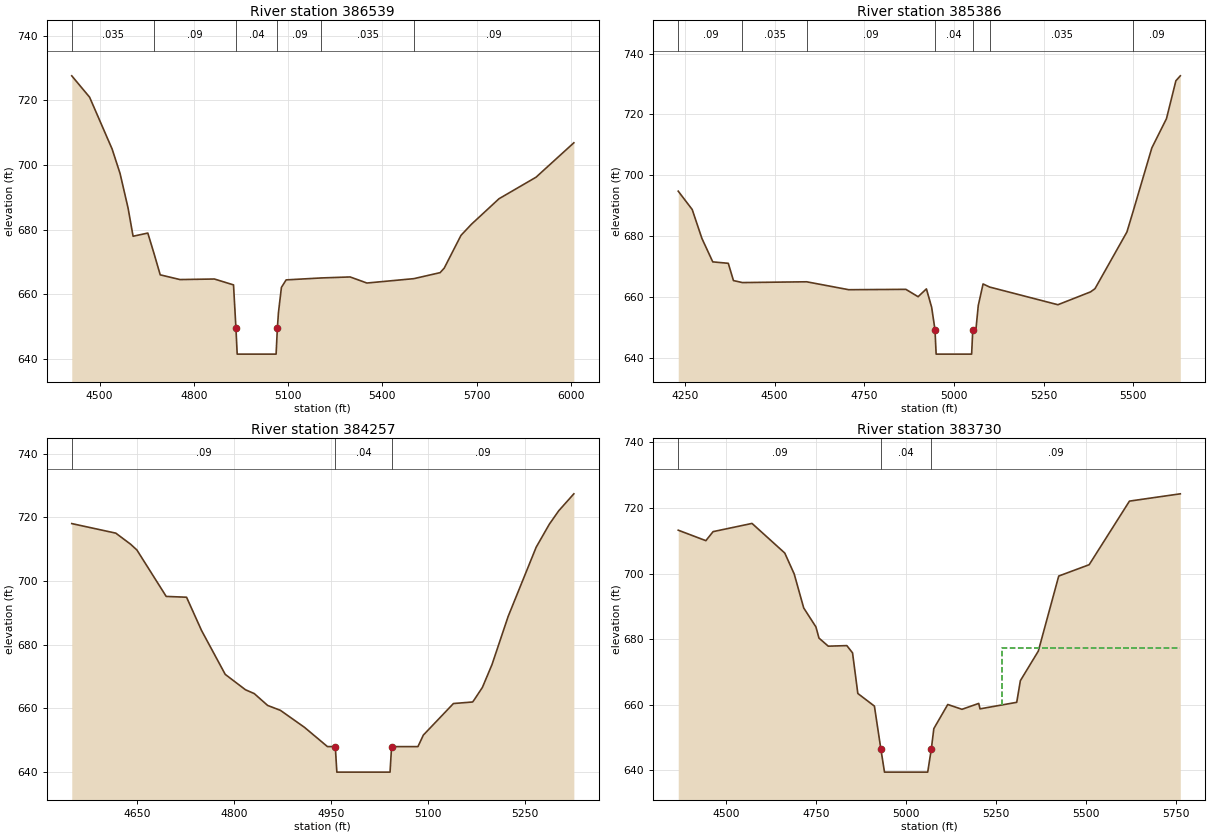
Type RM Length L Ch R = 1 ,386539  ,1153,1153,1153
BEGIN DESCRIPTION:
Dan River 93.0
END DESCRIPTION:
XS GIS Cut Line= 4
      1662227.54       967721.75      1662295.49       967345.59
      1662267.95        967147.3      1662052.15       966155.26
#Sta/Elev= 30
  4411.7  727.61  4468.4  721.01  4540.1  704.97  4565.3  697.43  4590.8  686.75
  4606.8     678  4653.7  678.98  4672.9  672.83  4693.2  666.06    4756   664.6
 4865.54  664.77  4926.4  662.95  4934.1  649.54  4938.1  641.54  5061.9  641.54
  5065.9  649.54  5069.3  654.33  5078.8  662.17  5093.8   664.5  5205.7   665.1
  5297.4  665.41  5350.8  663.53    5500  664.88  5583.8  666.74  5596.9  668.15
  5650.2  678.27  5683.5  681.71  5771.2   689.6  5888.9  696.25  6009.3   706.9
#Mann= 6 ,-1 , 0
  4411.7    .035       0  4672.9     .09       0  4934.1     .04       0
  5065.9     .09       0  5205.7    .035       0    5500     .09       0
Bank Sta=4934.1,5065.9
Exp/Cntr=0.3,0.1

Type RM Length L Ch R = 1 ,385386  ,1129,1129,1129
BEGIN DESCRIPTION:
Dan River 92.0
END DESCRIPTION:
XS GIS Cut Line= 5
      1663231.55       967866.91      1663353.05       967340.08
      1663407.52       967131.49      1663452.19       966899.43
      1663705.57       966579.96
#Sta/Elev= 30
  4231.2  694.81  4270.1   688.8  4297.2  679.31  4327.5   671.6  4370.8  671.13
  4385.2  665.46  4410.3   664.8  4589.3  665.06  4706.7  662.46  4866.1  662.58
  4900.2  660.16  4923.4  662.73    4938  656.68  4947.3  649.31  4950.5  641.31
  5049.5  641.31  5052.7  649.31  5061.4  649.31    5068  657.27  5081.4  664.35
    5100  663.32  5290.1  657.53  5381.1  661.74  5393.5  662.79  5482.6  681.41
    5500  688.23  5552.1  709.02  5592.9  718.62  5619.2  731.06  5631.5  732.68
#Mann= 7 ,-1 , 0
  4231.2     .09       0  4410.3    .035       0  4589.3     .09       0
  4947.3     .04       0  5052.7     .09       0    5100    .035       0
    5500     .09       0
Bank Sta=4947.3,5052.7
Exp/Cntr=0.3,0.1

Type RM Length L Ch R = 1 ,384257  ,527,527,527
BEGIN DESCRIPTION:
Dan River 91.0
END DESCRIPTION:
XS GIS Cut Line= 3
      1664619.91       967665.06      1664526.27       967318.05
      1664432.64       966910.45
#Sta/Elev= 30
  4548.2  718.02  4616.4  715.02  4639.3  711.55  4649.1  709.73  4694.5  695.16
    4726  694.91  4749.2  684.48  4785.9   670.7  4817.2  665.88  4830.9  664.66
  4851.6  660.95  4871.4  659.41  4908.6  654.09  4944.2  648.04  4956.4  648.02
  4958.8  640.02  5041.2  640.02  5043.6  648.02  5084.4  648.03  5092.8  651.65
  5139.4  661.55  5169.1  662.03  5171.6  662.73  5184.2  666.58  5199.1  673.76
  5224.1  688.86  5267.6  710.63  5287.9  717.82  5302.5  722.04  5325.9  727.36
#Mann= 3 ,-1 , 0
  4548.2     .09       0  4956.4     .04       0  5043.6     .09       0
Bank Sta=4956.4,5043.6
Exp/Cntr=0.5,0.3

Type RM Length L Ch R = 1 ,383730  ,153,153,153
BEGIN DESCRIPTION:
Dodgetown Rd. SR-1695 - US
END DESCRIPTION:
XS GIS Cut Line= 4
      1665440.62       967576.93      1665104.63       967262.97
      1664961.42        967015.1      1664586.86       966486.32
#Sta/Elev= 30
  4367.3  713.22    4444  710.03  4464.1  712.78  4572.2  715.28  4663.1  706.26
  4689.3  699.88  4715.7  689.53  4749.6  683.75  4758.1  680.34  4783.9  677.88
  4835.5  678.05  4851.3  675.84    4866  663.46    4912  659.62    4930   646.5
    4940   639.5    5060   639.5    5070   646.5    5077  652.76  5115.7  660.11
  5155.2  658.64 5201.66  660.44  5205.3  658.78 5307.19  660.77  5317.3  667.37
  5367.1  676.37  5423.8  699.25  5508.3   702.7  5620.2  722.08  5761.4   724.3
#Mann= 3 ,-1 , 0
  4367.3     .09       0    4930     .04       0    5070     .09       0
#XS Ineff= 2 , 0
       0    4735  677.97    5265       0  677.28
Permanent Ineff=
       F       F
Bank Sta=4930,5070
Exp/Cntr=0.5,0.3