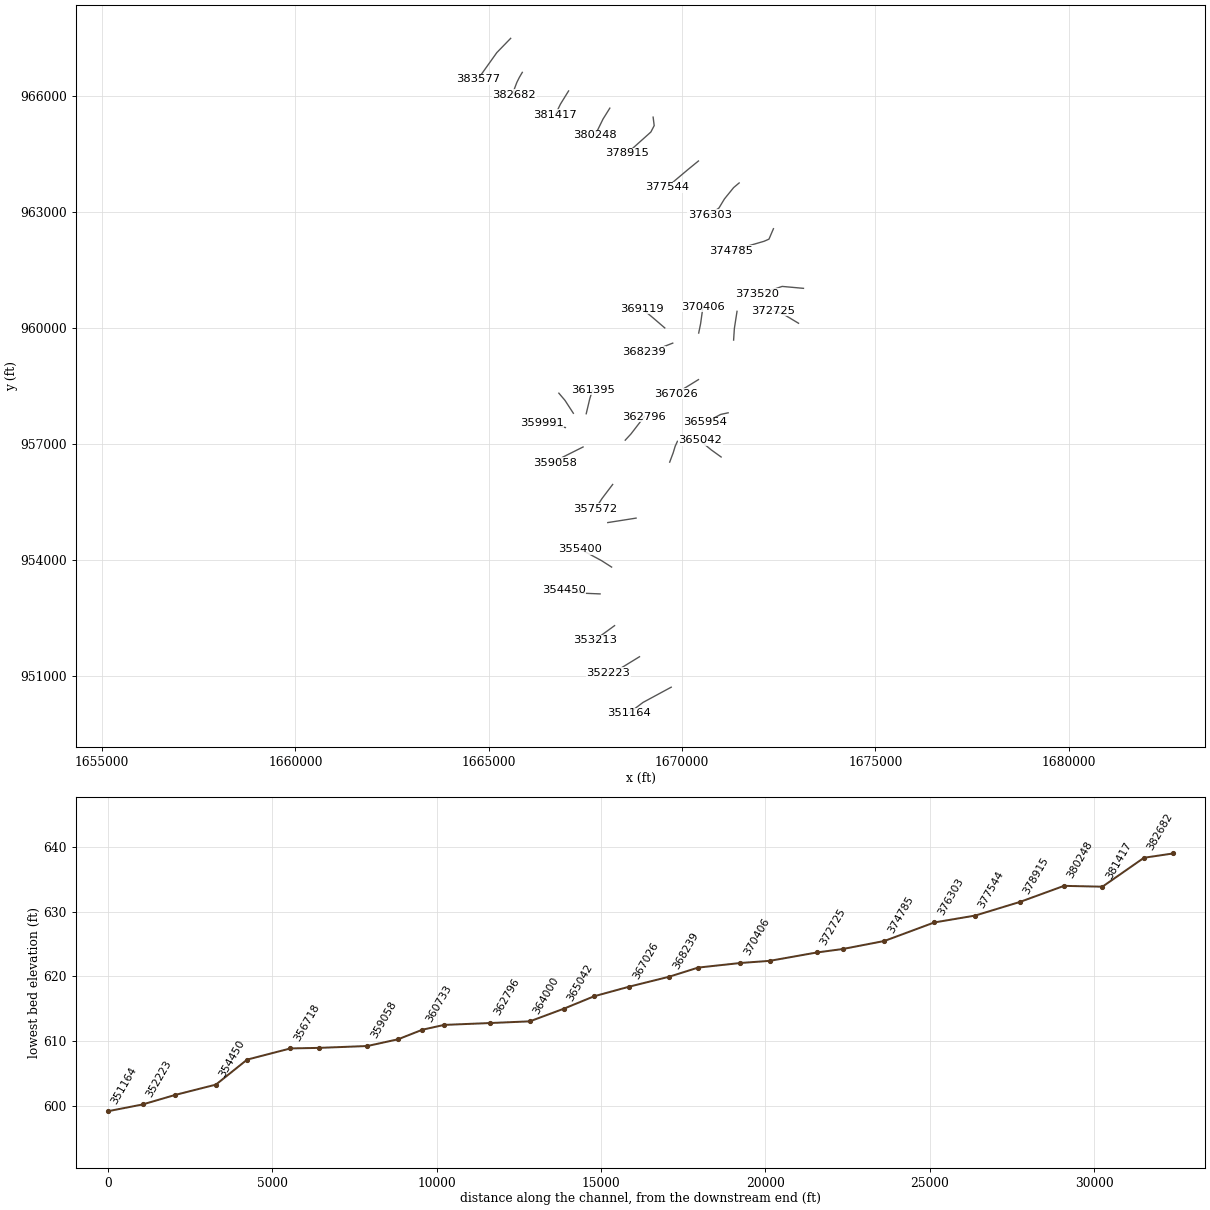
HEC-RAS study lds_dan_rvr_bctfud_lower.prj: Dan River Limited Detail Study Lower

--- lds_dan_rvr_bctfud_lower.g02 (geometry) --- (continued)

Type RM Length L Ch R = 3 ,383632  ,,,
BEGIN DESCRIPTION:
Dodgetown Rd. SR-1695
Structure ID: Dodgetown Road
Approximate Survey Structure
END DESCRIPTION:
Bridge Culvert--1,0,-1,-1, 0
Deck Dist Width WeirC Skew NumUp NumDn MinLoCord MaxHiCord MaxSubmerge Is_Ogee
80,36,3,0, 60, 60, , , , 0, 1,1,,
  4435.2  4443.9  4453.5  4462.4  4481.4    4496  4499.5    4501  4516.7  4535.6
  4571.9  4590.9  4601.6  4614.1  4627.8  4643.5  4651.4  4655.1  4670.7  4800.7
    4815    4815    5185    5185    5216  5216.3  5279.9  5294.7  5311.6    5328
  5361.7  5377.3  5382.4  5387.7  5410.2  5456.6  5462.9  5464.1  5465.9  5477.9
  5492.3  5528.9  5550.9  5556.3  5570.6  5574.2  5585.7  5602.7    5631  5637.2
  5663.3  5673.2  5690.3  5692.8  5705.6  5730.2  5737.3  5741.8  5754.7  5764.4
  681.52  681.43  680.95  681.17  680.82  680.83   680.4  680.78  680.45  680.65
     680  679.97  679.63  679.75  679.28  679.19  678.82  679.06     679  677.05
   677.5   677.5   677.5   677.5   677.5  677.32  677.38  677.23  677.88  678.06
  679.42  680.21  680.29  680.83  681.83  684.62  684.88  685.28  685.15  685.98
  687.21  689.16  690.91  691.76  692.41  692.73  692.97  694.41  696.37  696.97
  698.61  698.96  700.11  700.39  700.79  702.97  703.31  703.74  704.02  705.01
   619.5   619.5   619.5   619.5   619.5   619.5   619.5   619.5   619.5   619.5
   619.5   619.5   619.5   619.5   619.5   619.5   619.5   619.5   619.5   619.5
   619.5     675     675   619.5   619.5   619.5   619.5   619.5   619.5   619.5
   619.5   619.5   619.5   619.5   619.5   619.5   619.5   619.5   619.5   619.5
   619.5   619.5   619.5   619.5   619.5   619.5   619.5   619.5   619.5   619.5
   619.5   619.5   619.5   619.5   619.5   619.5   619.5   619.5   619.5   619.5
  4435.2  4443.9  4453.5  4462.4  4481.4    4496  4499.5    4501  4516.7  4535.6
  4571.9  4590.9  4601.6  4614.1  4627.8  4643.5  4651.4  4655.1  4670.7  4800.7
    4815    4815    5185    5185    5216  5216.3  5279.9  5294.7  5311.6    5328
  5361.7  5377.3  5382.4  5387.7  5410.2  5456.6  5462.9  5464.1  5465.9  5477.9
  5492.3  5528.9  5550.9  5556.3  5570.6  5574.2  5585.7  5602.7    5631  5637.2
  5663.3  5673.2  5690.3  5692.8  5705.6  5730.2  5737.3  5741.8  5754.7  5764.4
  681.52  681.43  680.95  681.17  680.82  680.83   680.4  680.78  680.45  680.65
     680  679.97  679.63  679.75  679.28  679.19  678.82  679.06     679  677.05
   677.5   677.5   677.5   677.5   677.5  677.32  677.38  677.23  677.88  678.06
  679.42  680.21  680.29  680.83  681.83  684.62  684.88  685.28  685.15  685.98
  687.21  689.16  690.91  691.76  692.41  692.73  692.97  694.41  696.37  696.97
  698.61  698.96  700.11  700.39  700.79  702.97  703.31  703.74  704.02  705.01
   619.5   619.5   619.5   619.5   619.5   619.5   619.5   619.5   619.5   619.5
   619.5   619.5   619.5   619.5   619.5   619.5   619.5   619.5   619.5   619.5
   619.5     675     675   619.5   619.5   619.5   619.5   619.5   619.5   619.5
   619.5   619.5   619.5   619.5   619.5   619.5   619.5   619.5   619.5   619.5
   619.5   619.5   619.5   619.5   619.5   619.5   619.5   619.5   619.5   619.5
   619.5   619.5   619.5   619.5   619.5   619.5   619.5   619.5   619.5   619.5
Pier Skew, UpSta & Num, DnSta & Num=  ,4894.3, 2 ,4894.3, 2 , 0 , 0 , 0 ,0,0
       2       2
  662.01     675
       2       2
  657.39     675
Pier Skew, UpSta & Num, DnSta & Num=  ,4947.1, 2 ,4947.1, 2 , 0 , 0 , 0 ,0,0
       2       2
     613     675
       2       2
  612.75     675
Pier Skew, UpSta & Num, DnSta & Num=  ,5000, 2 ,5000, 2 , 0 , 0 , 0 ,0,0
       2       2
     613     675
       2       2
  612.75     675
Pier Skew, UpSta & Num, DnSta & Num=  ,5052.9, 2 ,5052.9, 2 , 0 , 0 , 0 ,0,0
       2       2
     613     675
       2       2
  612.75     675
Pier Skew, UpSta & Num, DnSta & Num=  ,5105.7, 2 ,5105.7, 2 , 0 , 0 , 0 ,0,0
       2       2
   658.8     675
       2       2
  662.03     675
Abutment Skew #Up #Dn= , 2 , 2
    4815    4880
     674  662.04
    4815    4880
     674  659.73
Abutment Skew #Up #Dn= , 2 , 2
    5120    5185
  660.11     675
    5120    5185
  660.06     674
BR Coef= 1 , 1 , 0 ,1.25, 0 ,,,0.8,0,2,0,
WSPro=,,,, 1 ,,,, 0 ,,,, 0 ,,,,-1 ,-1 ,-1 , 0 , 0 , 0 , 0 , 0
BC Design=,, 0 ,, 0 ,,,,,,
BC HTab HWMax=724.54

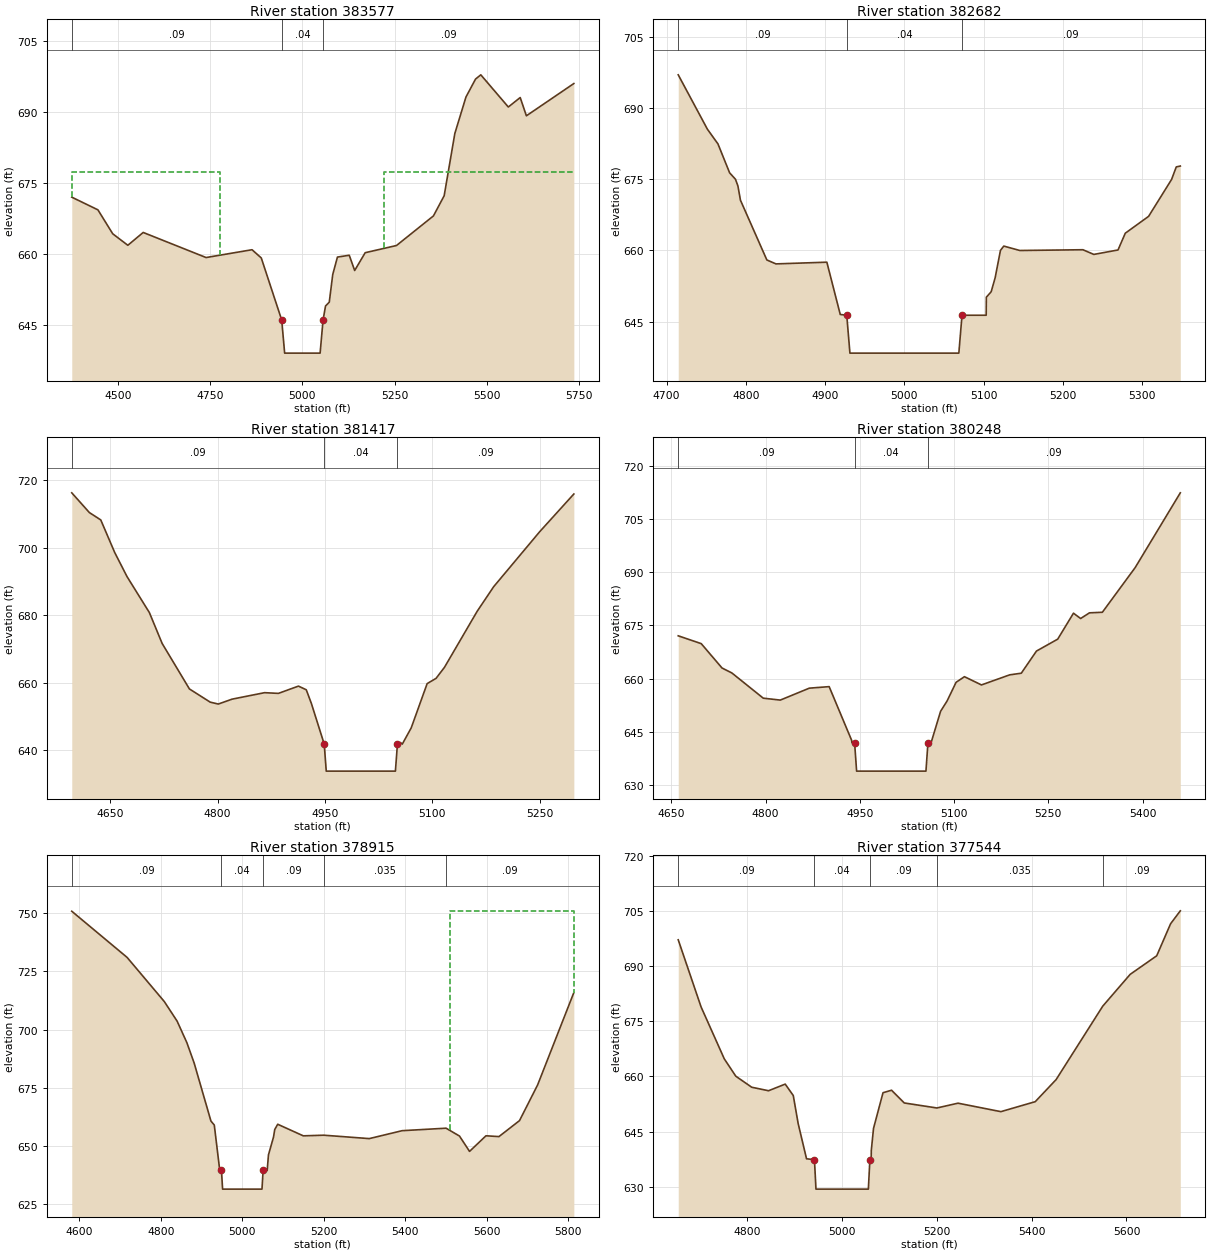
Type RM Length L Ch R = 1 ,383577  ,895,895,895
BEGIN DESCRIPTION:
Dodgetown Rd. SR-1695 - DS
END DESCRIPTION:
XS GIS Cut Line= 3
      1665567.31        967488.8      1665209.28       967119.76
      1664719.06       966431.24
#Sta/Elev= 30
  4375.6  671.96  4446.4  669.28  4486.5  664.22  4527.4  661.79    4569   664.5
  4739.3   659.2  4863.7  660.85  4888.7  659.11    4944     646    4952     639
    5048     639    5056     646  5062.7  648.96  5072.8  649.77  5082.2  655.62
 5094.95   659.3  5126.9  659.68  5141.6  656.46    5170  660.22  5254.8  661.74
  5354.9     668  5383.9  672.26  5412.8  685.42  5442.9  693.12  5468.8  696.91
  5483.1  697.81  5557.6  691.01  5589.8  693.01  5606.5  689.15    5735  695.97
#Mann= 3 ,-1 , 0
  4375.6     .09       0    4944     .04       0    5056     .09       0
#XS Ineff= 2 , 0
       0    4778  677.34    5222       0  677.35
Permanent Ineff=
       F       F
Bank Sta=4944,5056
Exp/Cntr=0.5,0.3

Type RM Length L Ch R = 1 ,382682  ,1265,1265,1265
BEGIN DESCRIPTION:
Dan River 90.0
END DESCRIPTION:
XS GIS Cut Line= 5
      1665868.58       966608.88      1665793.14       966480.82
      1665727.04       966348.62      1665644.79       966131.07
      1665662.94       966028.25
#Sta/Elev= 30
  4714.7  697.09  4751.5  685.61  4764.8  682.51  4779.5  676.41  4786.9  675.04
    4790  673.63  4793.2  670.62  4826.5     658    4838  657.17  4902.2  657.53
  4919.1  646.49  4927.3  646.33  4931.3  638.33  5068.7  638.33  5072.7  646.33
  5103.2  646.33  5103.4  650.14  5109.5  651.29  5114.5  654.24  5121.2  660.02
  5125.4  660.93  5145.6     660  5225.2  660.16    5239  659.17  5269.5  660.11
  5278.7  663.65  5308.1  667.21  5337.1     675    5343  677.65  5348.1  677.83
#Mann= 3 ,-1 , 0
  4714.7     .09       0  4927.3     .04       0  5072.7     .09       0
Bank Sta=4927.3,5072.7
Exp/Cntr=0.3,0.1

Type RM Length L Ch R = 1 ,381417  ,1169,1169,1169
BEGIN DESCRIPTION:
Dan River 89.0
END DESCRIPTION:
XS GIS Cut Line= 3
      1667065.51        966128.3      1666854.66       965786.96
      1666724.01        965516.9
#Sta/Elev= 30
  4596.3  716.34  4620.9  710.49  4636.8  708.31  4656.3  698.64  4673.5   691.5
  4704.7  680.85  4722.5  671.71  4760.6  658.22  4789.6  654.31  4800.9  653.74
  4820.2  655.19  4865.6  657.11  4884.9   656.9  4912.9  659.06  4923.8  657.97
    4931  653.88  4948.9  641.86  4951.7  633.86  5048.3  633.86  5051.1  641.86
  5055.4  642.34  5057.9  641.86  5070.4  646.69  5092.6  659.79  5105.1  661.36
  5116.8  664.62  5162.4   681.2  5185.5  688.51  5249.9  704.84  5297.5  715.99
#Mann= 3 ,-1 , 0
  4596.3     .09       0  4948.9     .04       0  5051.1     .09       0
Bank Sta=4948.9,5051.1
Exp/Cntr=0.3,0.1

Type RM Length L Ch R = 1 ,380248  ,1333,1333,1333
BEGIN DESCRIPTION:
Dan River 88.0
END DESCRIPTION:
XS GIS Cut Line= 3
      1668132.43        965683.5      1667956.03       965400.77
      1667751.39       964981.91
#Sta/Elev= 30
  4660.8  672.09  4697.4  669.89  4730.5  663.03  4746.2  661.63  4796.2  654.53
  4823.3  653.99  4869.5  657.35  4901.1  657.78    4937  642.62  4937.3  641.99
  4941.6  641.99  4944.8  633.99  5055.2  633.99  5058.4  641.99  5063.4  641.99
  5078.5  650.83  5088.9  653.75  5103.2     659  5116.5  660.58  5143.6  658.26
  5188.6   661.1    5207  661.56  5231.2   667.8    5265  671.15  5290.1  678.46
  5301.5  676.96  5315.6  678.56  5336.1  678.72  5388.3  691.29  5460.2  712.35
#Mann= 3 ,-1 , 0
  4660.8     .09       0  4941.6     .04       0  5058.4     .09       0
Bank Sta=4941.6,5058.4
Exp/Cntr=0.3,0.1

Type RM Length L Ch R = 1 ,378915  ,1371,1371,1371
BEGIN DESCRIPTION:
Dan River 87.0
END DESCRIPTION:
XS GIS Cut Line= 4
      1669252.23        965450.8      1669279.78       965230.47
      1669193.27       965064.64        1668580.       964516.19
#Sta/Elev= 30
  4581.6  750.82  4717.4     731  4808.6  712.06  4840.1  703.64    4864  694.41
  4881.9  685.65  4923.1  660.74  4931.3  659.03  4944.4     640  4948.9  639.52
  4951.7  631.52  5048.3  631.52  5051.1  639.52  5061.1  639.52  5064.2  646.22
  5076.6  653.87  5079.6  657.11  5086.9  659.37  5149.7   654.4    5200  654.67
  5311.6  653.21  5392.2  656.61    5500  657.68  5532.9  654.31  5557.6  647.72
  5597.9  654.42  5629.7  654.07  5680.2  660.93  5724.7  676.28  5813.5  715.91
#Mann= 5 ,-1 , 0
  4581.6     .09       0  4948.9     .04       0  5051.1     .09       0
    5200    .035       0    5500     .09       0
#XS Ineff= 2 , 0
       0                  5509.3       0     751
Permanent Ineff=
       F       F
Bank Sta=4948.9,5051.1
Exp/Cntr=0.3,0.1

Type RM Length L Ch R = 1 ,377544  ,1241,1241,1241
BEGIN DESCRIPTION:
Dan River 86.0
END DESCRIPTION:
XS GIS Cut Line= 3
      1670424.71        964316.6      1670161.07       964101.31
      1669610.26       963638.63
#Sta/Elev= 30
    4654  697.11  4702.2  678.89  4751.2  664.78  4775.5  660.07  4809.1  657.07
  4844.6  656.12  4879.8  657.92  4896.8  654.82  4907.1  647.23  4924.8  637.64
  4941.5   637.4  4944.7   629.4  5055.3   629.4  5058.5   637.4  5061.2   637.4
  5061.5  639.92  5066.2  645.91  5086.2  655.58  5104.2  656.26  5131.1   652.8
    5200  651.44  5244.5  652.74    5335  650.44  5407.5  653.15  5451.6  659.15
    5550  679.09  5607.9  687.73  5663.9  692.77  5693.2  701.47  5713.7  704.98
#Mann= 5 ,-1 , 0
    4654     .09       0  4941.5     .04       0  5058.5     .09       0
    5200    .035       0    5550     .09       0
Bank Sta=4941.5,5058.5
Exp/Cntr=0.3,0.1

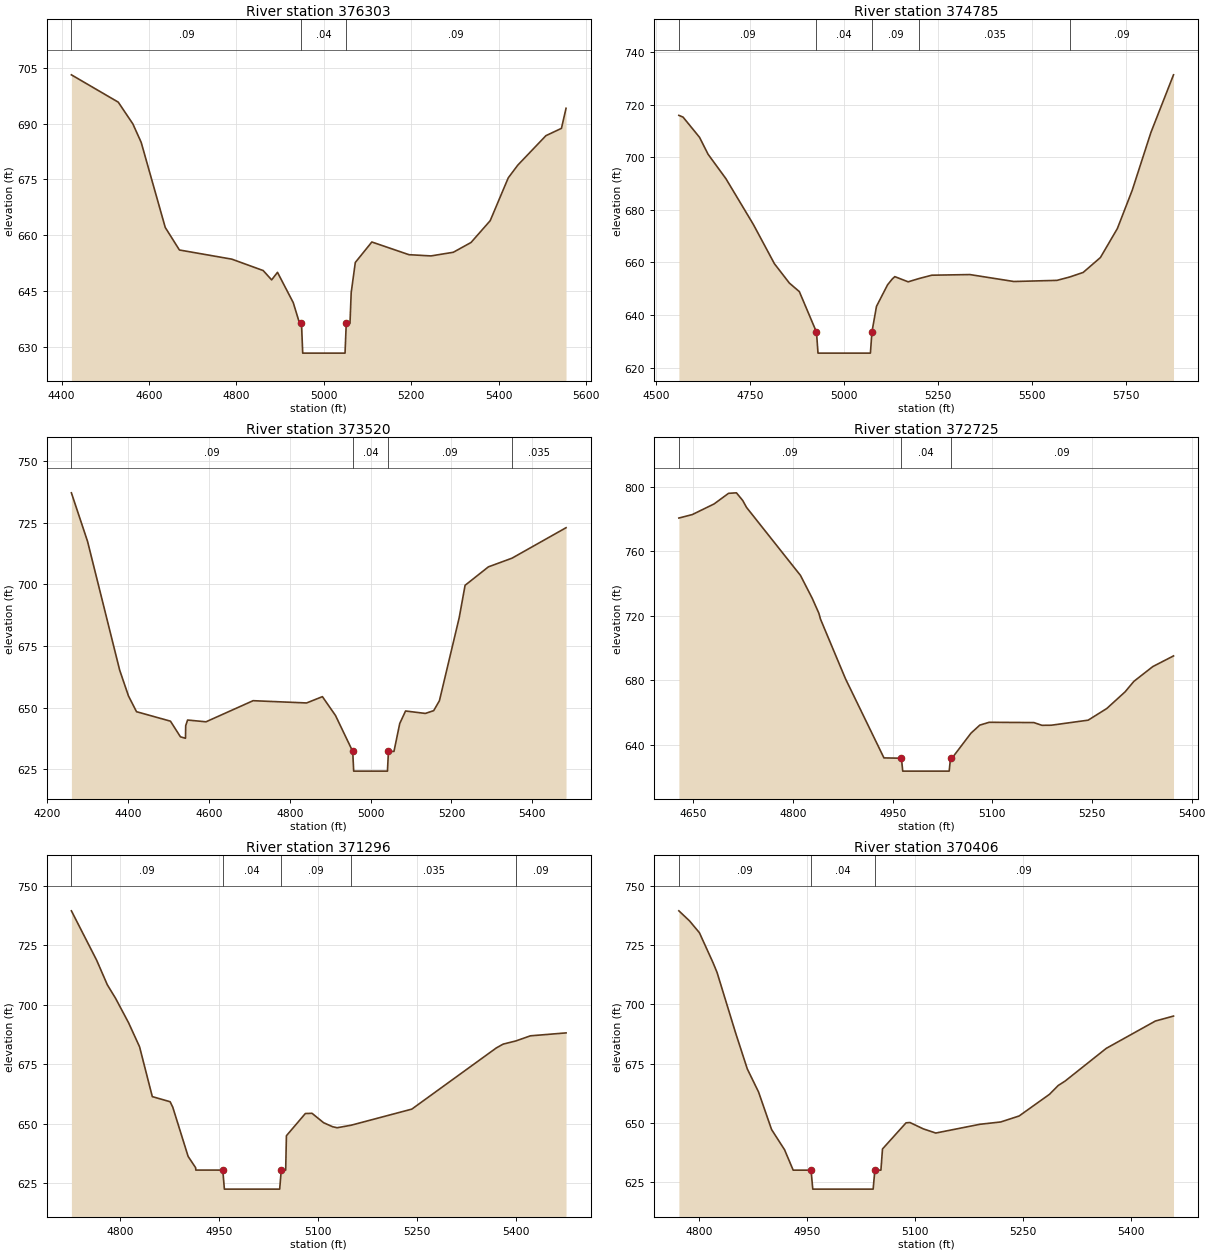
Type RM Length L Ch R = 1 ,376303  ,1518,1518,1518
BEGIN DESCRIPTION:
Dan River 85.0
END DESCRIPTION:
XS GIS Cut Line= 5
       1671477.1       963748.07       1671334.3       963627.61
      1671097.45       963335.68      1670954.24       963098.83
      1670715.02       962931.56
#Sta/Elev= 30
  4422.5  703.09  4529.7  695.75  4563.1  689.91  4582.1  684.96  4637.2  662.09
  4669.6  656.04  4789.5  653.58  4861.2  650.52  4880.5  648.01  4893.9  650.04
    4930  641.89  4944.4  636.34  4948.8  636.34  4951.6  628.34  5048.4  628.34
  5051.2  636.34  5059.7  636.34  5062.5  644.59  5071.9  652.69  5109.7  658.19
  5194.6  654.78    5245  654.45  5296.1  655.43  5336.6  658.06  5380.4  663.91
  5421.7  675.41  5443.5  678.83  5507.9  686.75  5543.4  688.71  5553.9   694.1
#Mann= 3 ,-1 , 0
  4422.5     .09       0  4948.8     .04       0  5051.2     .09       0
Bank Sta=4948.8,5051.2
Exp/Cntr=0.3,0.1

Type RM Length L Ch R = 1 ,374785  ,1265,1265,1265
BEGIN DESCRIPTION:
Dan River 84.0
END DESCRIPTION:
XS GIS Cut Line= 4
      1672364.32       962564.55      1672248.65       962294.65
      1672121.96       962239.57      1671273.71        961991.7
#Sta/Elev= 30
  4560.3  716.04  4571.5  715.37  4615.4  707.65  4637.9  701.24  4685.3  691.95
  4758.7  674.42  4814.4  659.54  4854.2  652.16  4880.7  648.91  4926.3  633.48
  4930.3  625.48  5069.7  625.48  5073.7  633.48  5085.9  643.31  5115.3  651.49
  5127.2  653.61  5134.5  654.62  5170.1  652.64    5200  653.93  5232.9  655.16
  5334.3   655.4  5451.3  652.76  5565.8  653.19    5600  654.49  5635.6  656.22
  5681.4  661.89  5726.5  672.94    5766  687.52  5815.6  709.49  5875.8  731.48
#Mann= 5 ,-1 , 0
  4560.3     .09       0  4926.3     .04       0  5073.7     .09       0
    5200    .035       0    5600     .09       0
Bank Sta=4926.3,5073.7
Exp/Cntr=0.3,0.1

Type RM Length L Ch R = 1 ,373520  ,795,795,795
BEGIN DESCRIPTION:
Dan River 82.0
END DESCRIPTION:
XS GIS Cut Line= 4
      1673140.96       961022.28      1672590.15       961071.85
       1672404.4        961009.6       1671945.7       960884.57
#Sta/Elev= 30
  4259.5  737.16  4299.5  717.45    4379  665.21  4400.8  654.74  4420.7  648.35
  4504.7  644.51  4529.4  638.16  4541.9  637.57  4542.4  642.66  4547.1  644.97
  4592.6  644.25  4709.3  652.82  4841.7   651.9  4880.8  654.46  4913.3  646.78
  4955.8  632.24  4958.2  624.24  5041.8  624.24  5044.2  632.24  5057.9  632.24
  5072.2  643.57  5086.6  648.64  5135.5  647.65  5156.2  648.78  5170.4   652.8
  5219.4  686.53  5233.9  699.63  5291.6  707.12    5350  710.64  5483.8     723
#Mann= 4 ,-1 , 0
  4259.5     .09       0  4955.8     .04       0  5044.2     .09       0
    5350    .035       0
Bank Sta=4955.8,5044.2
Exp/Cntr=0.3,0.1

Type RM Length L Ch R = 1 ,372725  ,1429,1429,1429
BEGIN DESCRIPTION:
Dan River 81.0
END DESCRIPTION:
XS GIS Cut Line= 3
      1673013.35       960119.13      1672645.23       960339.27
      1672348.04       960445.73
#Sta/Elev= 30
  4628.1  780.58  4648.4  782.74  4681.1  789.32  4702.9   795.9  4714.8  796.21
  4724.3  791.41  4729.9   787.2  4811.2  744.99  4828.9  730.78  4838.8  721.61
  4841.3  717.91  4878.9  680.97  4936.8   631.9  4963.1   631.7  4965.1   623.7
    5035   623.7    5037   631.7  5039.8  632.04  5067.7  647.18  5081.1  652.22
  5095.2  653.97  5162.5   653.8  5174.6   652.1  5188.6  652.15  5244.2  655.29
  5272.3  662.53  5299.8  672.84  5313.1  679.37  5341.5   688.5  5372.7  695.12
#Mann= 3 ,-1 , 0
  4628.1     .09       0  4963.1     .04       0    5037     .09       0
Bank Sta=4963.1,5037
Exp/Cntr=0.3,0.1

Type RM Length L Ch R = 1 ,371296  ,890,890,890
BEGIN DESCRIPTION:
Dan River 80.0
END DESCRIPTION:
XS GIS Cut Line= 3
       1671334.3        959683.8       1671353.1       959979.75
      1671422.43        960427.4
#Sta/Elev= 30
  4726.3  739.43  4764.6  718.64  4780.7  708.35  4793.3  702.61  4812.9  692.39
  4829.6  682.25  4848.9  661.31  4875.9  659.16  4879.9  656.86  4903.2  636.15
  4914.6  631.39  4914.8  630.42  4955.7  630.41  4958.1  622.41  5041.9  622.41
  5044.3  630.41    5051  630.42  5052.1  644.86  5080.8   654.2  5090.9  654.29
  5108.4  650.34    5122  648.66  5128.9  648.22    5150  649.27  5242.1  656.05
  5370.2  681.79  5380.5  683.38    5400  684.74  5421.8  686.87  5475.8   688.1
#Mann= 5 ,-1 , 0
  4726.3     .09       0  4955.7     .04       0  5044.3     .09       0
    5150    .035       0    5400     .09       0
Bank Sta=4955.7,5044.3
Exp/Cntr=0.3,0.1

Type RM Length L Ch R = 1 ,370406  ,1287,1287,1287
BEGIN DESCRIPTION:
Dan River 79.0
END DESCRIPTION:
XS GIS Cut Line= 3
      1670430.97       959865.57      1670480.59       960108.49
      1670541.13       960543.07
#Sta/Elev= 30
  4772.2  739.47  4787.1  735.19  4800.7  730.24  4819.6  717.62  4825.3  713.41
  4850.7  688.22  4867.2  672.79  4882.8  663.07  4900.9  647.22  4918.9  638.71
  4930.9  630.08  4955.7  630.08  4958.1  622.08  5041.9  622.08  5044.3  630.08
  5052.7  630.08  5054.9  639.03  5087.6  650.05    5093  650.17  5111.7  647.48
  5128.9  645.74  5190.1  649.43    5219  650.41  5244.5  652.92  5286.7  662.07
  5298.9  665.81  5308.4  667.66  5365.6  681.47  5433.7  692.98  5458.9  695.08
#Mann= 3 ,-1 , 0
  4772.2     .09       0  4955.7     .04       0  5044.3     .09       0
Bank Sta=4955.7,5044.3
Exp/Cntr=0.3,0.1

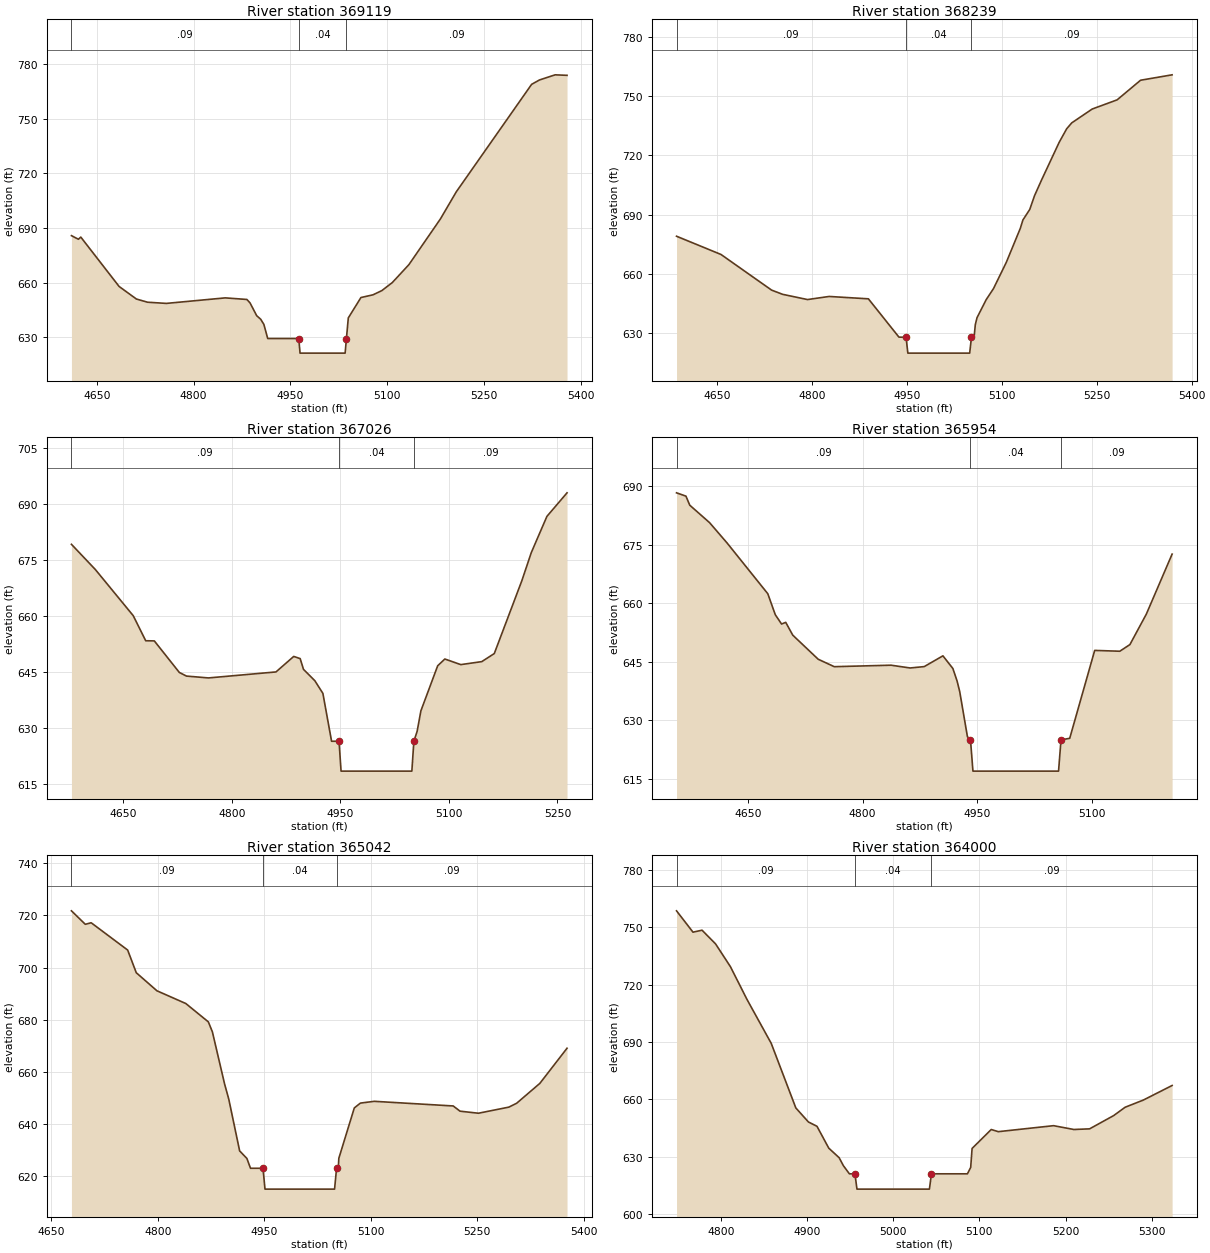
Type RM Length L Ch R = 1 ,369119  ,880,880,880
BEGIN DESCRIPTION:
Dan River 78.0
END DESCRIPTION:
XS GIS Cut Line= 3
      1669553.76       959998.17      1669251.35       960258.24
      1668967.08       960494.12
#Sta/Elev= 30
  4610.7   685.8  4621.5  683.82  4625.2  685.01  4684.6  657.93  4711.4  651.04
  4728.7  649.29  4757.7  648.64  4849.2  651.67  4882.7   650.8  4887.6   648.9
  4897.9  641.89  4904.1  639.95    4909  637.14    4915  629.37  4963.1  629.37
  4965.1  621.37    5035  621.37    5037  629.37  5039.9  640.67  5059.5  651.86
  5078.2  653.35  5091.9  655.66  5108.1  660.06  5133.8  669.87  5182.7  694.96
  5207.3  709.83  5324.1  768.78  5336.3  771.19  5360.6     774    5379  773.72
#Mann= 3 ,-1 , 0
  4610.7     .09       0  4963.1     .04       0    5037     .09       0
Bank Sta=4963.1,5037
Exp/Cntr=0.3,0.1

Type RM Length L Ch R = 1 ,368239  ,1213,1213,1213
BEGIN DESCRIPTION:
Dan River 77.0
END DESCRIPTION:
XS GIS Cut Line= 4
       1669759.4       959605.03      1669541.67       959520.36
      1669390.46       959441.73      1669015.47       959381.25
#Sta/Elev= 30
  4585.2  679.12  4655.5   669.9  4735.6  651.85    4753  649.72  4792.4  647.07
  4826.6  648.64  4888.7  647.44    4937  628.06  4948.3  627.96  4951.1  619.96
  5048.9  619.96  5051.7  627.96  5055.9  627.98  5057.8  634.36  5060.5  637.89
    5075  647.01  5086.6  652.64  5106.9  665.95    5129  683.12  5133.1  687.35
  5143.9  692.67  5151.5  699.65  5162.7  707.66  5190.5  726.67  5202.3  733.49
  5210.3  736.48  5242.7   743.5  5282.1  748.14  5319.2  758.07  5369.1  760.81
#Mann= 3 ,-1 , 0
  4585.2     .09       0  4948.3     .04       0  5051.7     .09       0
Bank Sta=4948.3,5051.7
Exp/Cntr=0.3,0.1

Type RM Length L Ch R = 1 ,367026  ,1072,1072,1072
BEGIN DESCRIPTION:
Dan River 76.0
END DESCRIPTION:
XS GIS Cut Line= 3
      1670424.71       958661.51      1670061.81       958437.72
      1669844.08       958298.61
#Sta/Elev= 30
  4578.6  679.18  4611.6  672.43    4664  660.06  4681.2  653.35  4693.1  653.31
  4727.7  644.85  4737.5  643.89  4767.9  643.39  4861.2     645  4885.7  649.15
  4894.6  648.57  4899.2  645.69  4914.9  642.64    4926  639.25    4938  626.43
  4948.3  626.43  4951.1  618.43  5048.9  618.43  5051.7  626.43  5056.2  629.09
  5061.4  634.58  5084.6  646.65  5094.5  648.46  5116.5  646.96  5145.5  647.76
  5162.8  649.92  5200.9  669.45  5213.9  676.95  5235.5  686.66  5263.3  692.97
#Mann= 3 ,-1 , 0
  4578.6     .09       0  4948.3     .04       0  5051.7     .09       0
Bank Sta=4948.3,5051.7
Exp/Cntr=0.3,0.1

Type RM Length L Ch R = 1 ,365954  ,912,912,912
BEGIN DESCRIPTION:
Dan River 75.0
END DESCRIPTION:
XS GIS Cut Line= 4
      1671192.83       957802.66      1670999.29       957760.32
      1670793.65       957651.45      1670600.11       957554.68
#Sta/Elev= 30
    4557  688.27  4569.3  687.42  4574.3   685.1  4600.2  680.62    4623  675.42
  4676.2  662.41    4686  657.02  4694.2  654.64  4699.6  655.08  4708.8  651.79
    4742  645.62    4763  643.71  4837.1  644.09  4862.1  643.38  4880.5  643.73
  4904.9  646.49  4917.9  643.24  4923.4  640.03  4926.8  637.36  4936.9  625.77
  4940.9  624.94  4944.1  616.94  5055.9  616.94  5059.1  624.94  5070.5  625.36
  5103.1  647.88  5135.9  647.67  5149.1  649.38  5170.5  657.17  5204.2  672.56
#Mann= 3 ,-1 , 0
    4557     .09       0  4940.9     .04       0  5059.1     .09       0
Bank Sta=4940.9,5059.1
Exp/Cntr=0.3,0.1

Type RM Length L Ch R = 1 ,365042  ,1042,1042,1042
BEGIN DESCRIPTION:
Dan River 74.0
END DESCRIPTION:
XS GIS Cut Line= 4
      1671011.39       956659.54      1670751.31       956847.04
      1670575.91        956992.2      1670467.05       957095.02
#Sta/Elev= 30
  4678.4  721.79  4697.9  716.62  4706.2  717.21  4757.6  706.74  4769.7  698.05
  4798.8  691.12  4839.5  686.23  4871.2   679.2  4876.9  675.38    4894  655.48
    4900  649.54  4915.3   629.7  4925.5  626.81  4930.6  623.04  4948.2  623.04
    4951  615.04    5049  615.04  5051.8  623.04  5054.2  623.04    5055  626.87
  5076.8  646.19  5085.4  648.04  5104.9  648.72  5216.1  646.94  5225.7  644.94
  5251.6  644.15  5294.4  646.49  5305.4  647.97  5338.1   655.6  5376.4  669.08
#Mann= 3 ,-1 , 0
  4678.4     .09       0  4948.2     .04       0  5051.8     .09       0
Bank Sta=4948.2,5051.8
Exp/Cntr=0.3,0.1

Type RM Length L Ch R = 1 ,364000  ,1204,1204,1204
BEGIN DESCRIPTION:
Dan River 73.0
END DESCRIPTION:
XS GIS Cut Line= 4
      1669680.78       956526.48        1669770.        956764.5
      1669822.17       956936.37      1669880.37       957064.77
#Sta/Elev= 30
  4748.7  758.51  4767.8  747.36  4778.3  748.39    4794  741.22  4811.2  729.34
  4830.4  712.23  4858.5  689.29  4887.1  655.48  4901.7  648.16  4911.6  645.91
  4925.3  634.47  4937.3   629.5  4942.2  625.34  4949.2  621.07  4955.6  621.07
    4958  613.07    5042  613.07  5044.4  621.07  5086.1  621.07  5089.9  624.43
  5091.5  634.33  5113.7  644.22  5121.9   643.1    5186  646.23  5209.6  644.23
  5227.8  644.57  5255.7   651.5    5269  655.86  5290.1  659.61  5323.5  667.23
#Mann= 3 ,-1 , 0
  4748.7     .09       0  4955.6     .04       0  5044.4     .09       0
Bank Sta=4955.6,5044.4
Exp/Cntr=0.3,0.1

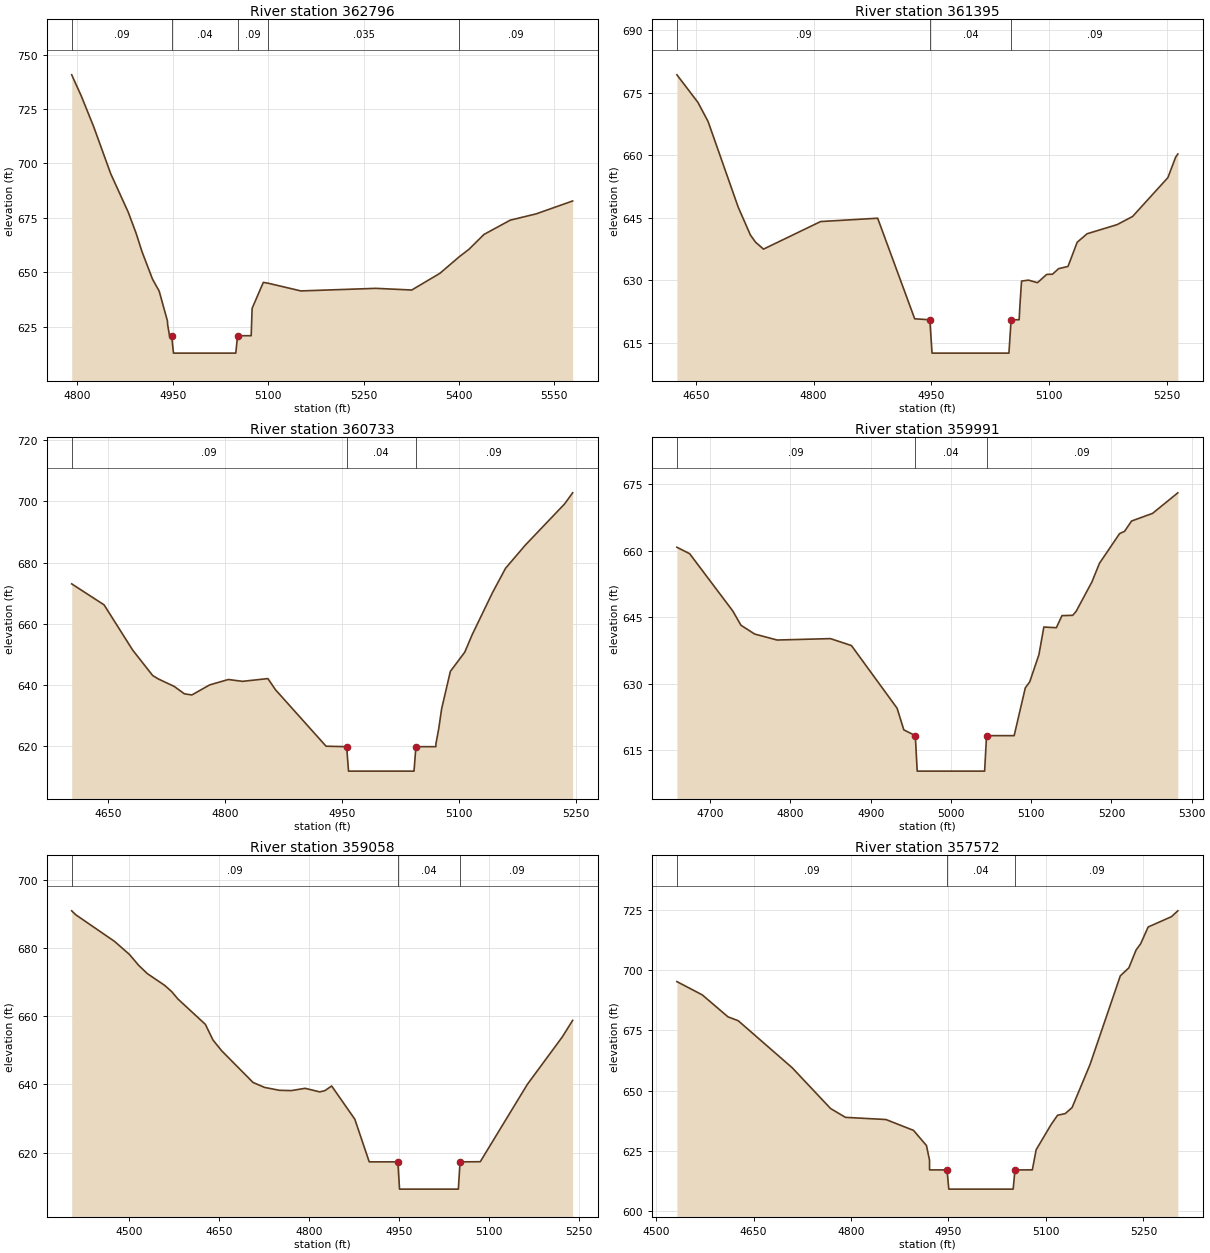
Type RM Length L Ch R = 1 ,362796  ,1401,1401,1401
BEGIN DESCRIPTION:
Dan River 72.0
END DESCRIPTION:
XS GIS Cut Line= 3
      1668530.67       957094.99      1668678.35       957254.94
       1669026.4       957706.39
#Sta/Elev= 30
    4791  740.74    4806  731.05  4825.5  716.94  4852.4  695.23    4880  677.53
  4892.3  667.89  4901.6  659.41  4918.1   646.8  4928.5  641.35  4941.5  627.65
  4941.9  625.81  4944.8  620.82  4948.2  620.81    4951  612.81    5049  612.81
  5051.8  620.81  5073.2  620.81  5074.7  633.39  5092.3  645.33    5100  644.94
  5151.3   641.4  5269.1  642.59  5325.7  641.82    5370   649.5    5400  657.01
  5415.7  660.55  5439.3  667.37  5480.6  673.93  5521.4  676.83  5578.7  682.75
#Mann= 5 ,-1 , 0
    4791     .09       0  4948.2     .04       0  5051.8     .09       0
    5100    .035       0    5400     .09       0
Bank Sta=4948.2,5051.8
Exp/Cntr=0.3,0.1

Type RM Length L Ch R = 1 ,361395  ,662,662,662
BEGIN DESCRIPTION:
Dan River 70.0
END DESCRIPTION:
XS GIS Cut Line= 3
      1667521.56       957778.47      1667612.74       958163.21
      1667684.86       958395.38
#Sta/Elev= 30
  4625.8  679.25  4652.6  672.64  4665.5  668.08  4703.9  647.54  4719.5  640.83
  4726.1  639.11  4736.2  637.46    4809  644.07  4881.7  644.87  4928.9  620.75
  4948.2  620.52    4951  612.52    5049  612.52  5051.8  620.52    5062  620.52
  5063.2  624.55  5065.1   629.8    5074  630.02  5085.4  629.41  5097.2   631.4
  5104.5  631.44  5112.3  632.77  5124.3  633.31    5136   639.1  5148.6  641.14
  5186.9  643.33  5206.6  645.28  5251.6   654.6  5261.5   659.5  5264.3  660.26
#Mann= 3 ,-1 , 0
  4625.8     .09       0  4948.2     .04       0  5051.8     .09       0
Bank Sta=4948.2,5051.8
Exp/Cntr=0.3,0.1

Type RM Length L Ch R = 1 ,360733  ,742,742,742
BEGIN DESCRIPTION:
Dan River 69.0
END DESCRIPTION:
XS GIS Cut Line= 3
      1667188.91       957790.56      1666971.88       958125.01
      1666813.92       958310.71
#Sta/Elev= 30
    4603  673.03  4644.5  666.17  4681.2  651.37  4706.8  643.06    4714  641.94
  4734.5  639.48  4747.6  637.06  4757.1   636.7    4780  639.99  4803.9  641.75
    4822  641.15  4854.6  642.05  4864.3  638.41  4929.2  619.93  4955.6  619.78
    4958  611.78    5042  611.78  5044.4  619.78    5070  619.78  5070.1  620.73
  5073.7  625.69  5077.4  632.17  5088.6  644.41  5107.1  650.71  5116.5  656.37
  5142.5   670.1  5159.4  678.14  5184.5  685.65    5235  699.16  5245.4  702.81
#Mann= 3 ,-1 , 0
    4603     .09       0  4955.6     .04       0  5044.4     .09       0
Bank Sta=4955.6,5044.4
Exp/Cntr=0.3,0.1

Type RM Length L Ch R = 1 ,359991  ,933,933,933
BEGIN DESCRIPTION:
Dan River 68.0
END DESCRIPTION:
XS GIS Cut Line= 3
      1666983.27       957421.62      1666632.95        957483.8
      1666372.39       957548.63
#Sta/Elev= 30
  4658.5  660.76  4674.4  659.31  4728.2  646.38  4738.3  643.19  4755.4   641.2
  4783.4  639.85  4849.8  640.17    4876  638.61  4932.9  624.48  4941.3   619.6
  4955.6   618.3    4958   610.3    5042   610.3  5044.4   618.3  5078.8   618.3
  5092.7  629.07  5098.2  630.42  5109.7  636.56  5115.8  642.78  5131.4  642.63
  5138.4  645.35  5151.8  645.42    5156   646.3  5175.7  652.94  5185.1  657.14
  5210.2  663.84  5216.4  664.35  5225.1  666.67  5251.3   668.4  5282.8  673.03
#Mann= 3 ,-1 , 0
  4658.5     .09       0  4955.6     .04       0  5044.4     .09       0
Bank Sta=4955.6,5044.4
Exp/Cntr=0.3,0.1

Type RM Length L Ch R = 1 ,359058  ,1486,1486,1486
BEGIN DESCRIPTION:
Dan River 67.0
END DESCRIPTION:
XS GIS Cut Line= 3
      1667440.07       956918.73      1666911.87        956654.2
       1666718.5       956505.62
#Sta/Elev= 30
  4404.8  690.89  4411.3  689.77  4476.1  681.93  4500.8  678.13  4516.4   674.9
  4530.8  672.47  4559.6  669.04  4571.4  667.19  4581.7  665.04  4627.5  657.59
  4640.2     653  4654.5  649.87    4707  640.54    4726   639.1  4750.8  638.25
  4770.7  638.16  4793.7  638.83  4818.1  637.78  4826.8  638.17  4837.9  639.51
  4876.5  629.77  4900.5  617.26  4948.2  617.26    4951  609.26    5049  609.26
  5051.8  617.26  5085.5   617.3  5163.9  639.98    5222  653.86  5239.4  658.76
#Mann= 3 ,-1 , 0
  4404.8     .09       0  4948.2     .04       0  5051.8     .09       0
Bank Sta=4948.2,5051.8
Exp/Cntr=0.3,0.1

Type RM Length L Ch R = 1 ,357572  ,854,854,854
BEGIN DESCRIPTION:
Dan River 65.0
END DESCRIPTION:
XS GIS Cut Line= 3
      1668205.69        955949.3      1667930.29       955585.77
      1667759.54       955321.38
#Sta/Elev= 30
  4532.1  695.32  4571.1   689.8  4610.7  680.66  4626.5  679.03  4709.6  659.45
  4768.5  642.52  4791.4  638.84  4853.8  637.93  4896.2  633.41  4916.1  627.11
  4920.8  621.07  4920.9  616.97  4947.7  616.97  4950.5  608.97  5049.5  608.97
  5052.3  616.97    5079  616.98  5084.9  625.37    5108  635.88  5117.8   639.7
  5129.7  640.42  5140.2  642.92  5167.8  660.83  5214.4  697.74  5227.5  701.02
  5238.6  708.44  5245.8  711.13  5257.2  718.04    5293  722.33  5302.9  724.77
#Mann= 3 ,-1 , 0
  4532.1     .09       0  4947.7     .04       0  5052.3     .09       0
Bank Sta=4947.7,5052.3
Exp/Cntr=0.3,0.1

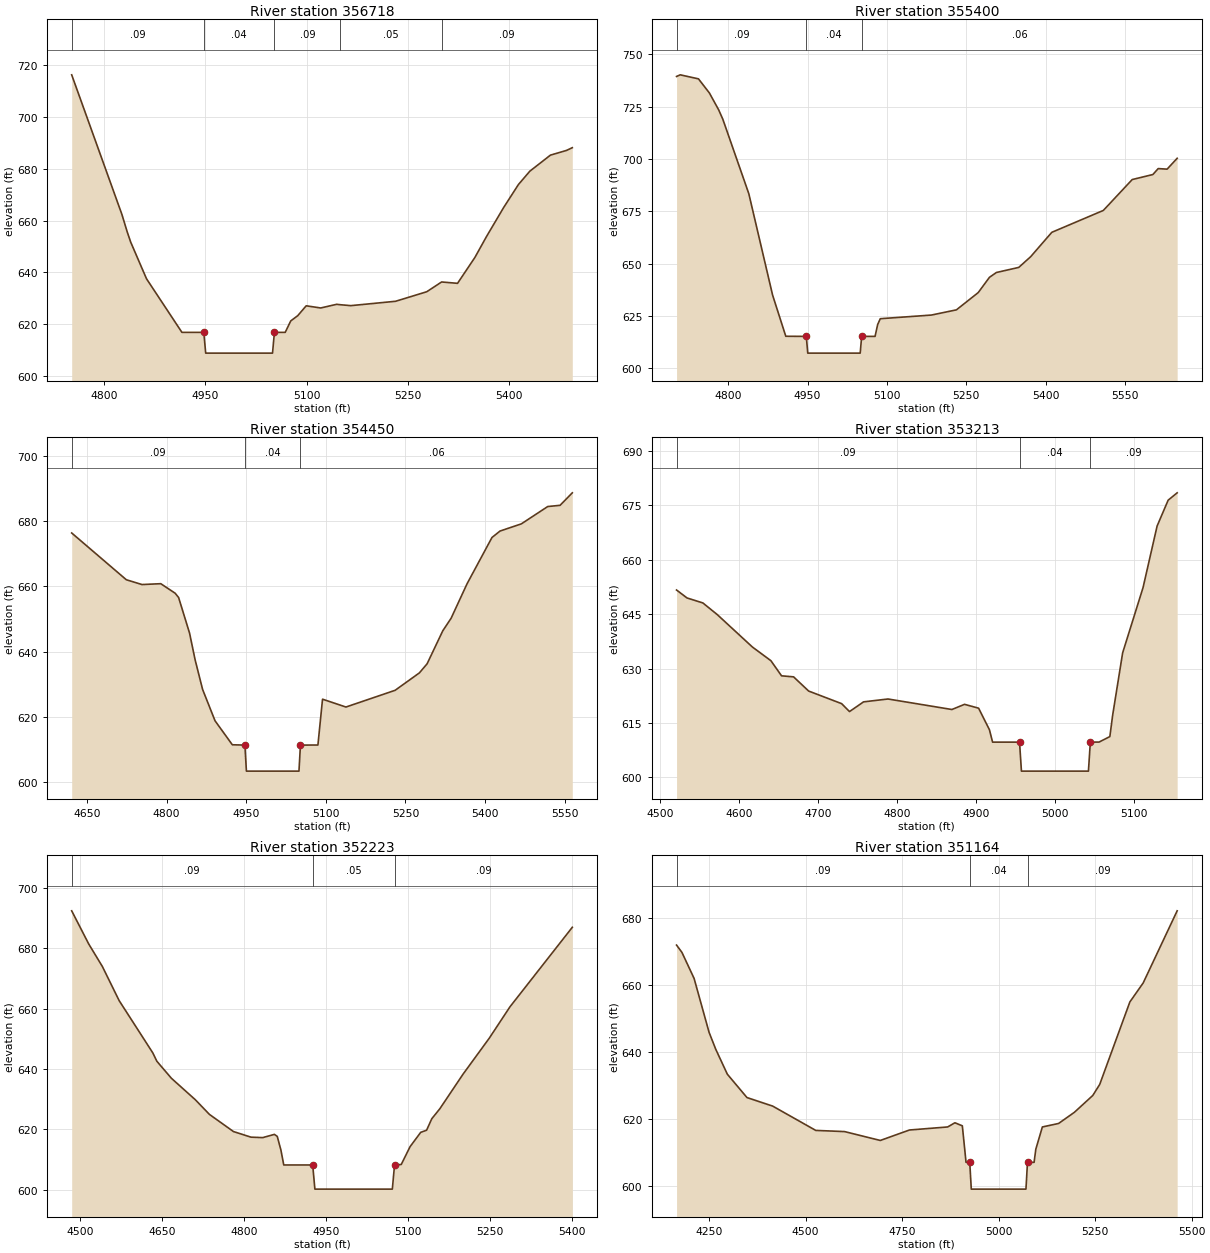
Type RM Length L Ch R = 1 ,356718  ,1318,1318,1318
BEGIN DESCRIPTION:
Dan River 64.0
END DESCRIPTION:
XS GIS Cut Line= 3
      1668811.59       955079.02      1668673.88       955056.99
      1668079.01       954963.35
#Sta/Elev= 30
    4752  716.14  4826.4  662.33  4834.1  655.73  4839.4  651.67  4862.8  637.56
  4915.3  616.89  4947.7  616.89  4950.5  608.89  5049.5  608.89  5052.3  616.89
  5068.3  616.89  5076.5   621.3  5086.9  623.33  5099.4  627.13  5120.9  626.29
  5144.6  627.71    5150  627.54  5165.5  627.19  5231.8  628.87    5278  632.55
    5300  636.31  5323.6  635.79  5349.3  645.76  5366.7  653.91  5392.1  665.09
  5413.7  673.83  5430.7  679.01  5461.2  685.19  5484.9     687  5493.6  688.06
#Mann= 5 ,-1 , 0
    4752     .09       0  4947.7     .04       0  5052.3     .09       0
    5150     .05       0    5300     .09       0
Bank Sta=4947.7,5052.3
Exp/Cntr=0.3,0.1

Type RM Length L Ch R = 1 ,355400  ,950,950,950
BEGIN DESCRIPTION:
Dan River 63.0
END DESCRIPTION:
XS GIS Cut Line= 3
      1668178.15       953812.16      1667916.69       953979.45
      1667357.44       954280.35
#Sta/Elev= 30
  4702.7  739.41  4709.6  740.19  4744.1  738.26  4764.7  731.53  4782.3  723.42
  4790.1  718.96  4839.2  683.34  4884.1  634.88    4909  615.22  4947.7  615.16
  4950.5  607.16  5049.5  607.16  5052.3  615.16  5077.6  615.16  5082.5  620.85
  5087.5  623.61  5183.8  625.35  5231.2  627.84  5272.4   636.1  5293.6  643.39
  5306.7   645.7  5348.9  648.13  5371.2  653.19  5411.4  664.91  5508.7  675.37
  5563.2  690.13  5602.2  692.53  5612.3  695.37  5629.1   695.1  5648.1  700.29
#Mann= 3 ,-1 , 0
  4702.7     .09       0  4947.7     .04       0  5052.3     .06       0
Bank Sta=4947.7,5052.3
Exp/Cntr=0.3,0.1

Type RM Length L Ch R = 1 ,354450  ,1237,1237,1237
BEGIN DESCRIPTION:
Dan River 62.0
END DESCRIPTION:
XS GIS Cut Line= 3
      1667880.71       953118.13      1667484.13       953134.66
      1666944.34       953217.28
#Sta/Elev= 30
  4621.4  676.42  4724.3  662.06  4753.8  660.59  4789.2  660.85  4816.3  657.92
  4822.8  656.61  4843.4  645.69    4854   637.4    4868  628.38  4891.4  618.76
    4924  611.39  4947.7   611.3  4950.5   603.3  5049.5   603.3  5052.3   611.3
  5085.2  611.31  5093.9  625.39    5138  622.98  5230.7  628.12  5276.4  633.47
  5290.9  636.26  5320.4  646.38  5336.1  650.24  5366.2  660.84  5413.1  675.04
  5428.2  677.01  5468.4  679.22  5518.1  684.54  5541.3  684.91  5564.4  688.75
#Mann= 3 ,-1 , 0
  4621.4     .09       0  4947.7     .04       0  5052.3     .06       0
Bank Sta=4947.7,5052.3
Exp/Cntr=0.3,0.1

Type RM Length L Ch R = 1 ,353213  ,990,990,990
BEGIN DESCRIPTION:
Dan River 60.0
END DESCRIPTION:
XS GIS Cut Line= 3
      1668255.27       952297.43      1667873.78       952019.88
      1667748.52       951917.37
#Sta/Elev= 30
  4521.1  651.68  4534.3  649.49  4554.4  648.11  4572.6   644.9  4617.1  635.95
  4640.5  632.18    4654     628  4669.2  627.72  4688.3   623.8    4730  620.33
    4740  618.14  4757.8  620.82  4788.7  621.61  4869.6  618.71  4885.6  620.14
  4903.4  619.07  4917.1  613.13  4921.1  609.71  4955.2  609.71  4957.6  601.71
  5042.4  601.71  5044.8  609.71  5055.9  609.73  5069.5  611.24  5073.1   617.2
  5085.7  634.34  5111.5  652.33  5129.3  669.32  5143.3  676.46  5154.7  678.49
#Mann= 3 ,-1 , 0
  4521.1     .09       0  4955.2     .04       0  5044.8     .09       0
Bank Sta=4955.2,5044.8
Exp/Cntr=0.3,0.1

Type RM Length L Ch R = 1 ,352223  ,1059,1059,1059
BEGIN DESCRIPTION:
Dan River 59.0
END DESCRIPTION:
XS GIS Cut Line= 4
      1668899.72       951493.24      1668459.07       951223.34
      1668312.13       951129.98      1668093.79        951078.6
#Sta/Elev= 30
  4484.6  692.41  4515.8  681.41  4540.7  673.97  4571.4  662.66  4632.9  645.36
  4640.3  642.59  4666.9  636.95  4710.7  629.83  4736.4  624.99  4780.3  619.31
  4812.4  617.45  4833.8   617.3  4855.2  618.37  4860.4   617.7  4867.1  613.17
  4872.3  608.24  4925.2  608.24  4929.2  600.24  5070.8  600.24  5074.8  608.24
  5087.1  608.41  5103.2   614.3  5122.7  619.05  5133.4  619.75  5142.9  623.55
  5157.6  626.85    5200   638.3    5248  650.23  5285.9  660.64  5399.8  686.96
#Mann= 3 ,-1 , 0
  4484.6     .09       0  4925.2     .05       0  5074.8     .09       0
Bank Sta=4925.2,5074.8
Exp/Cntr=0.3,0.1

Type RM Length L Ch R = 1 ,351164  ,1035,1035,1035
BEGIN DESCRIPTION:
Dan River 58.0
END DESCRIPTION:
XS GIS Cut Line= 3
      1669720.42       950705.58      1668989.45       950310.61
       1668618.8       950028.08
#Sta/Elev= 30
  4165.7  672.05  4179.6  669.88  4211.1  662.11    4250  645.99  4267.3  640.93
  4297.3   633.5  4348.1  626.53  4414.7  623.98  4526.3  616.72  4600.9  616.37
  4693.5  613.72  4768.9  616.84    4868  617.75  4886.8     619    4906  618.09
  4915.6  607.19  4925.2  607.19  4929.2  599.19  5070.8  599.19  5074.8  607.19
  5091.9  607.19  5096.3  611.09  5113.3  617.75  5155.3  618.79  5196.2  622.12
  5243.9  627.15  5261.9  630.46    5340  655.08  5374.5  660.75  5462.5  682.28
#Mann= 3 ,-1 , 0
  4165.7     .09       0  4925.2     .04       0  5074.8     .09       0
Bank Sta=4925.2,5074.8
Exp/Cntr=0.3,0.1