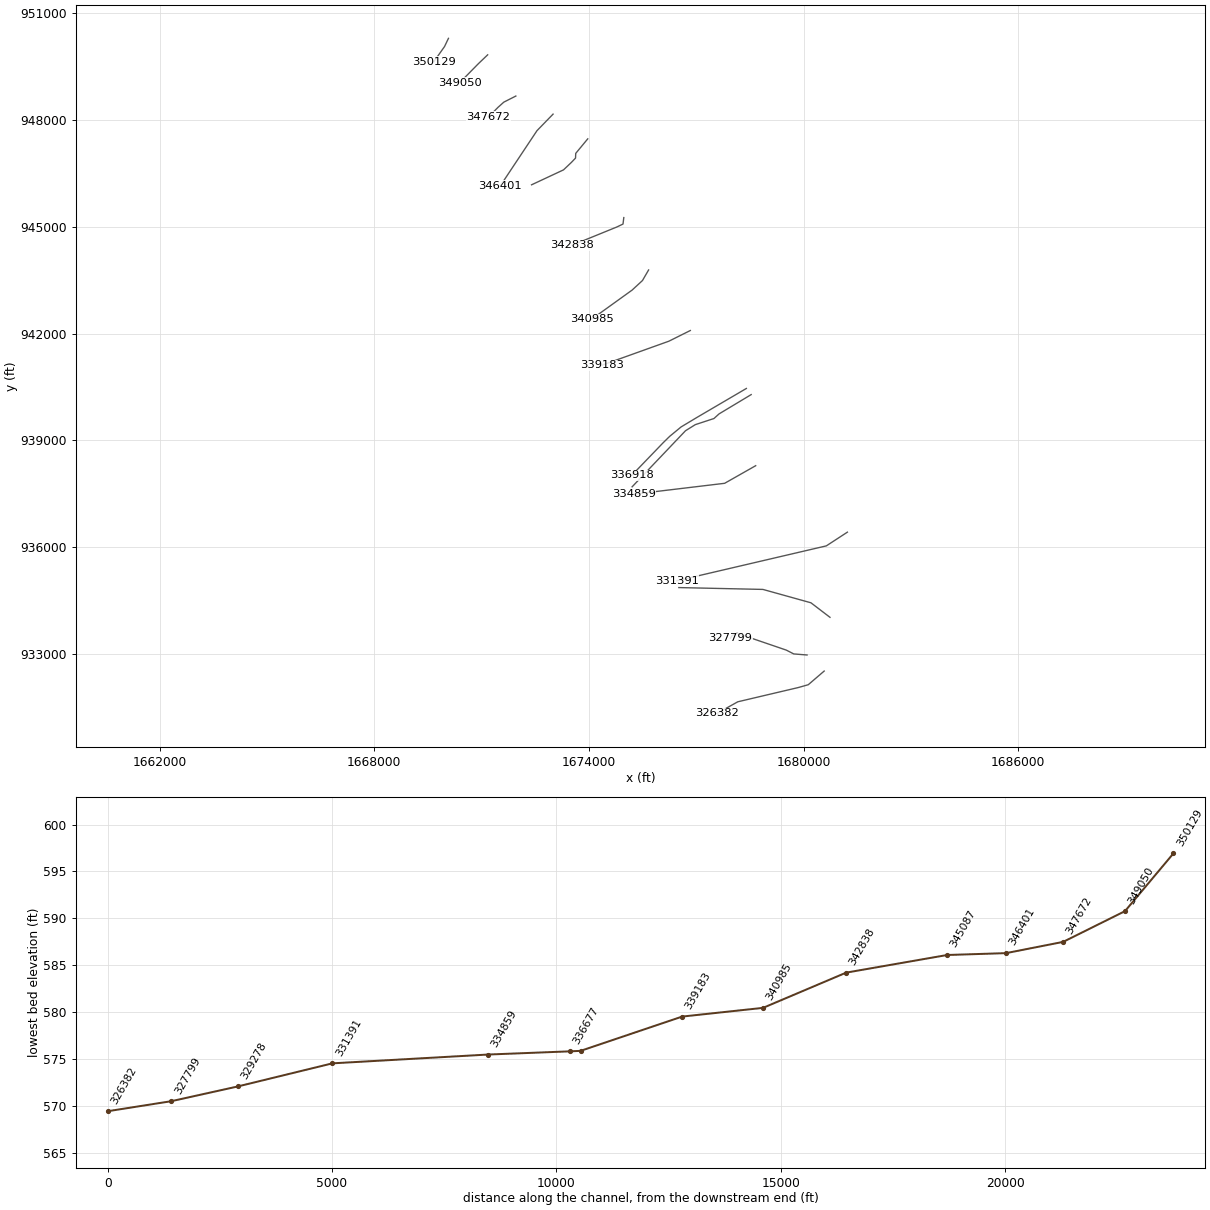
HEC-RAS study lds_dan_rvr_bctfud_lower.prj: Dan River Limited Detail Study Lower

--- lds_dan_rvr_bctfud_lower.g02 (geometry) --- (continued)

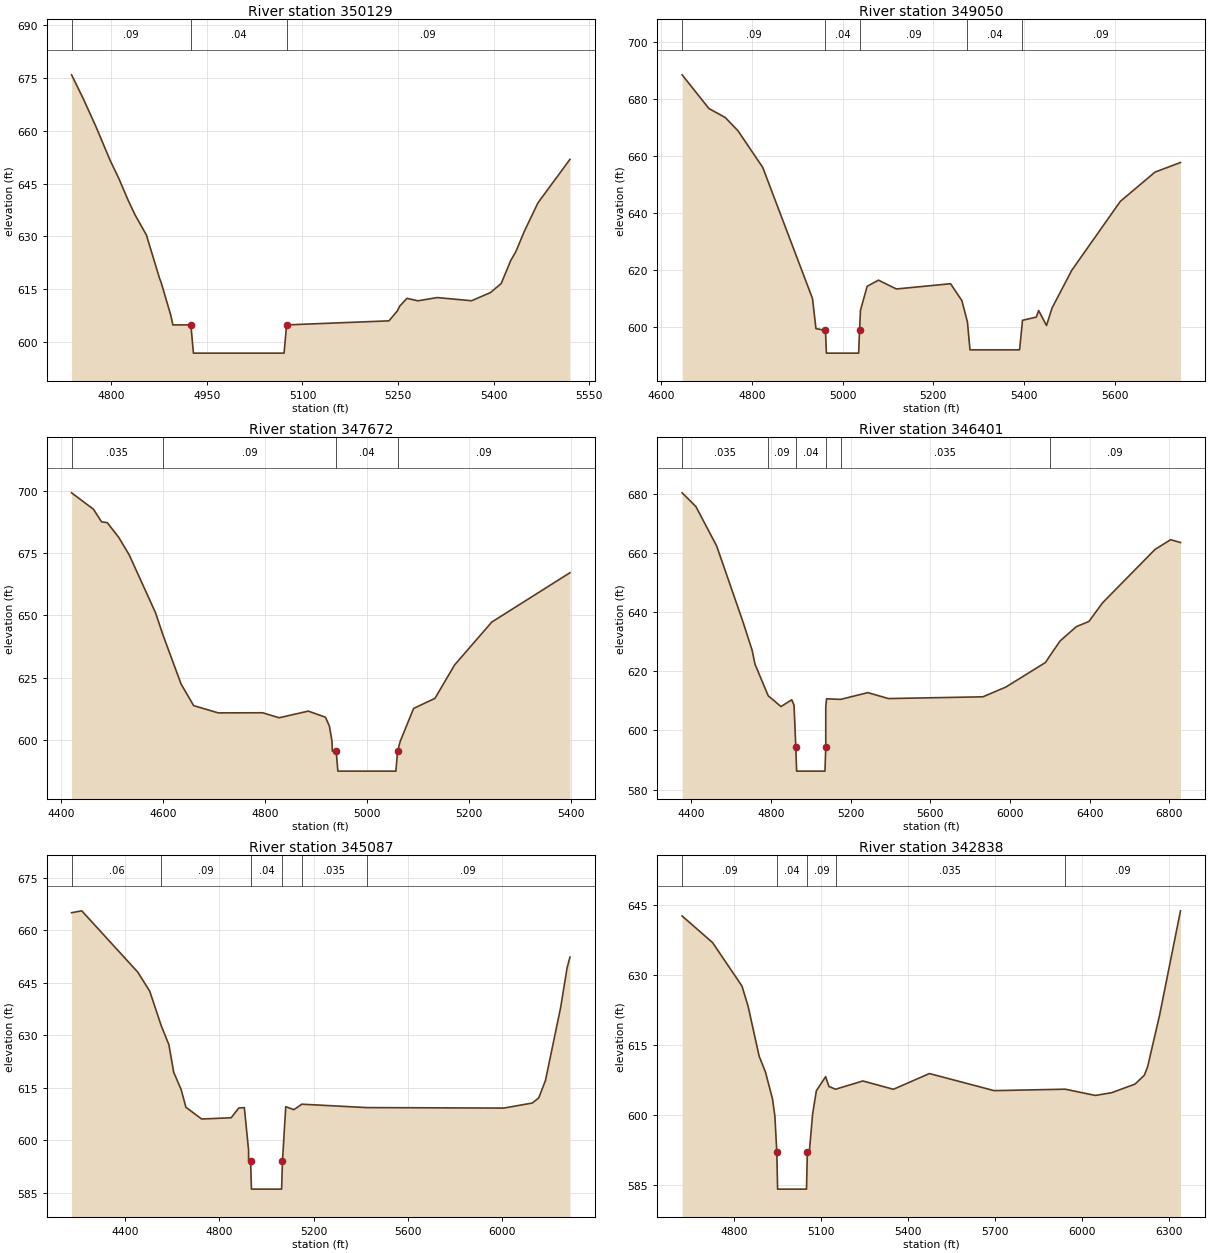
Type RM Length L Ch R = 1 ,350129  ,1079,1079,1079
BEGIN DESCRIPTION:
Dan River 57.0
END DESCRIPTION:
XS GIS Cut Line= 3
      1670072.94       950281.46      1669962.78       950050.12
      1669659.84       949620.48
#Sta/Elev= 30
  4737.7  675.81  4756.1  669.03  4775.6  661.26  4798.4  651.48  4811.6  646.53
  4825.6   640.6  4837.2  636.14  4855.1  630.41  4875.8  618.08  4878.2  616.97
  4893.3  607.69  4896.7  604.92  4924.9  604.92  4928.9  596.92  5071.1  596.92
  5075.1  604.92  5235.7  606.07  5248.9   608.9  5252.5  610.22  5263.9  612.45
  5281.2  611.75  5311.5  612.67  5365.3  611.77  5394.9  614.08  5411.8  616.65
  5426.8  623.18  5434.6  625.62  5448.4  631.57  5469.5  639.52  5519.7  651.85
#Mann= 3 ,-1 , 0
  4737.7     .09       0  4924.9     .04       0  5075.1     .09       0
Bank Sta=4924.9,5075.1
Exp/Cntr=0.3,0.1

Type RM Length L Ch R = 1 ,349050  ,1378,1378,1378
BEGIN DESCRIPTION:
Split flow
END DESCRIPTION:
XS GIS Cut Line= 3
      1671169.06       949818.78      1670910.18       949570.91
      1670392.41       949042.13
#Sta/Elev= 30
  4646.5  688.49  4705.6  676.65  4741.5  673.51  4769.3  668.91  4824.2  655.98
  4933.9  609.92  4941.5  599.36  4962.5  598.76  4964.5  590.76  5035.6  590.76
  5037.6  598.76  5039.6  605.79  5054.3  614.22  5079.3  616.38  5118.8  613.29
  5238.2  615.13  5263.2  609.18  5275.4  601.69    5281  591.92  5390.3  591.92
  5395.9  600.85  5396.6  602.28  5427.1  603.41  5432.3  605.72  5449.7  600.47
  5461.9  606.62  5505.3  619.84  5612.4  644.06  5688.8  654.33    5745  657.71
#Mann= 5 ,-1 , 0
  4646.5     .09       0  4962.5     .04       0  5037.6     .09       0
  5275.4     .04       0  5395.9     .09       0
Bank Sta=4962.5,5037.6
Exp/Cntr=0.3,0.1

Type RM Length L Ch R = 1 ,347672  ,1271,1271,1271
BEGIN DESCRIPTION:
Dan River 54.0
END DESCRIPTION:
XS GIS Cut Line= 4
      1671956.72       948662.07      1671620.72       948491.32
      1671455.48        948342.6      1671191.09        948072.7
#Sta/Elev= 30
  4421.1  699.15    4464  692.57  4479.8  687.52  4491.1  687.17  4513.8   681.2
  4534.3  674.16  4585.6  651.06    4600  642.28  4635.8  622.41  4660.4  613.77
  4708.7  610.85  4795.5   610.9    4828  608.89  4885.1  611.56  4918.9  609.11
  4926.7  605.41  4931.7  599.29  4932.3  595.49  4939.9  595.48  4943.1  587.48
  5056.9  587.48  5060.1  595.48  5061.6  595.48  5062.6  597.42  5065.5   599.5
  5091.6  612.64  5133.4  616.67  5171.9  630.06  5244.8  647.29  5398.1  667.09
#Mann= 4 ,-1 , 0
  4421.1    .035       0    4600     .09       0  4939.9     .04       0
  5060.1     .09       0
Bank Sta=4939.9,5060.1
Exp/Cntr=0.3,0.1

Type RM Length L Ch R = 1 ,346401  ,1314,1314,1314
BEGIN DESCRIPTION:
Dan River 53.0
END DESCRIPTION:
XS GIS Cut Line= 3
      1672997.75       948155.33      1672548.41       947691.29
       1671523.5       946144.56
#Sta/Elev= 30
  4354.2  680.24  4423.2  675.62  4527.8  662.25  4659.6  636.68    4706  626.99
  4719.6  622.46  4786.2  611.73  4850.5  608.08  4904.5  610.37  4915.9   608.5
  4924.9  594.28  4928.9  586.28  5071.1  586.28  5075.1  594.28  5075.2  607.97
  5079.1  610.69    5150  610.51  5286.2  612.78  5389.6  610.78  5863.9  611.37
    5979  614.66  6178.1  622.97    6200  625.21  6251.3  630.23  6332.5  635.05
  6396.1  636.82  6464.6  643.12  6727.6  661.12    6806  664.41  6855.6  663.47
#Mann= 6 ,-1 , 0
  4354.2    .035       0  4786.2     .09       0  4924.9     .04       0
  5075.1     .09       0    5150    .035       0    6200     .09       0
Bank Sta=4924.9,5075.1
Exp/Cntr=0.3,0.1

Type RM Length L Ch R = 1 ,345087  ,2249,2249,2249
BEGIN DESCRIPTION:
Dan River 52.0
END DESCRIPTION:
XS GIS Cut Line= 6
      1673967.18        947461.3      1673631.18        947053.7
      1673625.68       946921.51      1673508.04        946798.3
      1673289.68       946591.02      1672396.43       946171.92
#Sta/Elev= 30
  4171.3  665.03  4214.6  665.57  4452.6  648.07  4503.7  642.59  4551.8  632.87
    4585  627.33  4605.5  619.44    4637  614.54  4657.3  609.47  4724.3   606.1
  4849.7  606.47  4882.2  609.27  4905.7  609.35  4923.8  597.15  4923.9  594.08
  4932.3  594.08  4935.9  586.08  5064.1  586.08  5067.7  594.08  5081.8  609.63
  5116.3  608.78    5150  610.34  5425.6  609.37  6008.4  609.23  6129.8  610.67
  6157.3  612.14  6185.8  617.13  6250.5  638.02  6277.9  649.35  6289.9  652.35
#Mann= 6 ,-1 , 0
  4171.3     .06       0  4551.8     .09       0  4932.3     .04       0
  5067.7     .09       0    5150    .035       0  5425.6     .09       0
Bank Sta=4932.3,5067.7
Exp/Cntr=0.3,0.1

Type RM Length L Ch R = 1 ,342838  ,1853,1853,1853
BEGIN DESCRIPTION:
Dan River 50.0
END DESCRIPTION:
XS GIS Cut Line= 4
      1674975.16       945252.55      1674953.13       945070.78
      1674774.23       944985.66       1673534.7       944479.19
#Sta/Elev= 30
  4620.5  642.72  4725.7  637.01  4827.1   627.7  4848.3  623.36  4886.4  612.67
  4908.1  609.29  4932.4  603.55  4940.7  599.82  4947.3   592.2  4950.1   584.2
  5049.9   584.2  5052.7   592.2  5059.6  592.21  5070.9  600.27  5083.9  605.28
  5115.8   608.3  5127.3  606.19    5150   605.6  5244.4  607.37  5349.8  605.59
    5474  608.96  5697.5   605.3  5942.7  605.61    6047  604.27  6103.1  604.86
  6183.5  606.69  6215.7  608.58  6227.1  610.38  6268.2  621.37  6340.7  643.82
#Mann= 5 ,-1 , 0
  4620.5     .09       0  4947.3     .04       0  5052.7     .09       0
    5150    .035       0  5942.7     .09       0
Bank Sta=4947.3,5052.7
Exp/Cntr=0.3,0.1

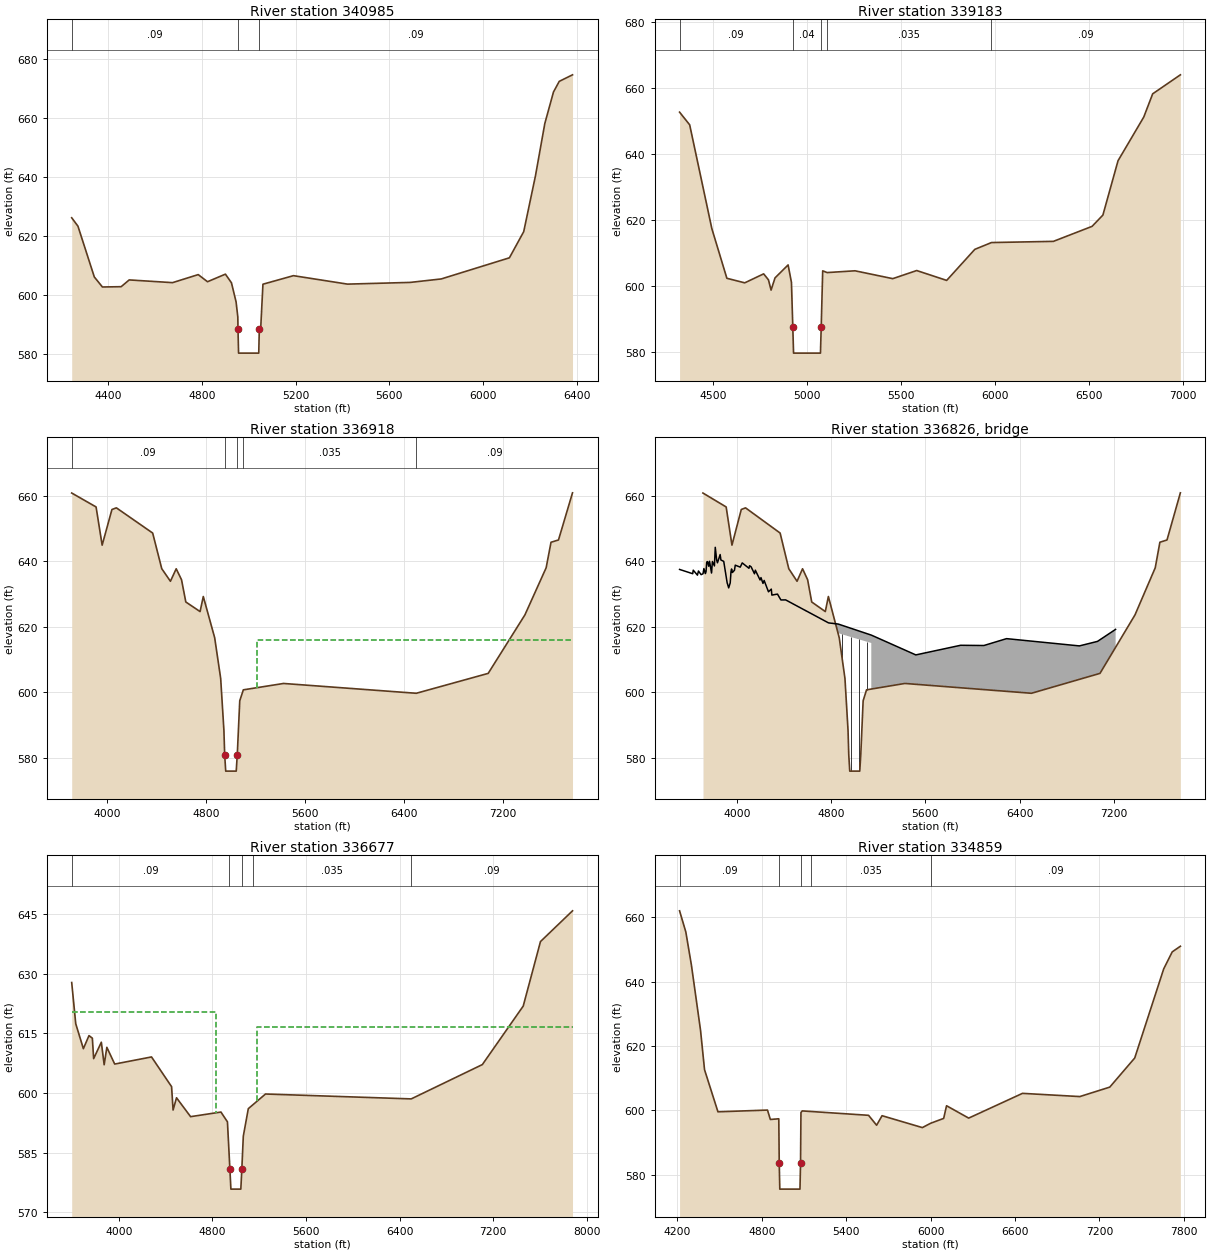
Type RM Length L Ch R = 1 ,340985  ,1802,1802,1802
BEGIN DESCRIPTION:
Dan River 48.0
END DESCRIPTION:
XS GIS Cut Line= 4
      1675668.52       943782.87      1675497.04       943486.11
      1675208.04       943218.52      1674074.49       942399.98
#Sta/Elev= 30
  4245.7  626.24  4272.3   623.4  4342.1  606.21  4376.6  602.82  4456.5  602.92
  4490.8  605.21  4675.7  604.29    4785  607.01  4824.6   604.6  4900.9  607.16
  4926.7  604.24  4946.4  597.77  4953.8  592.68  4954.6  588.44    4957  580.44
    5043  580.44  5045.4  588.44  5051.1  588.44  5060.9  603.76  5190.9  606.65
  5421.4  603.79  5688.7  604.37  5820.9  605.54  6111.5  612.69  6172.5  621.54
  6222.6  640.44  6262.4  658.12  6299.4   668.8    6324   672.4  6380.5  674.61
#Mann= 3 ,-1 , 0
  4245.7     .09       0  4954.6     .04       0  5045.4     .09       0
Bank Sta=4954.6,5045.4
Exp/Cntr=0.3,0.1

Type RM Length L Ch R = 1 ,339183  ,2265,2265,2265
BEGIN DESCRIPTION:
Dan River 47.0
END DESCRIPTION:
XS GIS Cut Line= 3
      1676835.02       942083.91      1676235.61       941784.21
      1674358.61        941109.3
#Sta/Elev= 30
  4321.9  652.54  4375.7   648.7  4493.6  617.25  4573.6  602.19  4668.7  600.81
  4769.3  603.53    4795  601.71  4808.8  598.61  4829.8  602.31  4899.4  606.24
  4917.2  600.95  4924.4  587.51  4928.4  579.51  5071.6  579.51  5075.6  587.51
  5083.5  604.45  5107.2  603.92  5255.4  604.46  5456.3  602.08  5583.7  604.54
  5743.2  601.55    5893  610.96  5981.5  613.02  6311.2  613.38  6516.9  617.93
  6574.5  621.35    6655  637.82  6791.8  651.04  6839.3  658.09  6986.7  663.85
#Mann= 5 ,-1 , 0
  4321.9     .09       0  4924.4     .04       0  5075.6     .09       0
  5107.2    .035       0  5981.5     .09       0
Bank Sta=4924.4,5075.6
Exp/Cntr=0.5,0.3

Type RM Length L Ch R = 1 ,336918  ,241,241,241
BEGIN DESCRIPTION:
US 311 HWYN - US
END DESCRIPTION:
XS GIS Cut Line= 6
      1678401.34       940457.83      1677031.25       939652.22
      1676576.38        939378.2      1676258.51       939115.14
      1676070.13        938929.5      1675200.28       938023.17
#Sta/Elev= 30
  3710.8  660.84  3908.1  656.58  3957.3  644.91  4036.4   655.8  4072.5  656.31
  4366.2  648.61  4439.8  637.71    4510  633.87  4556.7  637.69  4599.8  634.34
  4634.5  627.54  4749.9  624.61    4776  629.21  4868.1  616.62  4916.7  604.18
  4942.9  588.29    4949  580.85  4957.5  575.85  5042.5  575.85    5051  580.85
  5071.1  597.35    5100  600.69  5425.8  602.64    6500  599.64  7082.1  605.72
  7379.4   623.6  7551.3     638  7590.7   645.8  7651.1  646.49  7764.6   660.9
#Mann= 5 ,-1 , 0
  3710.8     .09       0    4949     .04       0    5051     .09       0
    5100    .035       0    6500     .09       0
#XS Ineff= 2 , 0
       0  4785.5  621.09  5214.5       0  615.89
Permanent Ineff=
       F       F
Bank Sta=4949,5051
Exp/Cntr=0.5,0.3

Type RM Length L Ch R = 3 ,336826  ,,,
BEGIN DESCRIPTION:
US 311 HWYN
Structure ID: US 311
Approximate Survey Structure
END DESCRIPTION:
Bridge Culvert--1,0,-1,-1, 0
Deck Dist Width WeirC Skew NumUp NumDn MinLoCord MaxHiCord MaxSubmerge Is_Ogee
74,36,3,0, 60, 60, , , , 0, 1,1,,
  3512.5    3624  3628.6  3664.2  3672.9  3695.4  3711.6  3719.1  3731.6  3737.2
  3743.1  3750.1    3760  3766.9  3783.8  3791.4  3808.4  3815.6  3827.9  3834.3
    3857  3863.5  3887.5  3916.2  3929.4  3942.5    3949    3954  3961.5  3978.7
  3985.4  4027.7  4044.5  4101.6  4106.8  4119.8  4148.7  4155.7    4196  4203.6
  4220.7  4230.5  4267.2  4291.3  4296.2  4343.9  4372.9  4413.1  4777.4  4859.5
  4859.5  5140.5  5140.5  5518.3  5898.7  6096.3  6288.7  6907.1  7060.9  7214.4
  637.49  636.18  637.26  635.74  637.01  635.89  636.17  637.75  636.22  636.82
  639.74  639.89  638.46  639.98  636.39  639.91  638.56  644.25  640.25  639.51
  642.04  640.38  639.94  633.46  631.85  633.37  636.79  637.63  636.56  637.25
  638.79  638.19  639.48  637.84  638.62  638.29  636.16  637.26  634.26  634.99
  633.22  634.12  630.66  631.47  629.65  629.95  628.16  628.18  621.15   620.8
   620.8  617.42  617.42  611.37  614.31  614.24  616.34  614.12   615.5  619.17
  555.85  555.85  555.85  555.85  555.85  555.85  555.85  555.85  555.85  555.85
  555.85  555.85  555.85  555.85  555.85  555.85  555.85  555.85  555.85  555.85
  555.85  555.85  555.85  555.85  555.85  555.85  555.85  555.85  555.85  555.85
  555.85  555.85  555.85  555.85  555.85  555.85  555.85  555.85  555.85  555.85
  555.85  555.85  555.85  555.85  555.85  555.85  555.85  555.85  555.85  555.85
     618     615  555.85  555.85  555.85  555.85  555.85  555.85  555.85  555.85
  3512.5    3624  3628.6  3664.2  3672.9  3695.4  3711.6  3719.1  3731.6  3737.2
  3743.1  3750.1    3760  3766.9  3783.8  3791.4  3808.4  3815.6  3827.9  3834.3
    3857  3863.5  3887.5  3916.2  3929.4  3942.5    3949    3954  3961.5  3978.7
  3985.4  4027.7  4044.5  4101.6  4106.8  4119.8  4148.7  4155.7    4196  4203.6
  4220.7  4230.5  4267.2  4291.3  4296.2  4343.9  4372.9  4413.1  4777.4  4859.5
  4859.5  5140.5  5140.5  5518.3  5898.7  6096.3  6288.7  6907.1  7060.9  7214.4
  637.49  636.18  637.26  635.74  637.01  635.89  636.17  637.75  636.22  636.82
  639.74  639.89  638.46  639.98  636.39  639.91  638.56  644.25  640.25  639.51
  642.04  640.38  639.94  633.46  631.85  633.37  636.79  637.63  636.56  637.25
  638.79  638.19  639.48  637.84  638.62  638.29  636.16  637.26  634.26  634.99
  633.22  634.12  630.66  631.47  629.65  629.95  628.16  628.18  621.15   620.8
   620.8  617.42  617.42  611.37  614.31  614.24  616.34  614.12   615.5  619.17
  555.85  555.85  555.85  555.85  555.85  555.85  555.85  555.85  555.85  555.85
  555.85  555.85  555.85  555.85  555.85  555.85  555.85  555.85  555.85  555.85
  555.85  555.85  555.85  555.85  555.85  555.85  555.85  555.85  555.85  555.85
  555.85  555.85  555.85  555.85  555.85  555.85  555.85  555.85  555.85  555.85
  555.85  555.85  555.85  555.85  555.85  555.85  555.85  555.85  555.85  555.85
     618     615  555.85  555.85  555.85  555.85  555.85  555.85  555.85  555.85
Pier Skew, UpSta & Num, DnSta & Num=  ,4894.6, 2 ,4894.6, 2 , 0 , 0 , 0 ,0,0
       2       2
  610.24     618
       2       2
  592.75     618
Pier Skew, UpSta & Num, DnSta & Num=  ,4964.9, 2 ,4964.9, 2 , 0 , 0 , 0 ,0,0
       2       2
     557     618
       2       2
  556.75     618
Pier Skew, UpSta & Num, DnSta & Num=  ,5035.1, 2 ,5035.1, 2 , 0 , 0 , 0 ,0,0
       2       2
     557     618
       2       2
  556.75     618
Pier Skew, UpSta & Num, DnSta & Num=  ,5105.4, 2 ,5105.4, 2 , 0 , 0 , 0 ,0,0
       2       2
  601.44     618
       2       2
  600.49     618
BR Coef= 1 , 1 , 0 ,1.25, 0 ,,,0.8,0,2,0,
WSPro=,,,, 1 ,,,, 0 ,,,, 0 ,,,,-1 ,-1 ,-1 , 0 , 0 , 0 , 0 , 0
BC Design=,, 0 ,, 0 ,,,,,,
BC HTab HWMax=660.95

Type RM Length L Ch R = 1 ,336677  ,1818,1818,1818
BEGIN DESCRIPTION:
US 311 HWYN - DS
END DESCRIPTION:
XS GIS Cut Line= 6
      1678536.29       940285.89      1677638.88        939744.7
      1677495.02       939614.54      1676974.39       939443.28
      1676700.37       939272.02      1675207.66       937698.31
#Sta/Elev= 30
  3595.8   627.8  3630.4  617.42  3695.6  611.15  3743.6  614.44  3772.4   613.8
  3783.5  608.65  3849.2  612.78  3873.5   607.1  3896.4  611.49  3963.6  607.28
  4278.6  609.07  4450.2  601.59    4463  595.71  4492.4  598.79  4612.8  594.04
  4872.4   595.2    4928  592.74  4944.5  583.36    4949   580.8  4957.5   575.8
  5042.5   575.8    5051   580.8  5063.7  589.13 5106.43  596.05 5253.52  599.74
    6500  598.51  7108.5  607.15  7458.2  621.88  7605.7  638.11  7879.7  645.85
#Mann= 5 ,-1 , 0
  3595.8     .09       0  4944.5     .04       0    5051     .09       0
    5150    .035       0    6500     .09       0
#XS Ineff= 2 , 0
       0  4834.3  620.38  5181.2       0  616.53
Permanent Ineff=
       F       F
Bank Sta=4949,5051
Exp/Cntr=0.5,0.3

Type RM Length L Ch R = 1 ,334859  ,3468,3468,3468
BEGIN DESCRIPTION:
Dan River 44.0
END DESCRIPTION:
XS GIS Cut Line= 3
      1678662.39       938291.07      1677794.84        937797.3
      1675251.96       937491.58
#Sta/Elev= 30
  4215.9  662.03  4260.4  655.45  4300.1  645.15    4365  624.84  4393.4   612.6
  4488.7  599.51 4840.82  600.05  4861.1  597.13  4921.1  597.34  4924.3  583.46
  4928.3  575.46  5071.7  575.46  5075.7  583.46 5078.65  599.28 5087.61  599.79
  5559.2  598.42  5616.4  595.34  5655.1   598.3  5941.5   594.6    6000  595.94
    6093  597.46  6113.5   601.4  6270.8  597.55  6653.2  605.25  7060.8  604.25
  7273.5  607.19    7451  616.25    7657  643.98  7717.5  649.26  7775.4  651.01
#Mann= 5 ,-1 , 0
  4215.9     .09       0  4924.3     .04       0  5075.7     .09       0
    5150    .035       0    6000     .09       0
Bank Sta=4924.3,5075.7
Exp/Cntr=0.3,0.1

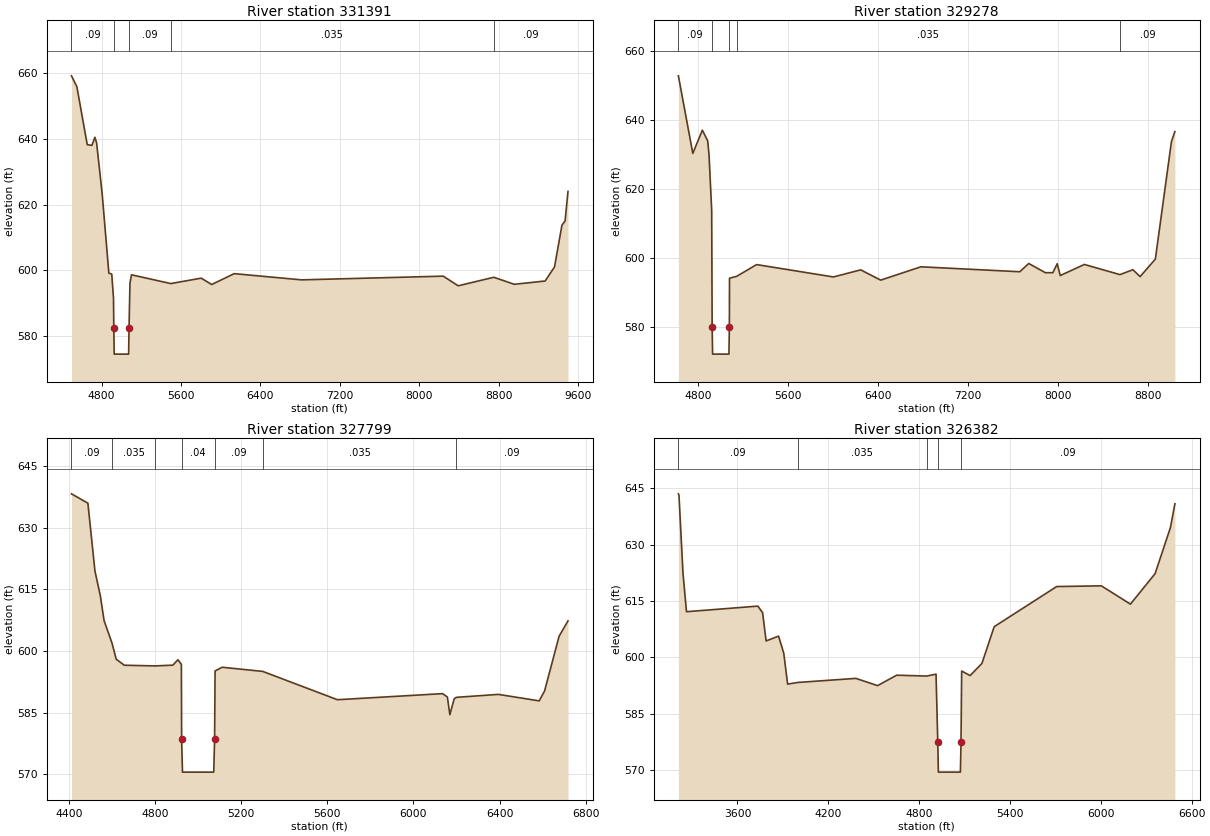
Type RM Length L Ch R = 1 ,331391  ,2113,2113,2113
BEGIN DESCRIPTION:
Dan River 42.0
END DESCRIPTION:
XS GIS Cut Line= 3
      1681226.64       936426.85      1680637.69       936041.76
      1676454.79       935061.32
#Sta/Elev= 30
  4497.2  659.25  4551.5  655.93  4655.8  638.28  4703.1  638.09    4733  640.54
  4750.1  638.84  4806.2  623.31  4873.6  599.17  4902.6  598.89  4920.2  591.55
  4923.4  582.52  4927.4  574.52  5072.6  574.52  5076.6  582.52  5086.1  596.12
  5101.7  598.67  5497.5     596  5803.7  597.65  5909.2  595.71  6135.7  599.02
  6814.8  597.13  8240.5  598.26  8391.6  595.32    8750  597.92    8956  595.78
  9266.8  596.78  9361.4  601.06  9436.2  613.77  9467.6  615.05  9497.2  624.05
#Mann= 5 ,-1 , 0
  4497.2     .09       0  4923.4     .04       0  5076.6     .09       0
  5497.5    .035       0    8750     .09       0
#XS Ineff= 2 , 0
       0                    7000       0
Permanent Ineff=
       F       F
Bank Sta=4923.4,5076.6
Exp/Cntr=0.3,0.1

Type RM Length L Ch R = 1 ,329278  ,1479,1479,1479
BEGIN DESCRIPTION:
Dan River 40.0
END DESCRIPTION:
XS GIS Cut Line= 4
      1680739.62       934037.04       1680207.3       934444.78
      1678864.44       934819.94      1676513.86       934871.78
#Sta/Elev= 30
  4623.2   652.9  4751.4  630.37  4836.3  637.11  4883.7  634.02  4895.9  629.85
  4919.3   613.8  4923.4  580.05  4927.4  572.05  5072.6  572.05  5076.6  580.05
  5077.7   594.1  5142.4  594.67  5318.9  598.06  6001.7  594.47  6244.4  596.53
  6422.5  593.55  6780.4  597.42  7659.3  595.98  7739.1  598.38  7887.3   595.7
  7953.9  595.71  7992.1  598.31  8019.4  594.88  8234.1   598.1    8550  595.15
  8665.7  596.57  8729.7  594.57  8865.3  599.66  9008.3  633.81  9039.1  636.69
#Mann= 5 ,-1 , 0
  4623.2     .09       0  4923.4     .04       0  5076.6     .09       0
  5142.4    .035       0    8550     .09       0
#XS Ineff= 2 , 0
       0                    7000       0
Permanent Ineff=
       F       F
Bank Sta=4923.4,5076.6
Exp/Cntr=0.3,0.1

Type RM Length L Ch R = 1 ,327799  ,1417,1417,1417
BEGIN DESCRIPTION:
Dan River 39.0
END DESCRIPTION:
XS GIS Cut Line= 6
      1680098.85       932980.12       1679726.3       933010.13
      1679519.08       933116.87       1678139.6       933590.03
      1678003.74       933526.88      1677955.36       933449.47
#Sta/Elev= 30
  4411.8  638.28    4488     636  4520.7   619.5    4546  613.38  4563.2  607.39
    4600  601.92  4619.7  597.98  4657.1  596.52    4800  596.36  4882.7  596.54
  4906.2  597.85  4922.3  596.73  4923.4  578.48  4927.4  570.48  5072.6  570.48
  5076.6  578.48  5078.8  595.13  5111.8  596.03    5300  595.02  5647.1  588.12
  6135.7   589.6  6157.8  588.79  6169.5  584.47  6189.5  588.35    6200   588.7
  6394.6  589.42  6584.4  587.84  6609.4  590.25  6676.8  603.59  6718.2  607.33
#Mann= 7 ,-1 , 0
  4411.8     .09       0    4600    .035       0    4800     .09       0
  4923.4     .04       0  5076.6     .09       0    5300    .035       0
    6200     .09       0
Bank Sta=4923.4,5076.6
Exp/Cntr=0.3,0.1

Type RM Length L Ch R = 1 ,326382  ,953,953,953
BEGIN DESCRIPTION:
Dan River 38.0
END DESCRIPTION:
XS GIS Cut Line= 6
      1680577.38       932529.41      1680132.23       932146.09
      1679846.62       932065.29      1678965.95       931857.36
      1678161.63       931667.07       1677582.8       931342.21
#Sta/Elev= 30
  3210.1  643.54    3214  643.11  3240.5  622.36  3263.6  612.14  3734.7  613.63
  3766.3  611.88  3789.4  604.35  3871.7  605.63  3906.1  601.07  3931.5  592.85
    4000   593.3  4382.1  594.38  4525.7  592.45  4651.6  595.23    4850     595
  4911.8  595.51  4923.3  577.41  4927.3  569.41  5072.7  569.41  5076.7  577.41
  5081.1  596.33  5137.1  595.13  5215.1  598.38  5295.9  608.15  5708.6  618.84
  6003.6  619.03  6195.7  614.16  6358.8  622.28  6460.1  634.58  6489.5  640.89
#Mann= 5 ,-1 , 0
  3210.1     .09       0    4000    .035       0    4850     .09       0
  4923.3     .04       0  5076.7     .09       0
Bank Sta=4923.3,5076.7
Exp/Cntr=0.3,0.1