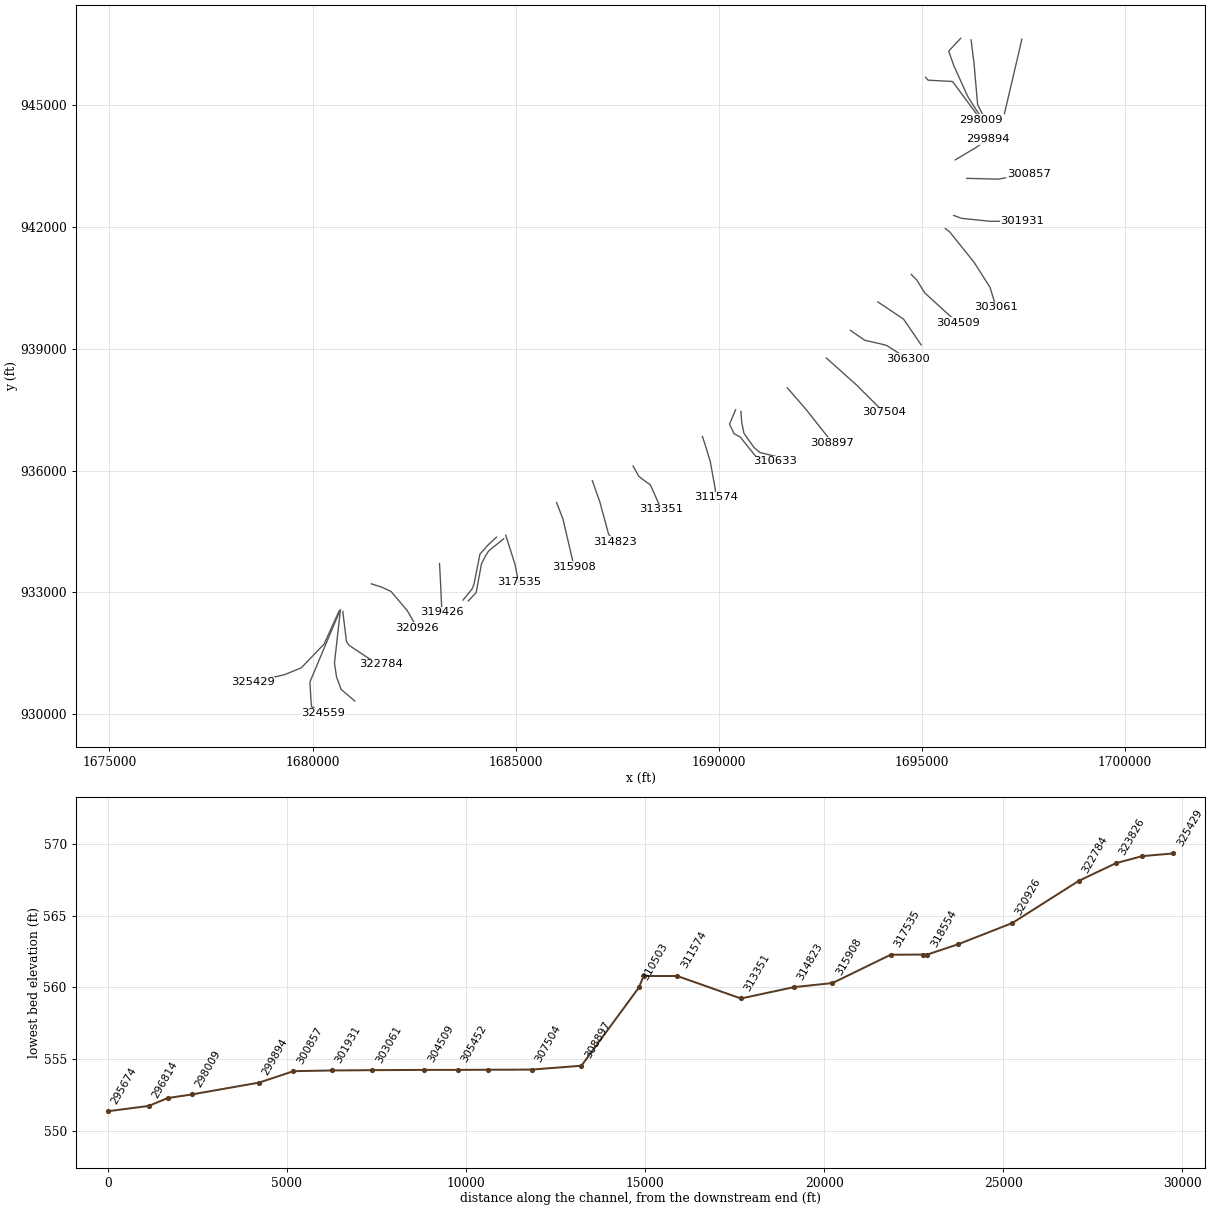
HEC-RAS study lds_dan_rvr_bctfud_lower.prj: Dan River Limited Detail Study Lower

--- lds_dan_rvr_bctfud_lower.g02 (geometry) --- (continued)

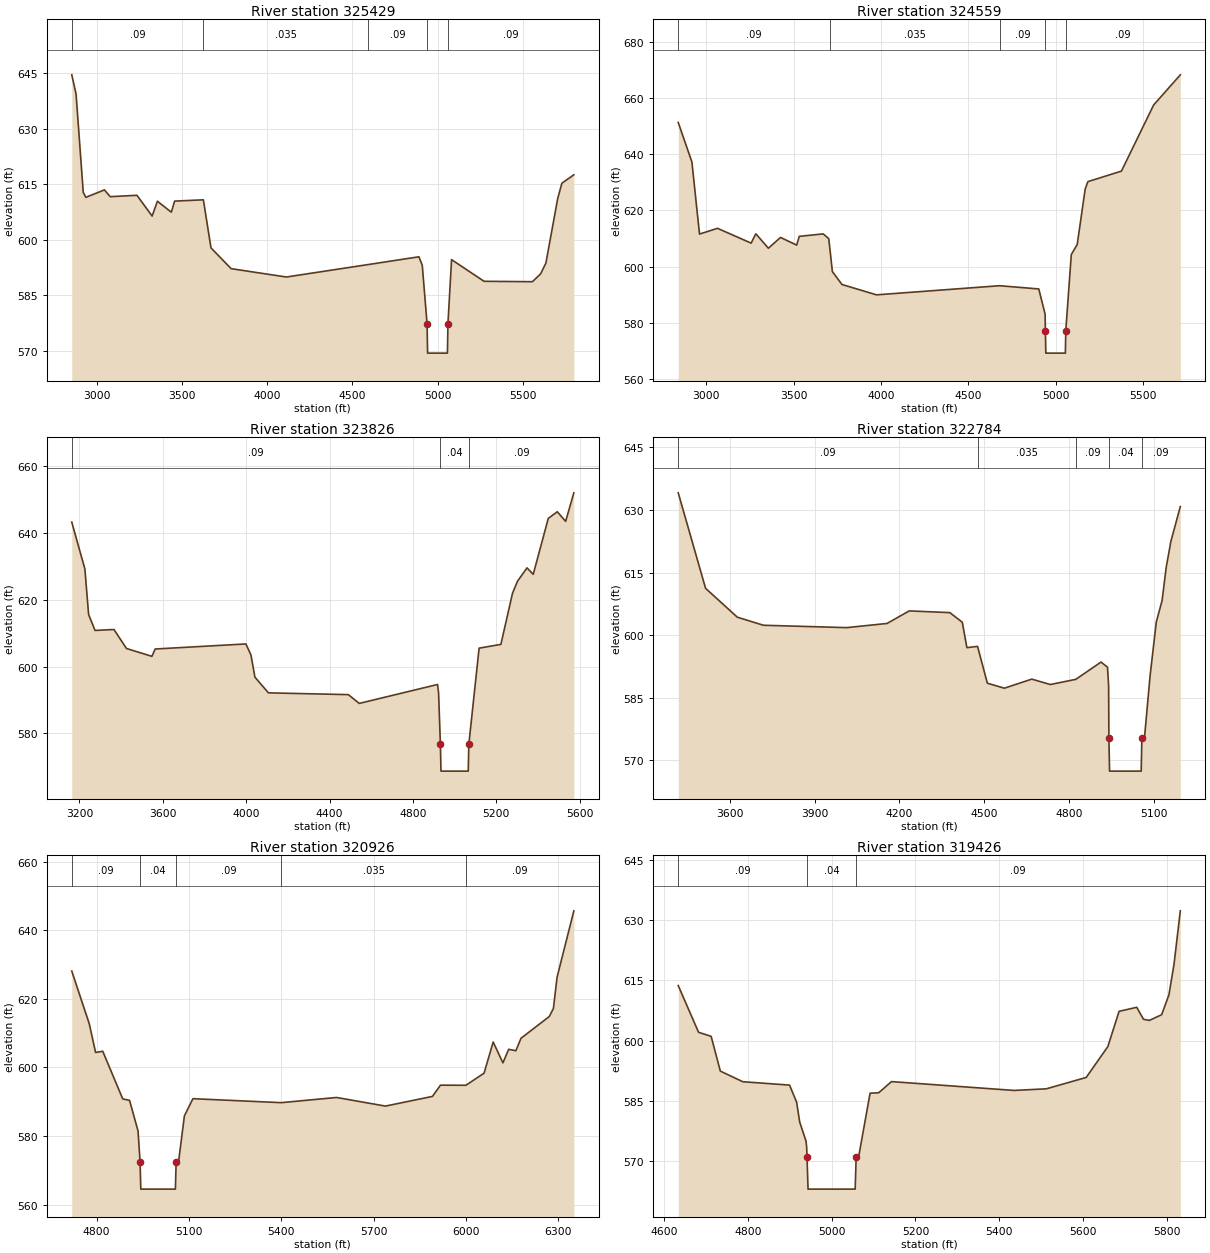
Type RM Length L Ch R = 1 ,325429  ,870,870,870
BEGIN DESCRIPTION:
Dan River 37.0
END DESCRIPTION:
XS GIS Cut Line= 5
      1680648.26       932529.41        1680283.       931722.76
       1679720.5       931137.07      1679308.78        930968.9
      1678521.47       930783.41
#Sta/Elev= 30
  2850.2  644.54  2875.5  639.35  2917.7  612.77  2933.2  611.45  3042.1  613.46
  3076.3  611.63  3233.4     612  3322.6  606.39  3353.6   610.4  3435.2  607.44
  3454.9  610.43  3623.8  610.78  3668.5  597.81    3787  592.18    4112  589.93
  4589.2  593.27  4890.6  595.39  4910.3  593.14  4938.6  577.37  4941.8  569.37
  5058.2  569.37  5061.4  577.37  5082.7  594.62  5273.7  588.77  5557.7  588.66
  5605.9  590.77  5637.2  593.69  5706.2  611.04    5731  615.26  5801.4  617.54
#Mann= 5 ,-1 , 0
  2850.2     .09       0  3623.8    .035       0  4589.2     .09       0
  4938.6     .04       0  5061.4     .09       0
Bank Sta=4938.6,5061.4
Exp/Cntr=0.3,0.1

Type RM Length L Ch R = 1 ,324559  ,733,733,733
BEGIN DESCRIPTION:
Dan River 36.7
END DESCRIPTION:
XS GIS Cut Line= 5
      1680681.29        932570.2      1679934.35        930789.8
      1679954.81       930421.45      1679973.09       930183.49
      1680265.24       930015.14
#Sta/Elev= 30
  2838.8  651.29  2917.1  637.24  2960.7  611.57  3063.7  613.62  3256.3  608.35
  3283.2  611.67  3355.1  606.53  3424.6  610.37  3517.2  607.64    3532  610.76
  3669.3  611.63  3700.7  609.94  3708.9  605.48  3721.7   598.2  3776.6  593.62
  3974.2  589.93  4679.2  593.18  4903.8  592.03    4940  583.06  4941.6  577.18
    4944  569.18    5056  569.18  5058.4  577.18    5090  604.27  5123.8  607.84
  5169.6  627.62    5185  630.24  5377.2  633.99  5561.5  657.52  5714.3  668.27
#Mann= 5 ,-1 , 0
  2838.8     .09       0  3708.9    .035       0  4679.2     .09       0
  4941.6     .04       0  5058.4     .09       0
Bank Sta=4941.6,5058.4
Exp/Cntr=0.3,0.1

Type RM Length L Ch R = 1 ,323826  ,1042,1042,1042
BEGIN DESCRIPTION:
Dan River 36.3
END DESCRIPTION:
XS GIS Cut Line= 5
      1680681.29       932539.51      1680538.04       931250.25
       1680589.2       930912.59      1680701.76       930605.62
      1681039.42       930319.12
#Sta/Elev= 30
  3163.5  643.23  3226.4  629.21  3244.4  615.55  3275.1  610.81    3366  611.08
  3426.1   605.4  3547.9  603.05  3563.9  605.25  3998.9  606.76  4023.1  603.45
  4042.1  596.82    4107  592.12  4490.2  591.59  4542.6  588.96  4918.4  594.63
  4923.2  592.07  4931.8  576.69  4934.6  568.69  5065.4  568.69  5068.2  576.69
  5117.5   605.5    5222  606.63  5277.9  621.97  5301.9  625.56  5347.4  629.54
  5377.2   627.6  5449.4  644.35  5492.7  646.33  5532.7  643.46    5572     652
#Mann= 3 ,-1 , 0
  3163.5     .09       0  4931.8     .04       0  5068.2     .09       0
Bank Sta=4931.8,5068.2
Exp/Cntr=0.3,0.1

Type RM Length L Ch R = 1 ,322784  ,1858,1858,1858
BEGIN DESCRIPTION:
Dan River 36.0
END DESCRIPTION:
XS GIS Cut Line= 5
      1680742.76       932529.41      1680834.03       931782.87
      1680902.05       931688.22      1681502.04       931291.46
      1681681.07       931228.56
#Sta/Elev= 30
  3416.8  634.13  3513.6  611.25  3625.9  604.34  3718.3   602.4  4013.2  601.83
    4156  602.83  4234.8  605.84  4378.4  605.43  4422.5  603.13  4438.9  597.04
  4476.6  597.34  4511.3  588.52  4571.4  587.32  4668.5  589.49  4734.3   588.2
  4824.5  589.44  4913.7  593.58  4936.7  592.35  4940.7  587.94  4941.6  575.45
    4944  567.45    5056  567.45  5058.4  575.45  5067.7  575.48  5087.3  590.14
  5109.4  603.15    5130  608.33  5144.4  616.19  5160.9  622.44  5194.5  630.84
#Mann= 5 ,-1 , 0
  3416.8     .09       0  4476.6    .035       0  4824.5     .09       0
  4941.6     .04       0  5058.4     .09       0
Bank Sta=4941.6,5058.4
Exp/Cntr=0.3,0.1

Type RM Length L Ch R = 1 ,320926  ,1500,1500,1500
BEGIN DESCRIPTION:
Dan River 35.0
END DESCRIPTION:
XS GIS Cut Line= 5
      1681444.46       933208.02      1681707.68       933122.86
      1681932.19       933018.35      1682330.89        932546.1
      1682573.77       932121.86
#Sta/Elev= 30
  4719.5  628.07  4776.3  612.74  4796.9  604.35  4820.2  604.69  4885.1   590.8
  4907.2  590.38  4934.8  581.47  4941.4   572.5  4943.8   564.5  5056.2   564.5
  5058.6   572.5  5066.5   572.5  5085.4  585.84  5113.1  590.87    5400  589.71
  5579.8  591.22  5738.4  588.71  5891.2  591.53  5917.5  594.81    6000  594.78
    6059   598.3  6088.6  607.39  6120.3  601.32    6139  605.26  6162.3  604.85
  6179.1  608.49  6271.1  614.84  6284.3  617.17  6296.2  626.27  6350.7  645.64
#Mann= 5 ,-1 , 0
  4719.5     .09       0  4941.4     .04       0  5058.6     .09       0
    5400    .035       0    6000     .09       0
Bank Sta=4941.4,5058.6
Exp/Cntr=0.3,0.1

Type RM Length L Ch R = 1 ,319426  ,872,872,872
BEGIN DESCRIPTION:
Dan River 34.0
END DESCRIPTION:
XS GIS Cut Line= 3
      1683124.41       933707.36      1683143.77       933347.37
      1683182.48       932511.27
#Sta/Elev= 30
  4634.2  613.69  4682.7  602.06  4712.7  601.06  4734.6  592.41  4788.1  589.76
  4899.7  588.92  4916.6  584.66  4923.9  579.72  4938.9     575  4940.5  573.54
  4941.4  571.03  4943.8  563.03  5056.2  563.03  5058.6  571.03  5064.4  571.03
  5091.8  586.91  5112.4  587.01  5142.8  589.79  5435.3  587.59  5511.9  587.99
  5607.2  590.82  5658.8  598.49  5685.7  607.28  5727.8  608.28  5743.9   605.3
  5757.9  605.02  5787.2  606.44  5804.6   611.4  5816.7  618.99  5831.7  632.29
#Mann= 3 ,-1 , 0
  4634.2     .09       0  4941.4     .04       0  5058.6     .09       0
Bank Sta=4941.4,5058.6
Exp/Cntr=0.5,0.3

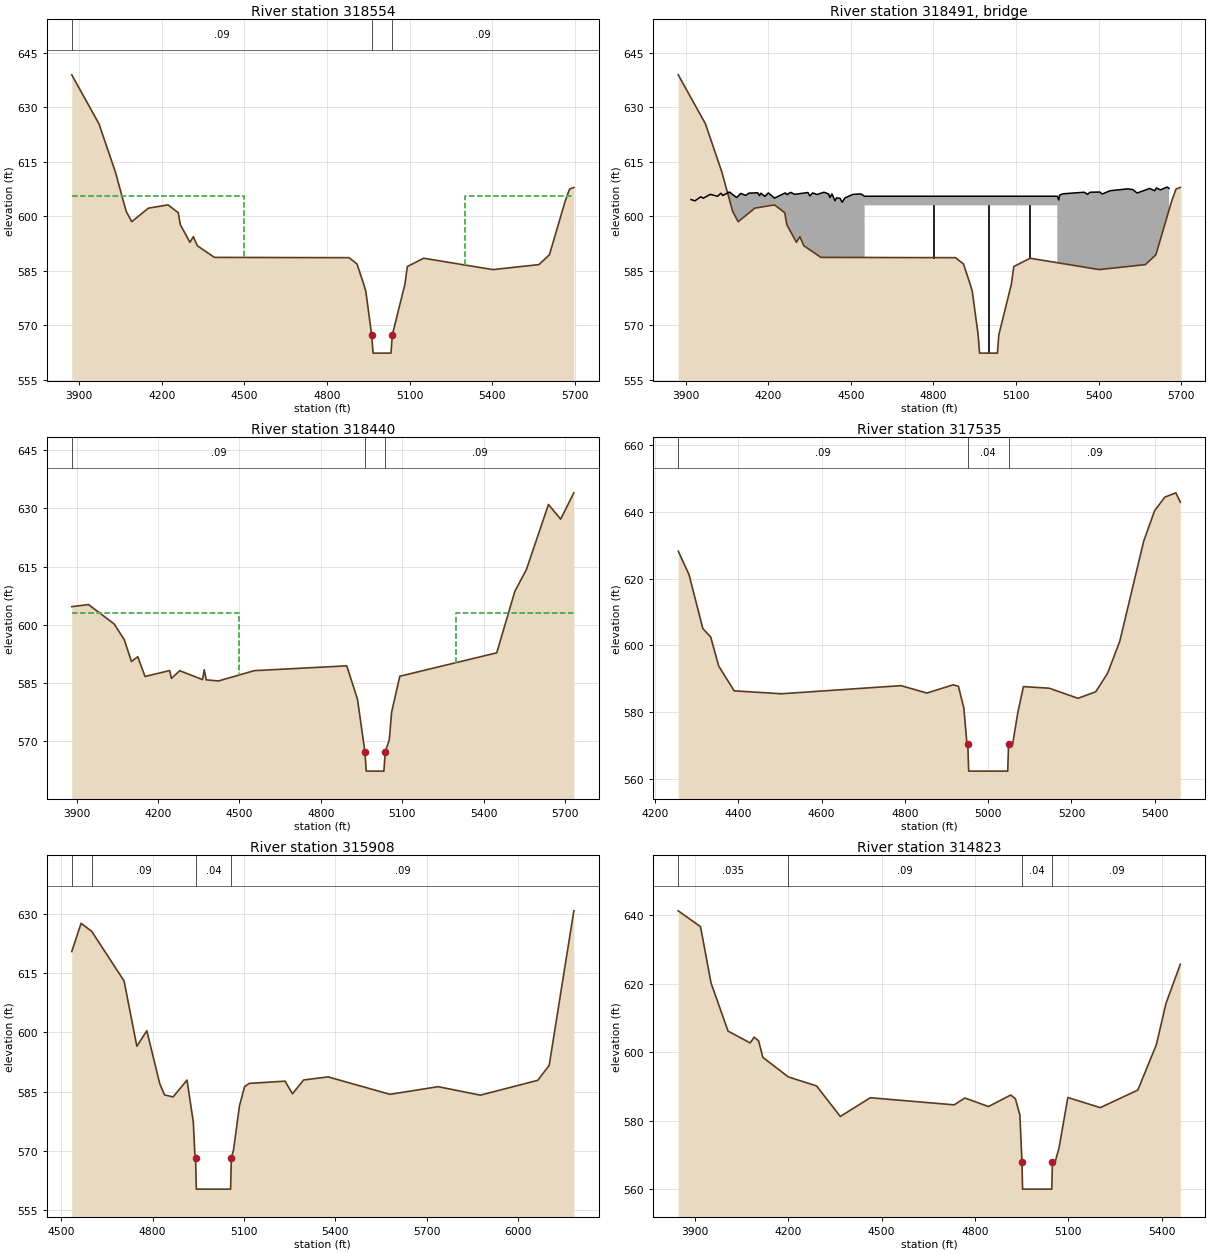
Type RM Length L Ch R = 1 ,318554  ,114,114,114
BEGIN DESCRIPTION:
Railroad - DS
END DESCRIPTION:
XS GIS Cut Line= 6
      1684525.67       934357.67      1684309.21       934155.42
        1684119.       933937.38      1683972.13       933196.41
      1683925.68       933080.28       1683701.9       932807.01
#Sta/Elev= 30
  3872.7  638.93  3971.4  625.46  4031.1   612.2  4070.4  601.33  4090.6  598.49
  4151.1  602.22  4222.4  603.12  4259.7  600.97  4267.3  597.64  4302.1  592.82
  4314.4  594.36  4329.2  591.86    4391  588.66  4880.4  588.58  4909.2  586.84
  4935.1  580.91  4941.1   579.3  4962.5   567.3  4967.5   562.3  5032.5   562.3
  5037.5   567.3  5083.3  581.34    5092  586.14  5151.3  588.43  5402.4   585.3
  5570.1  586.67  5608.2  589.37  5665.7  604.19  5681.6  607.48    5697  607.92
#Mann= 3 ,-1 , 0
  3872.7     .09       0  4962.5     .04       0  5037.5     .09       0
#XS Ineff= 2 , 0
       0    4500   605.5    5300       0   605.5
Permanent Ineff=
       F       F
Bank Sta=4962.5,5037.5
Exp/Cntr=0.5,0.3

Type RM Length L Ch R = 3 ,318491  ,,,
BEGIN DESCRIPTION:
Railroad
Structure ID: Railroad
Approximate Survey Structure
END DESCRIPTION:
Bridge Culvert--1,0,-1,-1, 0
Deck Dist Width WeirC Skew NumUp NumDn MinLoCord MaxHiCord MaxSubmerge Is_Ogee
51,24,3,0, 60, 60, 605.5, , , 0, 1,1,,
  3919.3  3933.3  3954.5  3963.8  3988.7  4015.8  4027.6  4034.8  4058.5  4084.9
  4100.1  4117.5  4129.8  4161.4  4167.8  4173.1    4187  4200.2  4222.6  4261.4
  4267.7  4281.4  4295.1  4343.9  4350.9  4361.4  4376.7  4402.2  4418.7    4424
  4431.2  4442.3    4448  4460.8  4468.2  4478.3  4506.7  4536.2    4550    4550
    5250  5250.1  5255.4  5258.4  5270.5  5347.9  5359.6  5369.4  5404.4  5413.4
  5441.2    5506  5524.3  5539.9  5585.7  5603.9  5610.1  5624.8  5648.5  5656.1
  604.58  604.23  605.34  604.96  606.01  605.49  606.32  605.71  606.67  605.16
  606.28  605.73  606.35  606.45  605.67  606.34  605.47  606.41  604.99  606.42
  605.94  606.57  606.03  606.52  605.58  606.42  605.97   606.6  606.15  605.15
  606.14  604.26  605.05  604.92  603.84  605.04     606  606.14   605.5   605.5
   605.5   605.5  604.45  605.82  606.17  606.61  606.03   606.6  606.66  606.11
  607.01  607.53  607.34  606.38  607.64  607.03   607.8  607.25  608.03  607.67
   542.3   542.3   542.3   542.3   542.3   542.3   542.3   542.3   542.3   542.3
   542.3   542.3   542.3   542.3   542.3   542.3   542.3   542.3   542.3   542.3
   542.3   542.3   542.3   542.3   542.3   542.3   542.3   542.3   542.3   542.3
   542.3   542.3   542.3   542.3   542.3   542.3   542.3   542.3   542.3     603
     603   542.3   542.3   542.3   542.3   542.3   542.3   542.3   542.3   542.3
   542.3   542.3   542.3   542.3   542.3   542.3   542.3   542.3   542.3   542.3
  3919.3  3933.3  3954.5  3963.8  3988.7  4015.8  4027.6  4034.8  4058.5  4084.9
  4100.1  4117.5  4129.8  4161.4  4167.8  4173.1    4187  4200.2  4222.6  4261.4
  4267.7  4281.4  4295.1  4343.9  4350.9  4361.4  4376.7  4402.2  4418.7    4424
  4431.2  4442.3    4448  4460.8  4468.2  4478.3  4506.7  4536.2    4550    4550
    5250  5250.1  5255.4  5258.4  5270.5  5347.9  5359.6  5369.4  5404.4  5413.4
  5441.2    5506  5524.3  5539.9  5585.7  5603.9  5610.1  5624.8  5648.5  5656.1
  604.58  604.23  605.34  604.96  606.01  605.49  606.32  605.71  606.67  605.16
  606.28  605.73  606.35  606.45  605.67  606.34  605.47  606.41  604.99  606.42
  605.94  606.57  606.03  606.52  605.58  606.42  605.97   606.6  606.15  605.15
  606.14  604.26  605.05  604.92  603.84  605.04     606  606.14   605.5   605.5
   605.5   605.5  604.45  605.82  606.17  606.61  606.03   606.6  606.66  606.11
  607.01  607.53  607.34  606.38  607.64  607.03   607.8  607.25  608.03  607.67
   542.3   542.3   542.3   542.3   542.3   542.3   542.3   542.3   542.3   542.3
   542.3   542.3   542.3   542.3   542.3   542.3   542.3   542.3   542.3   542.3
   542.3   542.3   542.3   542.3   542.3   542.3   542.3   542.3   542.3   542.3
   542.3   542.3   542.3   542.3   542.3   542.3   542.3   542.3   542.3     603
     603   542.3   542.3   542.3   542.3   542.3   542.3   542.3   542.3   542.3
   542.3   542.3   542.3   542.3   542.3   542.3   542.3   542.3   542.3   542.3
Pier Skew, UpSta & Num, DnSta & Num=  ,4800, 2 ,4800, 2 , 0 , 0 , 0 ,0,0
       2       2
  574.79     603
       2       2
  575.55     603
Pier Skew, UpSta & Num, DnSta & Num=  ,5000, 2 ,5000, 2 , 0 , 0 , 0 ,0,0
       2       2
     539     603
       2       2
  538.75     603
Pier Skew, UpSta & Num, DnSta & Num=  ,5150, 2 ,5150, 2 , 0 , 0 , 0 ,0,0
       2       2
  570.48     603
       2       2
  568.55     603
Abutment Skew #Up #Dn= , 2 , 2
    4550    4700
     603     574
    4550    4700
     603     574
Abutment Skew #Up #Dn= , 2 , 2
    5100    5250
     574     603
    5100    5250
     574     603
BR Coef= 1 , 1 , 0 ,1.25, 0 ,,,0.8,0,2,0,
WSPro=,,,, 1 ,,,, 0 ,,,, 0 ,,,,-1 ,-1 ,-1 , 0 , 0 , 0 , 0 , 0
BC Design=,, 0 ,, 0 ,,,,,,
BC HTab HWMax=638.93

Type RM Length L Ch R = 1 ,318440  ,905,905,905
BEGIN DESCRIPTION:
Railroad - US
END DESCRIPTION:
XS GIS Cut Line= 6
        1684706.       934319.07      1684332.41       934016.25
      1684253.54       933890.99      1684156.12       933696.15
      1684026.22       932990.99      1683831.38       932786.87
#Sta/Elev= 30
  3882.1   604.7  3943.7  605.24  4038.5  600.23  4075.7  596.17  4102.1  590.56
  4125.4  591.79  4152.1   586.7    4243  588.23  4249.5   586.2    4280  588.19
  4364.1  585.89  4370.3  588.44  4377.6  585.83  4422.7  585.54  4554.8   588.2
  4895.7  589.44  4935.3  580.79  4962.5   567.3  4967.5   562.3  5032.5   562.3
  5037.5   567.3  5052.3  570.35  5061.1  577.54  5091.1  586.76  5448.4   592.8
    5515  608.62  5557.8  614.27  5639.1  631.04    5684  627.25  5732.6  634.04
#Mann= 3 ,-1 , 0
  3882.1     .09       0  4962.5     .05       0  5037.5     .09       0
#XS Ineff= 2 , 0
       0    4500     603    5300       0     603
Permanent Ineff=
       F       F
Bank Sta=4962.5,5037.5
Exp/Cntr=0.5,0.3

Type RM Length L Ch R = 1 ,317535  ,1627,1627,1627
BEGIN DESCRIPTION:
Dan River 32.0
END DESCRIPTION:
XS GIS Cut Line= 5
      1684754.05       934407.99      1684978.56       933699.62
      1685040.49       933393.82      1685059.85       933328.02
      1685086.94        933250.6
#Sta/Elev= 30
  4255.6   628.2  4281.5  621.17  4314.7  605.01  4333.5  602.49  4352.9  593.75
    4390  586.34  4503.6  585.47  4790.7   587.9  4852.7  585.68  4915.8  588.14
  4928.4  587.73  4941.5  581.23  4949.1  570.31  4951.1  570.29  4953.1  562.29
  5046.9  562.29  5048.9  570.29  5058.6   570.3  5071.1   579.8  5084.6  587.61
  5146.7  587.13  5215.6  584.11  5258.2  586.06  5286.7   591.6    5316  601.19
  5373.5  631.22  5399.8  640.35  5424.3  644.38  5450.7  645.67  5461.4  642.87
#Mann= 3 ,-1 , 0
  4255.6     .09       0  4951.1     .04       0  5048.9     .09       0
Bank Sta=4951.1,5048.9
Exp/Cntr=0.3,0.1

Type RM Length L Ch R = 1 ,315908  ,1085,1085,1085
BEGIN DESCRIPTION:
Dan River 31.0
END DESCRIPTION:
XS GIS Cut Line= 3
      1686004.34       935213.13       1686163.2       934802.89
      1686437.88       933626.08
#Sta/Elev= 30
  4534.8  620.49  4565.2  627.62    4600  625.63  4706.5  613.05  4748.5   596.5
  4781.2  600.43  4823.4  587.09  4839.2  584.18  4867.4  583.66  4913.2  587.93
  4933.8  577.29  4938.7  569.46  4941.3  568.31  4943.7  560.31  5056.3  560.31
  5058.7  568.31  5065.7  570.16  5085.3  581.37  5101.9  586.23  5117.4  587.09
    5235  587.66  5259.3  584.46  5295.8  587.95  5376.1  588.74  5579.4  584.32
  5737.6  586.26  5876.2  584.11  6064.6  587.87  6102.1  591.65  6183.1   630.8
#Mann= 4 ,-1 , 0
  4534.8    .035       0    4600     .09       0  4941.3     .04       0
  5058.7     .09       0
Bank Sta=4941.3,5058.7
Exp/Cntr=0.3,0.1

Type RM Length L Ch R = 1 ,314823  ,1472,1472,1472
BEGIN DESCRIPTION:
Dan River 30.0
END DESCRIPTION:
XS GIS Cut Line= 4
      1686885.49       935748.44      1687069.45       935230.55
      1687286.03       934430.54      1687436.56       934249.29
#Sta/Elev= 30
  3846.1  641.29  3917.7  636.67  3951.7  620.18  4006.3  606.17  4077.2  602.72
  4090.3  604.37  4104.6   603.3  4118.1   598.5    4200  592.79  4290.8  590.16
  4367.1  581.24  4463.7  586.71  4733.2  584.63  4767.6  586.63  4843.5  584.14
  4915.1   587.5    4930  586.41  4944.4   581.7  4951.1  568.02  4953.1  560.02
    5047  560.02    5049  568.02  5058.1  568.02  5070.2  572.05  5098.7  586.77
  5202.8  583.82  5323.6  588.94  5383.2  602.19    5414  614.21  5460.2  625.69
#Mann= 4 ,-1 , 0
  3846.1    .035       0    4200     .09       0  4951.1     .04       0
    5049     .09       0
Bank Sta=4951.1,5049
Exp/Cntr=0.3,0.1

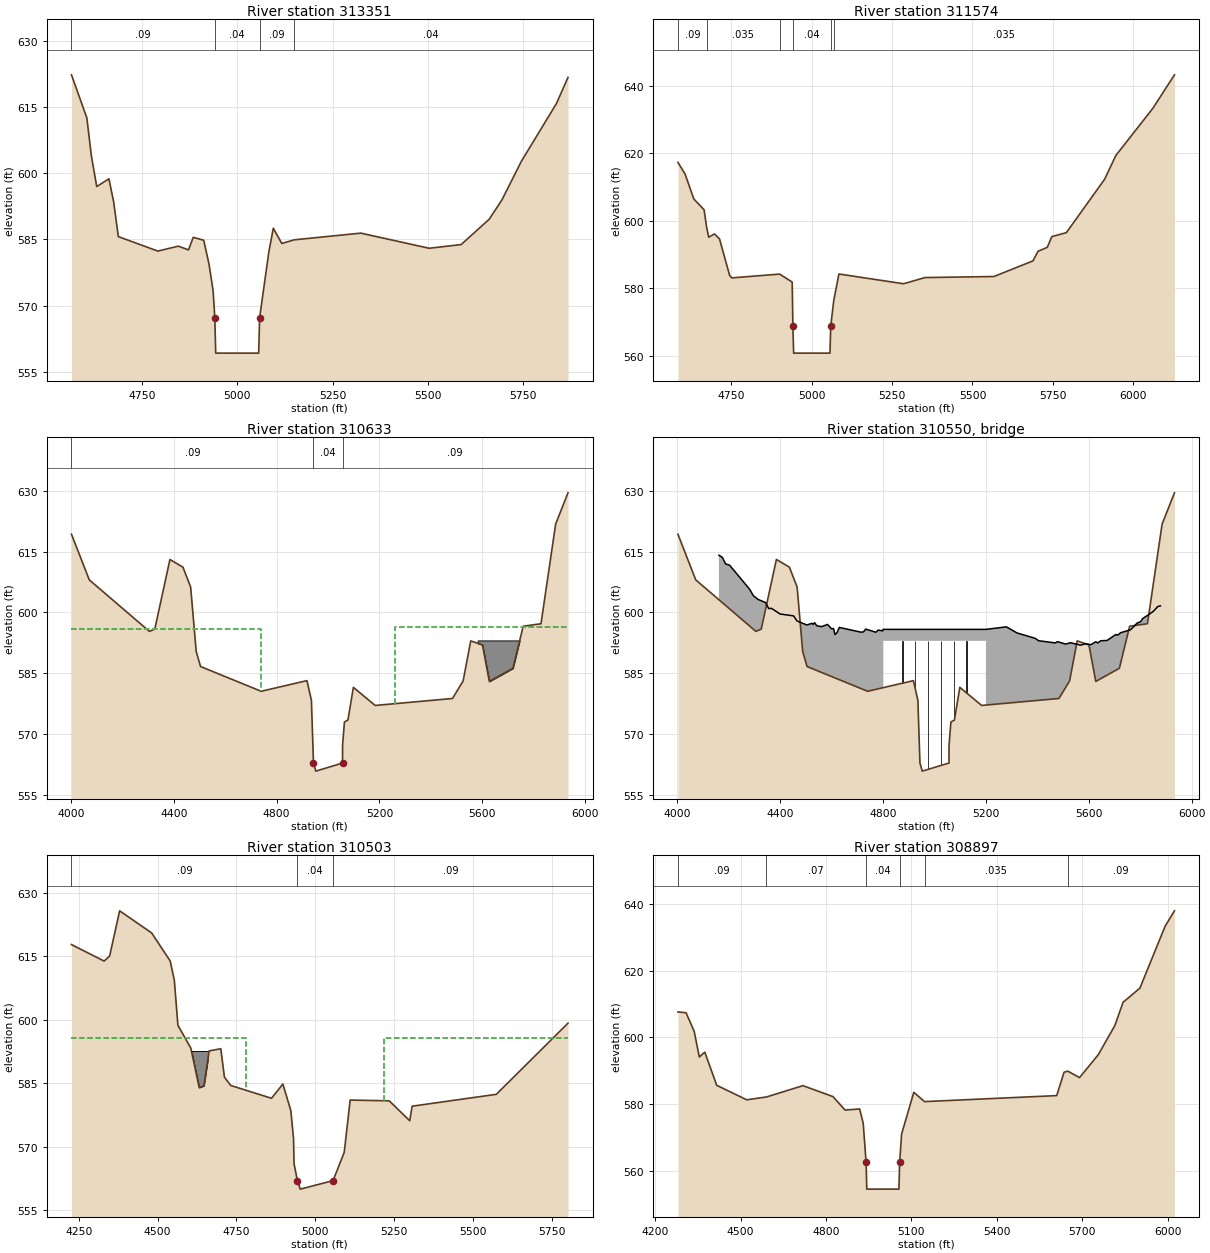
Type RM Length L Ch R = 1 ,313351  ,1777,1777,1777
BEGIN DESCRIPTION:
Dan River 29.0
END DESCRIPTION:
XS GIS Cut Line= 5
      1687889.45       936111.17      1688028.37       935858.43
      1688137.89       935773.24      1688312.32       935647.49
      1688584.11       935047.13
#Sta/Elev= 30
  4565.7  622.34    4606  612.56  4617.8  603.97  4631.8  597.01  4663.8  598.76
  4676.2  593.53  4688.5  585.65  4792.1  582.37  4845.6  583.49  4872.4  582.64
  4884.8  585.49  4912.2  584.83  4926.1  579.44  4936.9  573.35  4941.3  567.23
  4943.7  559.23  5056.3  559.23  5058.7  567.23  5082.9  582.16  5094.6  587.55
  5116.8   584.1    5150  584.93  5324.1  586.44    5503  583.01  5586.9  583.85
  5660.3  589.59  5693.6  593.95  5744.8  602.75  5836.7  615.84  5866.9  621.76
#Mann= 4 ,-1 , 0
  4565.7     .09       0  4941.3     .04       0  5058.7     .09       0
    5150     .04       0
Bank Sta=4941.3,5058.7
Exp/Cntr=0.3,0.1

Type RM Length L Ch R = 1 ,311574  ,941,941,941
BEGIN DESCRIPTION:
Dan River 27.0
END DESCRIPTION:
XS GIS Cut Line= 5
      1689596.89       936838.51      1689671.21       936606.26
      1689788.88       936225.36       1689909.6       935553.52
      1689933.23       935334.98
#Sta/Elev= 30
  4583.5   617.3  4605.7  613.83  4632.8  606.47  4664.7  603.27  4672.9  598.01
  4679.2  595.13    4697  596.11  4712.8  594.65  4744.4  583.79  4751.2  583.09
    4900  584.21    4939  581.85  4941.1   568.8  4943.5   560.8  5056.5   560.8
  5058.9   568.8  5068.2  576.29  5084.3  584.24  5285.5  581.35  5352.4  583.18
  5566.8  583.49  5688.2  588.12  5704.1  590.97  5732.7  592.13    5747  595.31
  5792.2  596.49  5911.3  612.32  5946.1  619.34  6061.6  633.35  6128.5  643.23
#Mann= 6 ,-1 , 0
  4583.5     .09       0  4672.9    .035       0    4900     .09       0
  4941.1     .04       0  5058.9     .09       0  5068.2    .035       0
Bank Sta=4941.1,5058.9
Exp/Cntr=0.5,0.3

Type RM Length L Ch R = 1 ,310633  ,130,130,130
BEGIN DESCRIPTION:
Pine Hall Rd. SR-1908 - US
END DESCRIPTION:
XS GIS Cut Line= 6
       1690412.5       937496.69      1690263.72         937144.
      1690374.94       936906.96      1690528.36       936824.97
      1690907.14       936348.86      1691373.25       936222.03
#Sta/Elev= 30
  4002.5  619.33  4071.7  608.06  4305.4  595.33  4326.4  595.88  4385.3   613.1
  4435.8   611.2  4465.9   606.3 4487.46  590.37 4504.35  586.65  4740.1  580.53
  4918.1  583.16  4935.5  578.29  4943.5   562.8  4952.5   560.8  5056.5   562.8
  5056.6  567.16  5063.9  572.94  5077.5  573.43  5098.7   581.5  5183.4  577.03
  5484.1  578.75 5525.43  583.08 5554.97  592.98  5600.5  591.99  5627.3  582.96
    5719  586.21  5759.1  596.61  5828.2  597.22  5885.2  621.85  5933.2  629.57
#Mann= 3 ,-1 , 0
  4002.5     .09       0  4943.5     .04       0  5056.5     .09       0
#XS Ineff= 2 , 0
       0    4739  595.81    5261       0  596.32
Permanent Ineff=
       F       F
#Block Obstruct= 1 ,-1
  5581.7  5748.1   593.1
Bank Sta=4943.5,5056.5
Exp/Cntr=0.5,0.3

Type RM Length L Ch R = 3 ,310550  ,,,
BEGIN DESCRIPTION:
Pine Hall Rd. SR-1908
Structure ID: Pine Hall Rd
Approximate Survey Structure
END DESCRIPTION:
Bridge Culvert--1,0,-1,-1, 0
Deck Dist Width WeirC Skew NumUp NumDn MinLoCord MaxHiCord MaxSubmerge Is_Ogee
61,44,3,0, 60, 60, , , , 0, 1,1,,
  4161.7  4175.1  4187.9  4203.3    4281  4295.2  4313.9  4342.9  4355.3  4365.9
  4399.9    4452  4465.4    4504  4523.9  4527.6  4533.9  4542.1  4561.1  4584.3
  4599.8  4607.5    4613  4621.1  4630.1  4714.7  4724.3  4732.8    4772  4781.2
  4798.7    4800    4800    5200    5200  5279.7  5320.6  5391.9  5404.5  5469.4
  5478.5  5509.9  5529.2  5567.9    5588  5607.7  5627.1  5635.3  5646.3  5671.3
  5705.1  5712.7  5723.8    5762  5788.2  5801.3  5809.8  5850.8  5868.4  5878.8
  614.15  613.63     612  611.69  605.77  604.19  603.23  602.46  600.98  601.02
  599.62  599.16   597.9  596.92  597.33  597.06  597.48  596.73   596.5  597.05
  595.96  596.04  594.54  595.05  596.31  595.13  595.23   595.9  595.12  595.65
  595.46  595.83  595.83  595.83  595.83  596.45  594.95  593.61  593.03  592.48
  592.79  592.19  592.53  591.93  592.29  592.03  592.77  592.48  593.01  593.09
  594.56  594.41     595  595.71  597.39  597.72   598.5  600.26  601.47  601.64
   540.8   540.8   540.8   540.8   540.8   540.8   540.8   540.8   540.8   540.8
   540.8   540.8   540.8   540.8   540.8   540.8   540.8   540.8   540.8   540.8
   540.8   540.8   540.8   540.8   540.8   540.8   540.8   540.8   540.8   540.8
   540.8   540.8     593     593   540.8   540.8   540.8   540.8   540.8   540.8
   540.8   540.8   540.8   540.8   540.8   540.8   540.8   540.8   540.8   540.8
   540.8   540.8   540.8   540.8   540.8   540.8   540.8   540.8   540.8   540.8
  4161.7  4175.1  4187.9  4203.3    4281  4295.2  4313.9  4342.9  4355.3  4365.9
  4399.9    4452  4465.4    4504  4523.9  4527.6  4533.9  4542.1  4561.1  4584.3
  4599.8  4607.5    4613  4621.1  4630.1  4714.7  4724.3  4732.8    4772  4781.2
  4798.7    4800    4800    5200    5200  5279.7  5320.6  5391.9  5404.5  5469.4
  5478.5  5509.9  5529.2  5567.9    5588  5607.7  5627.1  5635.3  5646.3  5671.3
  5705.1  5712.7  5723.8    5762  5788.2  5801.3  5809.8  5850.8  5868.4  5878.8
  614.15  613.63     612  611.69  605.77  604.19  603.23  602.46  600.98  601.02
  599.62  599.16   597.9  596.92  597.33  597.06  597.48  596.73   596.5  597.05
  595.96  596.04  594.54  595.05  596.31  595.13  595.23   595.9  595.12  595.65
  595.46  595.83  595.83  595.83  595.83  596.45  594.95  593.61  593.03  592.48
  592.79  592.19  592.53  591.93  592.29  592.03  592.77  592.48  593.01  593.09
  594.56  594.41     595  595.71  597.39  597.72   598.5  600.26  601.47  601.64
   540.8   540.8   540.8   540.8   540.8   540.8   540.8   540.8   540.8   540.8
   540.8   540.8   540.8   540.8   540.8   540.8   540.8   540.8   540.8   540.8
   540.8   540.8   540.8   540.8   540.8   540.8   540.8   540.8   540.8   540.8
   540.8   540.8     593     593   540.8   540.8   540.8   540.8   540.8   540.8
   540.8   540.8   540.8   540.8   540.8   540.8   540.8   540.8   540.8   540.8
   540.8   540.8   540.8   540.8   540.8   540.8   540.8   540.8   540.8   540.8
Pier Skew, UpSta & Num, DnSta & Num=  ,4875, 2 ,4875, 2 , 0 , 0 , 0 ,0,0
       2       2
  581.62     593
       2       2
  583.49     593
Pier Skew, UpSta & Num, DnSta & Num=  ,4925, 2 ,4925, 2 , 0 , 0 , 0 ,0,0
       2       2
  580.13     593
       2       2
  576.92     593
Pier Skew, UpSta & Num, DnSta & Num=  ,4975, 2 ,4975, 2 , 0 , 0 , 0 ,0,0
       2       2
     532     593
       2       2
  531.75     593
Pier Skew, UpSta & Num, DnSta & Num=  ,5025, 2 ,5025, 2 , 0 , 0 , 0 ,0,0
       2       2
     532     593
       2       2
  531.75     593
Pier Skew, UpSta & Num, DnSta & Num=  ,5075, 2 ,5075, 2 , 0 , 0 , 0 ,0,0
       2       2
  574.12     593
       2       2
     552     593
Pier Skew, UpSta & Num, DnSta & Num=  ,5125, 2 ,5125, 2 , 0 , 0 , 0 ,0,0
       2       2
  580.86     593
       2       2
  581.04     593
Abutment Skew #Up #Dn= , 2 , 2
    4800    4900
     593     564
    4800    4900
     593     564
Abutment Skew #Up #Dn= , 2 , 2
    5100    5200
     564     593
    5100    5200
     564     593
BR Coef= 1 , 1 , 0 ,1.25, 0 ,,,0.8,0,2,0,
WSPro=,,,, 1 ,,,, 0 ,,,, 0 ,,,,-1 ,-1 ,-1 , 0 , 0 , 0 , 0 , 0
BC Design=,, 0 ,, 0 ,,,,,,
BC HTab HWMax=629.6

Type RM Length L Ch R = 1 ,310503  ,1606,1606,1606
BEGIN DESCRIPTION:
Pine Hall Rd. SR-1908 - DS
END DESCRIPTION:
XS GIS Cut Line= 6
      1690543.67       937455.98      1690562.69       937189.63
      1690619.28       936915.08      1690866.06       936566.82
      1691013.81       936441.81      1691409.29        936346.2
#Sta/Elev= 30
    4227  617.73  4330.5  613.84    4348  615.03  4379.7   625.7  4481.3  620.48
    4540  613.86  4553.2  609.28  4564.5  598.68  4605.5  593.29    4632  583.98
    4647   584.4  4663.5  592.63  4700.5  593.14  4712.1  586.43  4732.1  584.47
  4861.3  581.45  4897.4  584.81  4922.5  578.58  4931.2  571.92  4932.8  566.02
  4943.5     562  4952.5     560  5056.5     562  5091.9  568.67  5110.8  581.03
  5234.8  580.84  5299.6  576.15  5307.4  579.58  5574.3  582.38  5801.6  599.18
#Mann= 3 ,-1 , 0
    4227     .09       0  4943.5     .04       0  5056.5     .09       0
#XS Ineff= 2 , 0
       0  4780.4  595.61  5217.1       0  595.78
Permanent Ineff=
       F       F
#Block Obstruct= 1 ,-1
  4607.1  4660.1   592.6
Bank Sta=4943.5,5056.5
Exp/Cntr=0.5,0.3

Type RM Length L Ch R = 1 ,308897  ,1393,1393,1393
BEGIN DESCRIPTION:
Dan River 25.0
END DESCRIPTION:
XS GIS Cut Line= 3
      1691687.16       938036.93      1692154.76       937495.01
      1692791.96       936687.56
#Sta/Elev= 30
  4280.1  607.66  4308.6  607.41  4337.1  601.86  4355.1  594.15  4374.4   595.6
  4416.4  585.65  4521.8  581.31    4591  582.16  4719.3  585.55  4824.7  582.27
  4867.4  578.24  4918.3  578.57  4930.9   574.3  4941.1  562.53  4943.5  554.53
  5056.5  554.53  5058.9  562.53  5065.8  571.04  5108.7  583.57  5146.3  580.77
  5610.7  582.57  5636.6  589.58  5649.8  589.91  5690.9  587.96  5756.7  594.83
  5814.9  603.55  5843.9  610.55    5903  614.79  5991.6  633.36  6024.4  637.97
#Mann= 6 ,-1 , 0
  4280.1     .09       0    4591     .07       0  4941.1     .04       0
  5058.9     .09       0  5146.3    .035       0  5649.8     .09       0
Bank Sta=4941.1,5058.9
Exp/Cntr=0.3,0.1

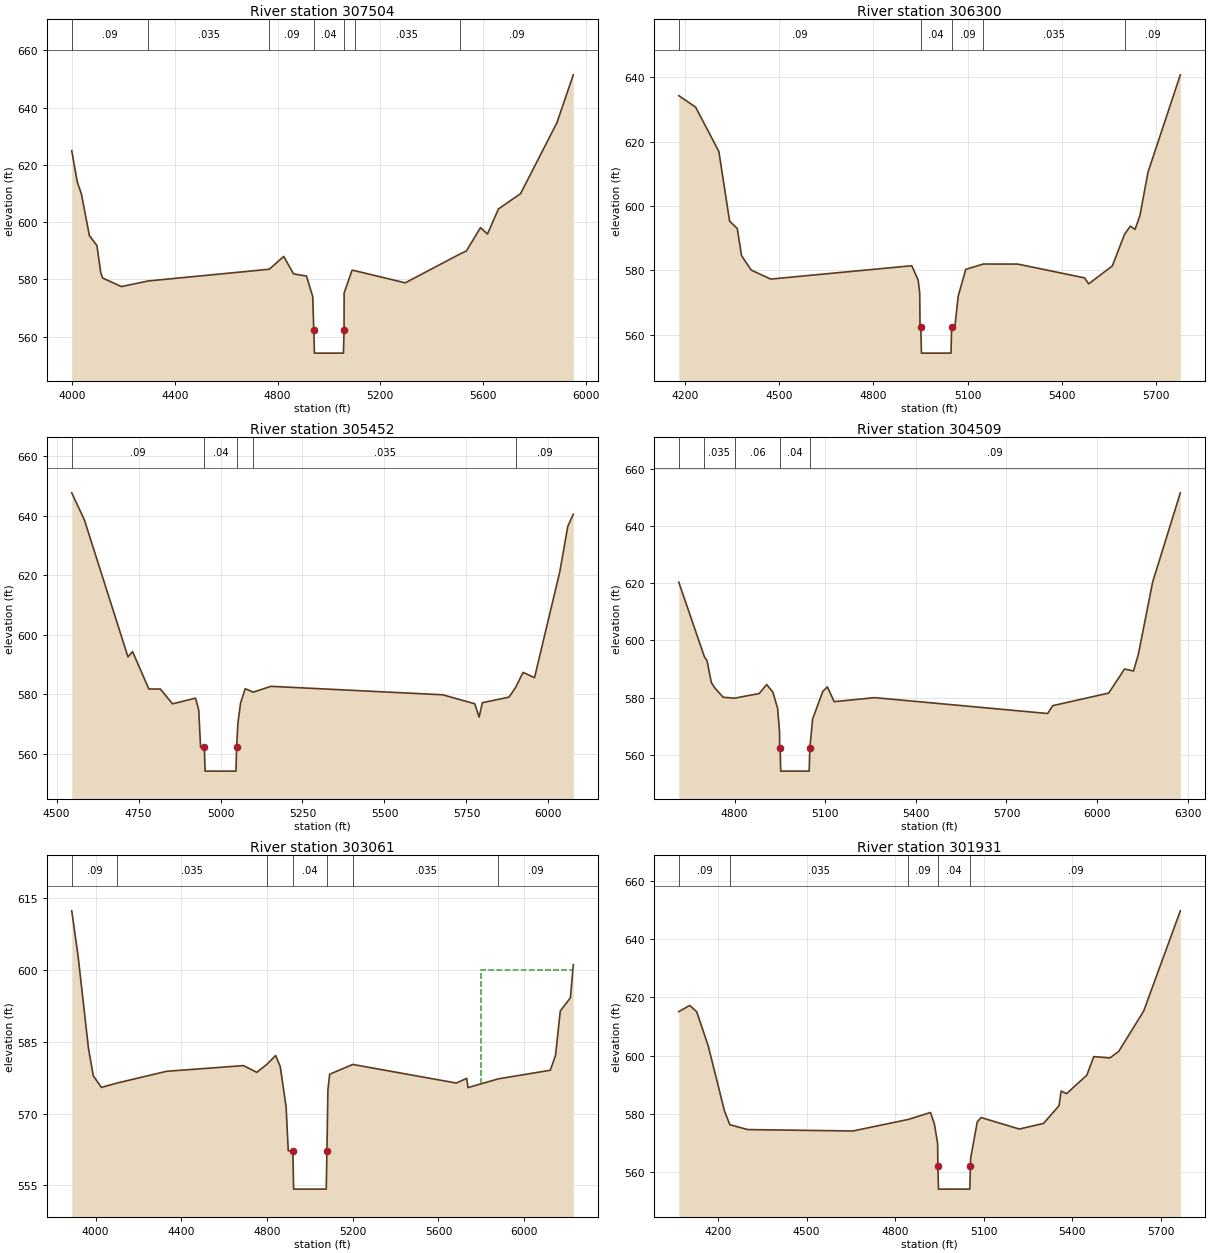
Type RM Length L Ch R = 1 ,307504  ,1204,1204,1204
BEGIN DESCRIPTION:
Dan River 24.0
END DESCRIPTION:
XS GIS Cut Line= 3
      1692647.43       938771.05      1693380.43       938114.96
      1694067.76       937431.78
#Sta/Elev= 30
  3998.6  624.93  4019.9   614.1  4036.6  609.69  4067.3  595.28  4096.7  591.81
  4111.8  582.19  4119.2  580.45    4192  577.49  4296.3  579.45  4767.5  583.54
  4824.1  588.01  4862.2  581.92  4912.6  581.18  4936.9  574.02  4941.1  562.26
  4943.5  554.26  5056.5  554.26  5058.9  562.26  5059.2  575.27  5090.3  583.23
    5100  583.05  5297.2   578.8  5508.9   588.8  5535.3  589.94  5590.2  598.07
  5617.4  595.84  5660.1  604.59  5746.1  609.92  5887.6  634.65  5951.5  651.41
#Mann= 7 ,-1 , 0
  3998.6     .09       0  4296.3    .035       0  4767.5     .09       0
  4941.1     .04       0  5058.9     .09       0    5100    .035       0
  5508.9     .09       0
Bank Sta=4941.1,5058.9
Exp/Cntr=0.3,0.1

Type RM Length L Ch R = 1 ,306300  ,848,848,848
BEGIN DESCRIPTION:
Dan River 23.0
END DESCRIPTION:
XS GIS Cut Line= 5
      1693239.35       939453.63      1693590.09       939209.49
      1693953.55        939127.9      1694129.94       939082.27
      1694649.16       938752.17
#Sta/Elev= 30
  4180.2  634.26  4233.7  630.71  4307.9  616.89    4342  595.26  4366.4  592.99
    4380  584.56  4410.7  580.06  4472.9  577.26  4922.2  581.41  4942.6  576.95
  4947.5  572.91  4948.5  562.25    4951  562.25    4953  554.25  5047.1  554.25
  5049.1  562.25  5059.3  562.25  5069.9  571.88    5094  580.27    5150  581.94
  5259.6  581.92  5472.2  577.64  5485.7  575.78  5560.8  581.33    5600  591.21
  5618.3  593.71  5633.3   592.7  5648.5  596.88  5674.6   610.5  5777.5  640.73
#Mann= 5 ,-1 , 0
  4180.2     .09       0    4951     .04       0  5049.1     .09       0
    5150    .035       0    5600     .09       0
Bank Sta=4951,5049.1
Exp/Cntr=0.3,0.1

Type RM Length L Ch R = 1 ,305452  ,943,943,943
BEGIN DESCRIPTION:
Dan River 22.0
END DESCRIPTION:
XS GIS Cut Line= 4
      1693916.25       940153.75      1694273.42       939914.27
      1694549.28       939727.79      1694981.15       939094.77
#Sta/Elev= 30
  4546.4  647.61    4585  638.53  4717.9  592.55  4731.8  594.34  4781.6  581.79
  4816.5  581.79  4853.7  576.82    4924  578.73  4933.7  574.68  4939.2  562.24
  4950.9  562.24  4952.9  554.24  5047.1  554.24  5049.1  562.24    5053  570.18
  5061.1  577.05  5075.4  581.89    5100  580.73  5153.4  582.69  5677.5  579.85
  5775.4  576.84  5788.5  572.37  5798.3   577.2  5879.8  579.07    5900  582.35
  5922.6  587.36  5957.5  585.59  6034.5  621.11  6058.9  636.34  6075.7  640.43
#Mann= 5 ,-1 , 0
  4546.4     .09       0  4950.9     .04       0  5049.1     .09       0
    5100    .035       0    5900     .09       0
Bank Sta=4950.9,5049.1
Exp/Cntr=0.3,0.1

Type RM Length L Ch R = 1 ,304509  ,1448,1448,1448
BEGIN DESCRIPTION:
Dan River 21.0
END DESCRIPTION:
XS GIS Cut Line= 4
      1694736.75         940831.      1694868.75       940699.81
      1695067.53       940377.97      1695876.85       939639.64
#Sta/Elev= 30
  4615.5  620.42    4700  594.37  4708.9   592.9  4723.3  585.26  4735.1  583.34
  4762.2  580.12    4800  579.79  4881.6  581.42  4906.4  584.57  4926.9  581.91
  4942.6  576.21    4949  567.93  4949.4  562.24  4950.9  562.24  4952.9  554.24
  5047.1  554.24  5049.1  562.24  5058.5   572.5    5092  582.17  5107.3  583.74
  5129.8  578.57  5263.8  579.98    5836  574.42  5853.4  577.18  6038.3  581.58
  6090.8  590.01  6120.5  589.31  6136.6  595.22  6183.8  620.49  6275.4  651.72
#Mann= 5 ,-1 , 0
  4615.5     .09       0    4700    .035       0    4800     .06       0
  4950.9     .04       0  5049.1     .09       0
Bank Sta=4950.9,5049.1
Exp/Cntr=0.3,0.1

Type RM Length L Ch R = 1 ,303061  ,1130,1130,1130
BEGIN DESCRIPTION:
Dan River 20.0
END DESCRIPTION:
XS GIS Cut Line= 5
      1695573.95       941961.95      1695684.25       941878.34
      1696285.99       941127.14      1696676.71       940510.49
      1696826.08       940023.17
#Sta/Elev= 30
  3888.5   612.3  3917.8  602.99  3966.6  583.58    3989  577.88  4026.8  575.45
    4100  576.36  4331.1  578.81  4689.7     580    4752   578.6    4800  580.29
  4840.1  582.11  4861.6  579.78  4888.9  571.39  4898.9  562.22  4920.6  562.22
  4923.8  554.22  5076.2  554.22  5079.4  562.22    5084  574.96  5092.2   578.2
    5200  580.24  5683.2  576.36  5731.9  577.34  5737.6  575.41  5879.9  577.24
  6121.8  579.03    6146  582.07  6168.5  591.41  6215.7  594.15  6229.1  601.07
#Mann= 7 ,-1 , 0
  3888.5     .09       0    4100    .035       0    4800     .09       0
  4920.6     .04       0  5079.4     .09       0    5200    .035       0
  5879.9     .09       0
#XS Ineff= 2 , 0
       0                    5800       0     600
Permanent Ineff=
       F       F
Bank Sta=4920.6,5079.4
Exp/Cntr=0.3,0.1

Type RM Length L Ch R = 1 ,301931  ,1074,1074,1074
BEGIN DESCRIPTION:
Dan River 19.0
END DESCRIPTION:
XS GIS Cut Line= 4
      1695782.19       942285.32      1695971.51       942214.33
      1696685.83       942140.08      1697463.98       942145.14
#Sta/Elev= 30
  4067.5  615.12  4104.6  617.26  4128.3  615.06  4167.6  603.21  4222.3     581
  4240.5   576.3  4300.9  574.64  4657.4  574.16  4845.1  578.13  4919.7   580.5
  4933.2  576.54  4944.1  569.76  4944.9   562.2  4946.9   554.2  5053.1   554.2
  5055.1   562.2    5056   564.9  5078.4  577.33  5091.4  578.76  5220.7  574.83
  5302.8  576.76  5355.3  582.85  5362.3  587.85  5380.6  586.97  5449.2  593.29
    5473  599.68  5527.5  599.23  5557.4  601.49  5641.8   615.3    5766  649.72
#Mann= 5 ,-1 , 0
  4067.5     .09       0  4240.5    .035       0  4845.1     .09       0
  4944.9     .04       0  5055.1     .09       0
Bank Sta=4944.9,5055.1
Exp/Cntr=0.3,0.1

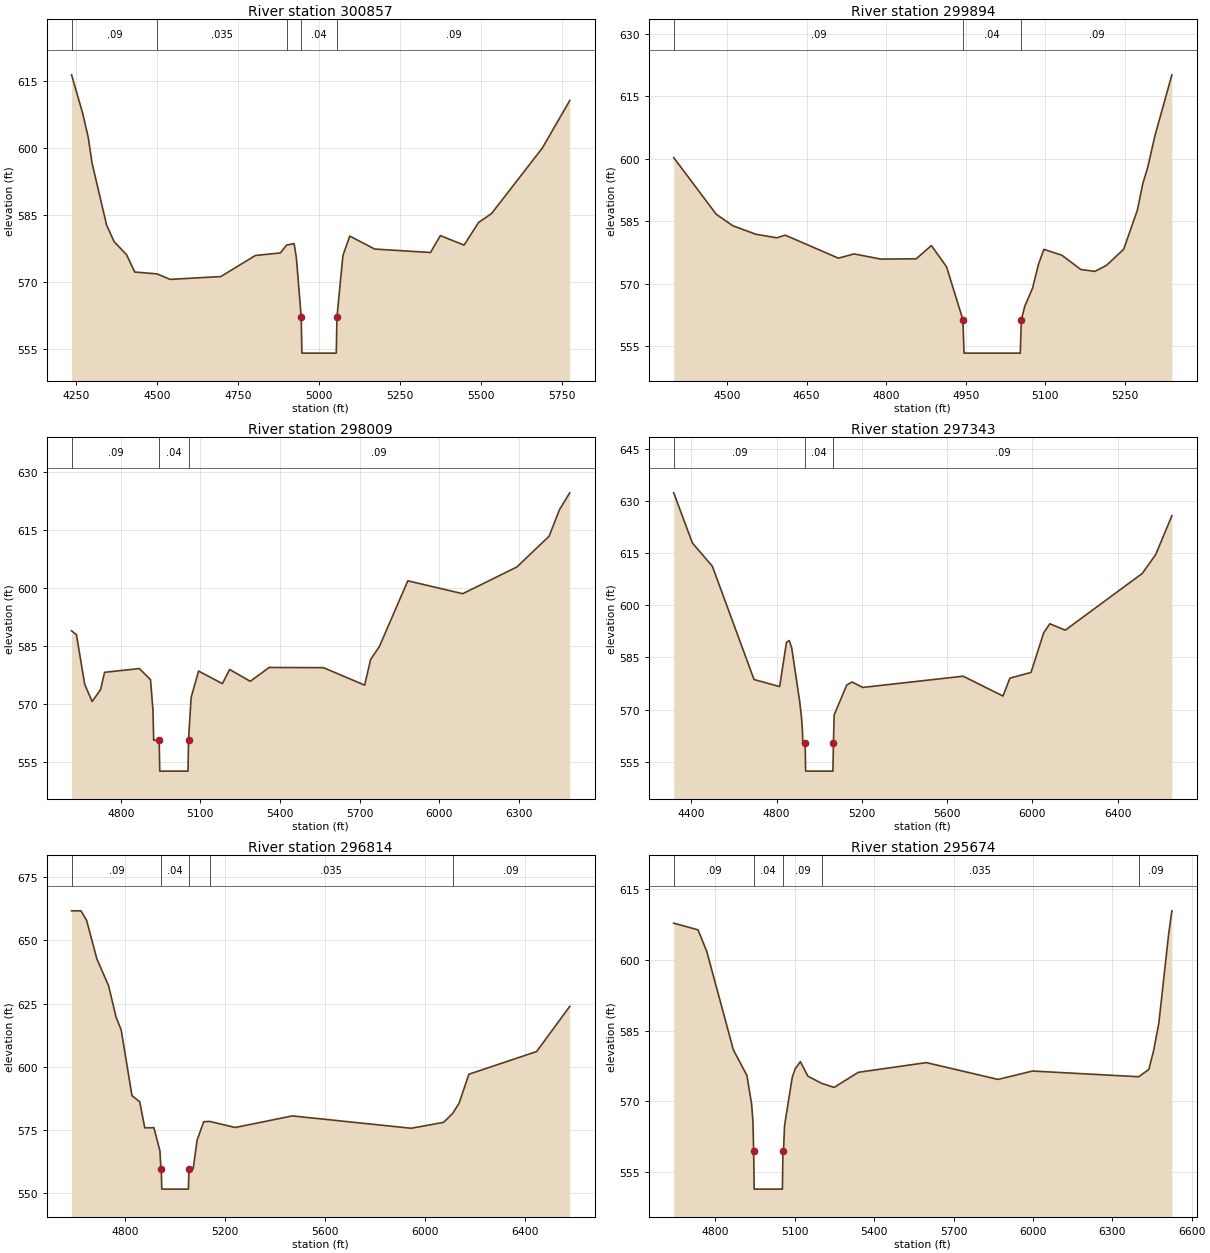
Type RM Length L Ch R = 1 ,300857  ,963,963,963
BEGIN DESCRIPTION:
Dan River 18.0
END DESCRIPTION:
XS GIS Cut Line= 4
      1696102.71       943199.39      1696872.43       943179.69
      1697384.44       943268.29      1697630.23        943302.2
#Sta/Elev= 30
    4236  616.46  4270.6  607.76  4287.5  602.42  4299.1  596.75  4344.1  582.83
  4367.2  579.12  4405.8  576.18    4431  572.31    4500  571.89  4540.2  570.66
  4696.6  571.29  4803.3  576.01  4880.3  576.58    4900  578.35    4923  578.67
    4930  575.44  4944.9  562.15  4946.9  554.15  5053.1  554.15  5055.1  562.15
  5073.6     576  5094.6  580.36  5171.7  577.45  5343.9  576.68  5374.4  580.46
  5447.5  578.34  5492.5  583.42  5532.4   585.4  5689.1  600.07  5773.7   610.7
#Mann= 5 ,-1 , 0
    4236     .09       0    4500    .035       0    4900     .09       0
  4944.9     .04       0  5055.1     .09       0
Bank Sta=4944.9,5055.1
Exp/Cntr=0.3,0.1

Type RM Length L Ch R = 1 ,299894  ,1885,1885,1885
BEGIN DESCRIPTION:
Dan River 17.0
END DESCRIPTION:
XS GIS Cut Line= 3
      1695819.97        943654.7      1696326.48       943956.03
       1696613.1       944157.76
#Sta/Elev= 30
  4399.3  600.28  4479.4  586.69  4510.8  583.92  4554.3  581.88  4593.7  581.03
  4609.5  581.67  4709.9  576.15  4739.7  577.16  4789.9  575.92  4856.7  575.99
  4885.4  579.17    4914  574.06  4944.9  561.35  4946.9  553.35  5053.1  553.35
  5055.1  561.35  5061.6  564.62  5076.3  568.97  5087.4  574.66  5097.6  578.26
  5131.6  576.85  5167.2  573.43  5193.9  572.97  5215.8  574.43  5248.2   578.3
    5274  587.67  5284.2  594.04  5293.4  597.89  5307.2  605.57  5339.1  620.15
#Mann= 3 ,-1 , 0
  4399.3     .09       0  4944.9     .04       0  5055.1     .09       0
Bank Sta=4944.9,5055.1
Exp/Cntr=0.3,0.1

Type RM Length L Ch R = 1 ,298009  ,666,666,666
BEGIN DESCRIPTION:
Dan River 16.0
END DESCRIPTION:
XS GIS Cut Line= 4
      1695089.58       945689.02      1695152.19        945618.3
      1695752.43       945586.29      1696453.97       944637.67
#Sta/Elev= 30
  4614.9  588.89  4633.3  587.88  4664.4     575  4692.3  570.57  4723.9  573.62
  4739.1  578.13  4870.1  579.11    4912  576.24  4921.3  568.34    4924  560.52
  4944.8  560.52  4946.8  552.52  5053.2  552.52  5055.2  560.52  5064.9  571.59
    5093  578.46  5182.7   575.2    5210  578.87  5287.6   575.8  5358.7  579.39
    5563  579.34  5718.3  574.81  5740.5  581.41  5773.7  584.83  5880.8  601.85
  6087.5  598.51  6291.4  605.44  6412.7  613.42  6451.5  620.27  6490.3  624.66
#Mann= 3 ,-1 , 0
  4614.9     .09       0  4944.8     .04       0  5055.2     .09       0
Bank Sta=4944.8,5055.2
Exp/Cntr=0.3,0.1

Type RM Length L Ch R = 1 ,297343  ,529,529,529
BEGIN DESCRIPTION:
Dan River 15.5
END DESCRIPTION:
XS GIS Cut Line= 6
      1695952.69       946649.35      1695658.82       946334.85
      1695787.71        945968.8      1696127.99       945216.06
      1696318.75       944911.87      1696509.51       944638.61
#Sta/Elev= 30
  4317.2  632.37  4404.7  617.95  4498.4  611.24    4694  578.63  4814.1  576.61
    4846  589.33  4859.2  589.88  4870.8  587.71  4908.5  572.13    4917   567.4
  4921.4  563.54  4922.3  560.29  4933.6  560.27    4936  552.27    5064  552.27
  5066.4  560.27  5069.7  568.44  5129.1  577.08    5154  577.92  5203.7  576.36
    5675  579.59  5861.8  573.88  5894.1  579.03  5993.2  580.68  6052.7  592.07
  6081.5  594.68  6153.8  592.84  6514.8  609.15  6577.8  614.56  6654.1  625.77
#Mann= 3 ,-1 , 0
  4317.2     .09       0  4933.6     .04       0  5066.4     .09       0
#XS Ineff= 2 , 0
       0    4846                       0
Permanent Ineff=
       F       F
Bank Sta=4933.6,5066.4
Exp/Cntr=0.3,0.1

Type RM Length L Ch R = 1 ,296814  ,1140,1140,1140
BEGIN DESCRIPTION:
Dan River 15.0
END DESCRIPTION:
XS GIS Cut Line= 4
      1696209.19        946610.6      1696279.29       946061.18
      1696370.89       945016.03      1696548.47        944667.2
#Sta/Elev= 30
  4585.5  661.62  4623.3  661.61  4645.3  657.97  4686.9  642.61  4733.6  632.06
  4763.5  619.71  4784.2  614.55  4827.3  588.64  4858.4  586.19  4878.6  575.91
  4915.1  575.99  4939.3  566.83  4943.3  559.72  4944.7  559.72  4946.7  551.72
  5053.4  551.72  5055.4  559.72  5072.3  559.79  5088.2  571.09  5114.6  578.35
  5138.6  578.46  5240.6  576.06  5469.4  580.63  5945.3  575.75  6074.9  578.09
    6111   581.6  6136.7  585.57  6176.3  597.09  6447.6  606.06    6580  623.89
#Mann= 5 ,-1 , 0
  4585.5     .09       0  4944.7     .04       0  5055.4     .09       0
  5138.6    .035       0    6111     .09       0
Bank Sta=4944.7,5055.4
Exp/Cntr=0.3,0.1

Type RM Length L Ch R = 1 ,295674  ,1247,1247,1247
BEGIN DESCRIPTION:
Dan River 14.0
END DESCRIPTION:
XS GIS Cut Line= 3
      1697458.94       946626.47      1697380.67       946284.54
      1697030.51       944793.26
#Sta/Elev= 30
  4642.7  607.81  4734.4   606.4  4767.3  601.85  4868.1  580.92  4919.3  575.47
    4937  569.41  4942.1  565.75  4944.7  559.35  4946.7  551.35  5053.4  551.35
  5055.4  559.35  5057.5  559.35  5061.2  564.56  5064.1  565.78  5090.6  575.08
  5101.7   576.9  5121.3  578.42  5149.8  575.32  5202.1   573.8  5248.7  572.94
  5340.3  576.15  5597.4  578.21  5868.2  574.64  5998.6  576.42    6400  575.21
  6438.1  576.75    6456  580.68  6476.1  586.63  6512.7  605.34  6525.3  610.43
#Mann= 5 ,-1 , 0
  4642.7     .09       0  4944.7     .04       0  5055.4     .09       0
  5202.1    .035       0    6400     .09       0
Bank Sta=4944.7,5055.4
Exp/Cntr=0.3,0.1