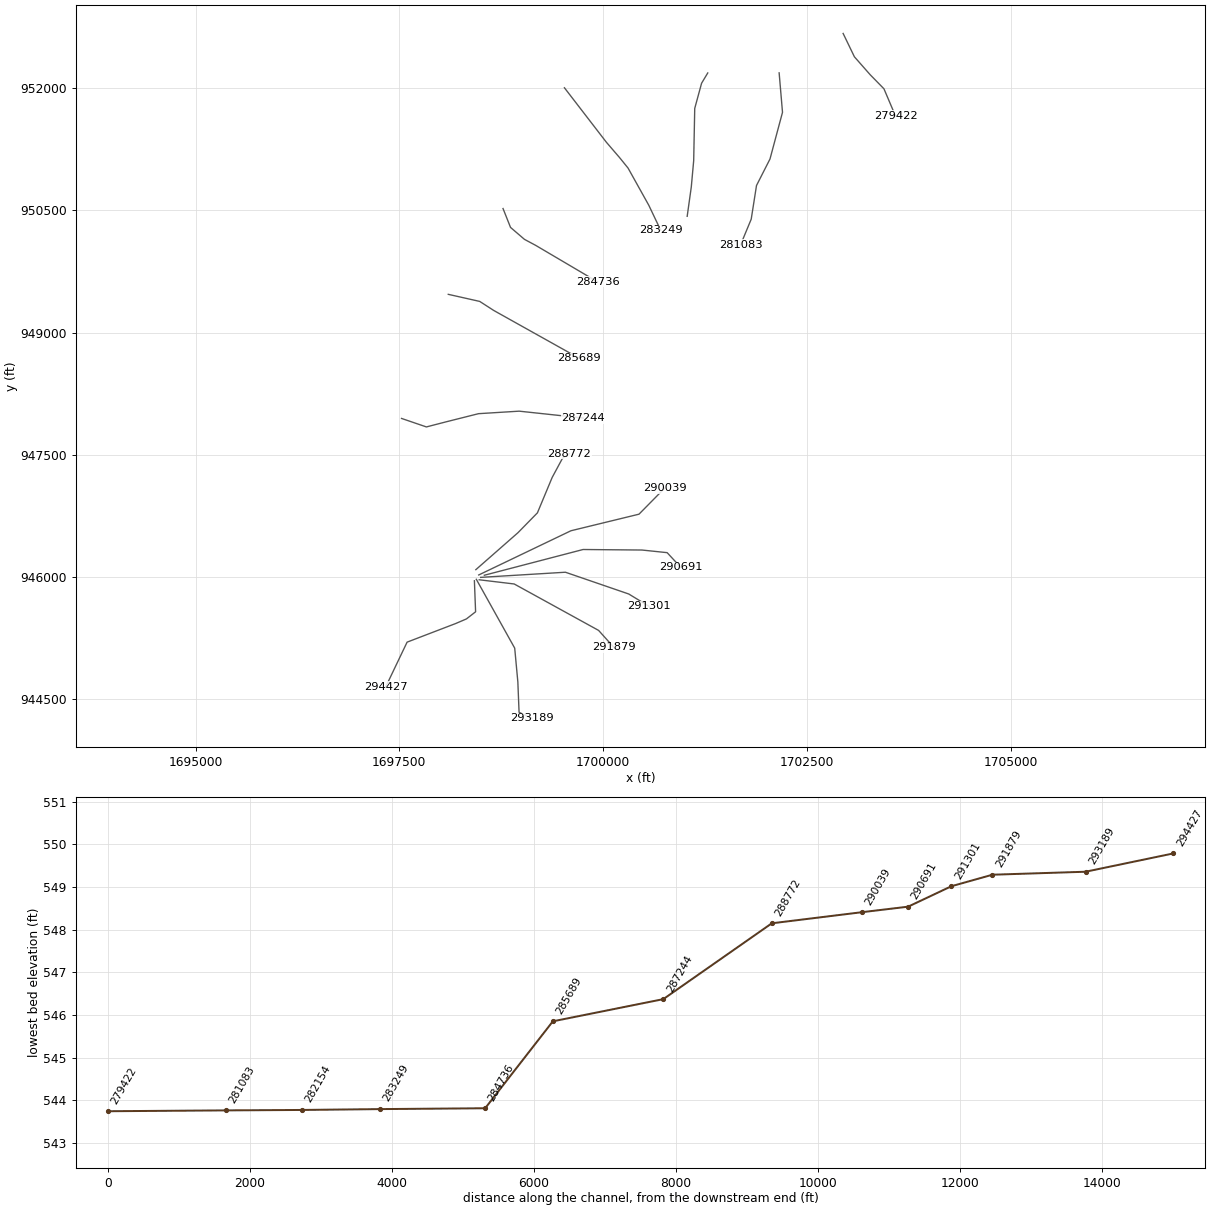
HEC-RAS study lds_dan_rvr_bctfud_lower.prj: Dan River Limited Detail Study Lower

--- lds_dan_rvr_bctfud_lower.g02 (geometry) --- (continued)

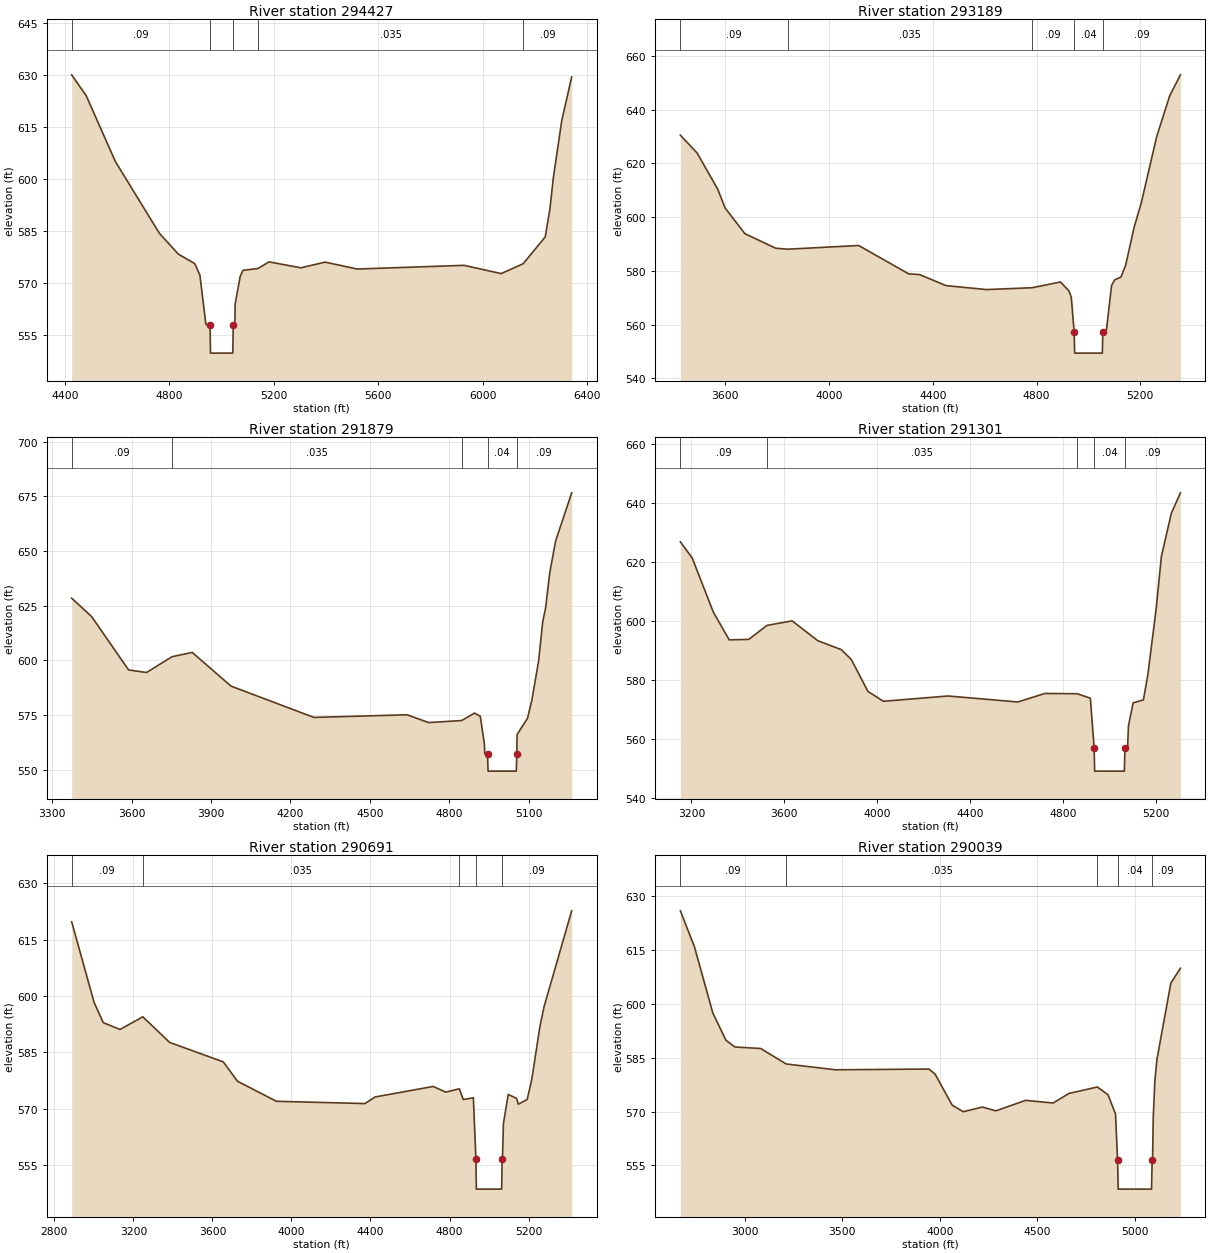
Type RM Length L Ch R = 1 ,294427  ,1238,1238,1238
BEGIN DESCRIPTION:
Dan River 13.0
END DESCRIPTION:
XS GIS Cut Line= 6
      1698420.82       945954.82      1698435.63       945573.84
       1698322.9       945486.26      1698193.71       945430.89
      1697595.22       945201.51      1697332.89       944652.79
#Sta/Elev= 30
    4426  629.94  4481.9   623.9    4593  605.01  4761.7   584.3  4834.6  578.28
  4897.3  575.57  4916.8  572.25  4939.7  558.07  4955.7  557.79  4957.3  549.79
  5042.7  549.79  5044.3  557.79  5050.1  557.79    5051  559.78  5051.7  563.94
  5071.1  571.93  5082.1  573.64  5138.7  574.16  5181.6  576.07  5303.3  574.36
  5396.1     576  5519.1  574.01  5927.9  575.07    6070   572.7  6154.1  575.54
  6238.4  583.25  6256.6  591.43  6269.3  600.21  6301.9  616.84  6339.7   629.3
#Mann= 5 ,-1 , 0
    4426     .09       0  4955.7     .04       0  5044.3     .09       0
  5138.7    .035       0  6154.1     .09       0
Bank Sta=4955.7,5044.3
Exp/Cntr=0.3,0.1

Type RM Length L Ch R = 1 ,293189  ,1310,1310,1310
BEGIN DESCRIPTION:
Dan River 12.5
END DESCRIPTION:
XS GIS Cut Line= 5
      1698444.45       945972.53      1698915.41       945127.84
      1698953.93       944713.33      1698968.96        944340.3
      1699124.18        944267.7
#Sta/Elev= 30
  3426.4  630.47  3490.8  623.86  3570.2  610.41    3599  603.35  3675.1  593.83
  3793.6  588.42  3840.7  588.05  4113.8  589.42  4306.5  578.87    4349  578.59
  4450.4   574.5  4606.6  573.02  4782.5   573.7  4891.9  575.84  4924.7  572.52
  4933.7  570.18  4944.7  557.36  4946.7  549.36  5053.4  549.36  5055.4  557.36
  5069.6  558.26  5089.2  574.61  5101.9   576.7  5125.2  577.66  5143.6  582.19
  5175.9  596.15  5203.3  605.15    5263  629.95  5313.3  645.17  5354.5  652.95
#Mann= 5 ,-1 , 0
  3426.4     .09       0  3840.7    .035       0  4782.5     .09       0
  4944.7     .04       0  5055.4     .09       0
Bank Sta=4944.7,5055.4
Exp/Cntr=0.3,0.1

Type RM Length L Ch R = 1 ,291879  ,578,578,578
BEGIN DESCRIPTION:
Dan River 12.0
END DESCRIPTION:
XS GIS Cut Line= 4
      1698479.89       945966.63      1698909.19       945915.09
      1699944.58       945345.52      1700128.78       945140.95
#Sta/Elev= 30
  3373.4  628.47  3449.1  619.98  3588.5   595.6  3656.4  594.42  3752.4  601.65
  3828.8  603.62  3975.7  588.19  4288.8  573.87  4640.9  575.08  4722.3  571.51
  4847.2  572.45  4895.5  575.86  4917.3   574.4  4932.8  561.76  4934.5   557.3
  4944.7  557.29  4946.7  549.29  5053.4  549.29  5055.4  557.29  5055.5  557.29
  5055.6  561.53  5056.5  566.05  5095.8  573.48  5112.5  581.92  5138.1  599.97
  5153.2  617.64    5164  623.86  5179.8     640  5201.9  654.61  5262.7  676.66
#Mann= 5 ,-1 , 0
  3373.4     .09       0  3752.4    .035       0  4847.2     .09       0
  4944.7     .04       0  5055.4     .09       0
Bank Sta=4944.7,5055.4
Exp/Cntr=0.3,0.1

Type RM Length L Ch R = 1 ,291301  ,610,610,610
BEGIN DESCRIPTION:
Dan River 11.0
END DESCRIPTION:
XS GIS Cut Line= 4
      1698497.61       945996.16      1699537.43       946059.21
      1700314.57       945792.12      1700561.88       945641.79
#Sta/Elev= 30
  3152.3   626.7    3203  621.29  3294.1  602.91  3362.6   593.5  3446.6  593.66
  3525.3  598.41  3633.5  599.94  3743.7  593.23  3845.3  590.19  3888.1  586.85
    3960  576.02  4026.4  572.69  4304.7  574.48  4605.2  572.45  4721.7  575.34
  4861.2  575.24  4917.5  573.73  4933.6  557.02    4936  549.02    5064  549.02
  5066.4  557.02  5077.8  557.02  5081.5  564.34  5101.6  572.15  5145.8  573.17
  5164.8  581.57  5200.6  603.91  5223.3  621.78  5266.1  636.38  5305.2  643.33
#Mann= 5 ,-1 , 0
  3152.3     .09       0  3525.3    .035       0  4861.2     .09       0
  4933.6     .04       0  5066.4     .09       0
Bank Sta=4933.6,5066.4
Exp/Cntr=0.3,0.1

Type RM Length L Ch R = 1 ,290691  ,652,652,652
BEGIN DESCRIPTION:
Dan River 10.7
END DESCRIPTION:
XS GIS Cut Line= 5
      1698542.81       946022.29      1699754.41       946338.08
      1700476.22       946331.63      1700785.56       946299.41
      1700953.12       946118.96
#Sta/Elev= 30
  2887.4  619.73    3001  598.24  3047.4  592.86  3132.4  591.05  3247.7  594.42
  3383.5   587.6    3655  582.42  3726.7  577.27  3923.6  571.93    4372  571.32
  4423.1  573.07  4717.5  575.88  4780.6  574.37  4849.7  575.26  4869.7   572.4
  4920.9  572.85  4933.6  556.54    4936  548.54    5064  548.54  5066.4  556.54
  5068.2  556.54  5072.9  565.96  5097.2  573.75  5139.7  572.71  5148.2  571.15
  5193.1   572.4  5216.3  577.67  5257.6   591.8  5278.6   597.1  5418.5  622.64
#Mann= 5 ,-1 , 0
  2887.4     .09       0  3247.7    .035       0  4849.7     .09       0
  4933.6     .04       0  5066.4     .09       0
Bank Sta=4933.6,5066.4
Exp/Cntr=0.3,0.1

Type RM Length L Ch R = 1 ,290039  ,1267,1267,1267
BEGIN DESCRIPTION:
Dan River 10.5
END DESCRIPTION:
XS GIS Cut Line= 4
      1698473.98       946025.69      1699605.48       946568.13
      1700440.16       946771.39      1700755.87       947091.43
#Sta/Elev= 30
  2670.1  625.84  2742.3   615.8  2836.6  597.39  2903.4  589.85  2949.5  587.96
    3082  587.53  3212.3  583.23  3466.2  581.61  3943.8  581.82  3975.5  580.45
  4063.3  571.79  4120.2  569.95    4218  571.24  4287.3  570.19  4439.5   573.1
    4581  572.37  4662.1  575.03  4807.8  576.83  4862.5  574.66  4900.8  569.29
  4911.4  556.41  4914.6  548.41  5085.4  548.41  5088.6  556.41  5090.8  556.41
  5094.1  568.06  5102.4  578.53  5113.1  584.47  5184.4  605.72  5233.5  609.87
#Mann= 5 ,-1 , 0
  2670.1     .09       0  3212.3    .035       0  4807.8     .09       0
  4911.4     .04       0  5088.6     .09       0
Bank Sta=4911.4,5088.6
Exp/Cntr=0.3,0.1

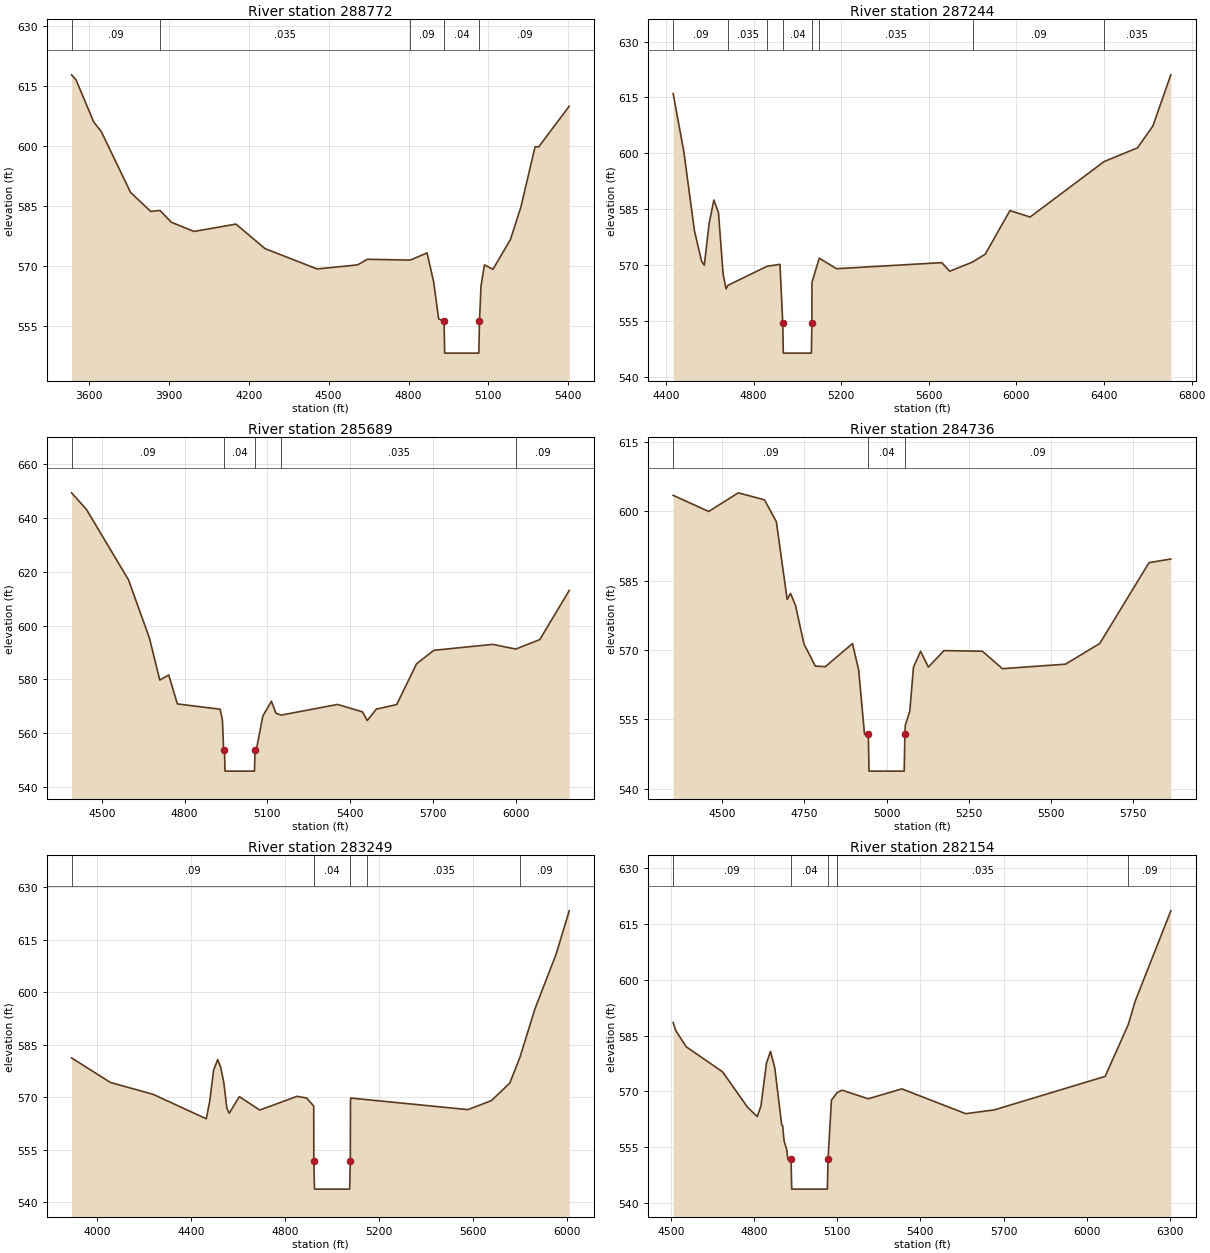
Type RM Length L Ch R = 1 ,288772  ,1528,1528,1528
BEGIN DESCRIPTION:
Dan River 10.0
END DESCRIPTION:
XS GIS Cut Line= 6
      1698438.54       946090.66      1698955.79       946544.51
      1699194.14       946787.94      1699374.82       947221.57
      1699501.29       947456.45      1699587.36       947513.89
#Sta/Elev= 30
  3534.7  617.76  3551.4  616.52  3618.2  605.93  3646.1   603.6  3756.4  588.35
  3832.1  583.59  3866.9  583.84  3909.8  580.87  3994.9  578.59  4152.2  580.42
  4261.3  574.29    4457   569.2  4608.5  570.22  4645.4  571.62  4806.5  571.42
  4869.7  573.22  4894.5  565.96  4913.2  556.72  4933.5  556.15  4935.9  548.15
  5064.1  548.15  5066.5  556.15  5072.2  564.84  5085.1  570.22  5117.2  569.12
  5183.1   576.6  5221.8  584.65  5275.3  599.75  5289.1  599.76  5403.5  609.91
#Mann= 5 ,-1 , 0
  3534.7     .09       0  3866.9    .035       0  4806.5     .09       0
  4933.5     .04       0  5066.5     .09       0
Bank Sta=4933.5,5066.5
Exp/Cntr=0.3,0.1

Type RM Length L Ch R = 1 ,287244  ,1555,1555,1555
BEGIN DESCRIPTION:
Dan River 9.0
END DESCRIPTION:
XS GIS Cut Line= 6
      1697527.09       947946.08      1697831.98        947841.9
       1698078.5       947905.58      1698471.43        948004.5
      1698970.48       948035.31      1699755.69        947951.2
#Sta/Elev= 30
  4433.2  616.02  4481.8  600.51  4530.3  579.23  4562.9  571.03  4575.4  569.98
  4597.3  581.15    4619  587.47  4640.1  584.06  4661.1  567.65  4674.6  563.62
  4683.8  564.58    4862  569.69  4920.8   570.2  4933.5  554.37  4935.9  546.37
  5064.1  546.37  5066.5  554.37  5066.8  565.36    5100  571.86    5179  569.03
  5659.3  570.66  5695.8  568.35    5800  570.82  5857.6  572.92  5970.5  584.63
  6062.6  582.91    6400  597.78  6552.6  601.47  6622.9  607.32  6704.9  621.07
#Mann= 8 ,-1 , 0
  4433.2     .09       0  4683.8    .035       0    4862     .09       0
  4933.5     .04       0  5066.5     .09       0    5100    .035       0
    5800     .09       0    6400    .035       0
#XS Ineff= 2 , 0
       0    4619                       0
Permanent Ineff=
       F       F
Bank Sta=4933.5,5066.5
Exp/Cntr=0.3,0.1

Type RM Length L Ch R = 1 ,285689  ,953,953,953
BEGIN DESCRIPTION:
Dan River 8.0
END DESCRIPTION:
XS GIS Cut Line= 4
      1698100.44       949468.59      1698485.89       949381.87
      1698658.41       949270.69      1699708.43        948683.6
#Sta/Elev= 30
  4390.5  649.36  4444.5  643.19  4596.9  616.99  4672.7  595.35  4710.2  579.73
  4742.8  581.62  4773.9  570.85  4928.8  568.87  4937.2  564.84  4941.5  553.86
  4944.6  553.85  4946.6  545.85  5053.4  545.85  5055.4  553.85  5060.3  553.85
  5083.5  566.32  5114.7  571.84  5131.3  567.38    5150  566.69  5354.5  570.65
  5444.7  567.89    5462  564.67  5494.9  568.91  5568.7  570.61  5640.8  585.79
  5703.3  590.78  5916.7     593    6000  591.25  6087.1  594.77  6193.8  613.05
#Mann= 5 ,-1 , 0
  4390.5     .09       0  4944.6     .04       0  5055.4     .09       0
    5150    .035       0    6000     .09       0
Bank Sta=4944.6,5055.4
Exp/Cntr=0.3,0.1

Type RM Length L Ch R = 1 ,284736  ,1487,1487,1487
BEGIN DESCRIPTION:
Dan River 7.0
END DESCRIPTION:
XS GIS Cut Line= 5
      1698772.19        950521.2      1698863.99       950289.87
      1699035.15       950143.12      1699172.43       950069.55
      1699932.52       949621.58
#Sta/Elev= 30
  4351.4  603.46  4459.4  599.97  4549.4     604  4628.9  602.48    4665  597.75
  4697.8  580.93  4707.9  582.25    4723   579.7  4748.8  571.32  4783.5  566.52
  4813.8   566.4  4896.3   571.4  4915.1   565.7  4932.9  551.81  4944.5  551.81
  4946.5  543.81  5053.5  543.81  5055.5  551.81  5056.7  553.68  5070.5  556.76
  5081.6  566.28  5103.3  569.73  5126.8  566.32  5174.5  569.88    5291  569.74
  5352.1  565.97  5543.5  566.94  5647.8  571.42  5797.4  588.89  5863.7  589.69
#Mann= 3 ,-1 , 0
  4351.4     .09       0  4944.5     .04       0  5055.5     .09       0
Bank Sta=4944.5,5055.5
Exp/Cntr=0.3,0.1

Type RM Length L Ch R = 1 ,283249  ,1095,1095,1095
BEGIN DESCRIPTION:
Dan River 6.0
END DESCRIPTION:
XS GIS Cut Line= 6
      1699525.33       952003.04       1700039.2       951335.61
      1700204.48        951143.3      1700306.15        951017.6
      1700560.42       950561.59      1700706.63       950254.72
#Sta/Elev= 30
  3890.4  581.24  4056.1  574.22  4237.4  570.85  4464.3  563.86  4479.6  569.17
  4495.3  577.73  4512.9  580.73  4525.9   578.5  4539.2  574.05  4551.8  566.89
  4561.9  565.44  4605.1  570.18  4691.9  566.35  4850.8  570.27  4891.7  569.78
  4921.8   567.5  4922.3  551.79  4925.1  543.79  5074.9  543.79  5077.7  551.79
  5078.4   569.1  5079.8  569.78    5150  569.31  5578.7  566.48  5678.6  569.05
  5756.8  574.04    5800  581.38  5864.5  595.29  5954.1  610.82    6010   623.2
#Mann= 5 ,-1 , 0
  3890.4     .09       0  4922.3     .04       0  5077.7     .09       0
    5150    .035       0    5800     .09       0
#XS Ineff= 2 , 0
       0  4510.2                       0
Permanent Ineff=
       F       F
Bank Sta=4922.3,5077.7
Exp/Cntr=0.3,0.1

Type RM Length L Ch R = 1 ,282154  ,1071,1071,1071
BEGIN DESCRIPTION:
Dan River 5.0
END DESCRIPTION:
XS GIS Cut Line= 6
      1701283.79       952184.58      1701208.09        952058.3
      1701124.13       951749.74      1701111.21        951108.7
      1701081.83       950785.58      1701031.48       950426.01
#Sta/Elev= 30
  4507.9   588.5  4517.3  586.37  4555.1  582.01  4686.3  575.27  4776.7  565.73
  4811.3  563.25  4824.6   566.1  4844.4  577.56  4859.1  580.78  4874.6  576.33
  4899.5  561.06    4903  560.79    4908  556.76  4917.7  554.39  4921.7  551.77
  4933.3  551.77  4935.7  543.77  5064.3  543.77  5066.7  551.77    5079  567.68
    5100  569.73  5117.4  570.35  5211.7  568.04    5333   570.7  5563.4  564.04
    5667  565.06  6066.7  574.06    6150  587.97  6175.2   594.3  6303.6  618.53
#Mann= 5 ,-1 , 0
  4507.9     .09       0  4933.3     .04       0  5066.7     .09       0
    5100    .035       0    6150     .09       0
#XS Ineff= 2 , 0
       0  4859.1                       0
Permanent Ineff=
       F       F
Bank Sta=4933.3,5066.7
Exp/Cntr=0.3,0.1

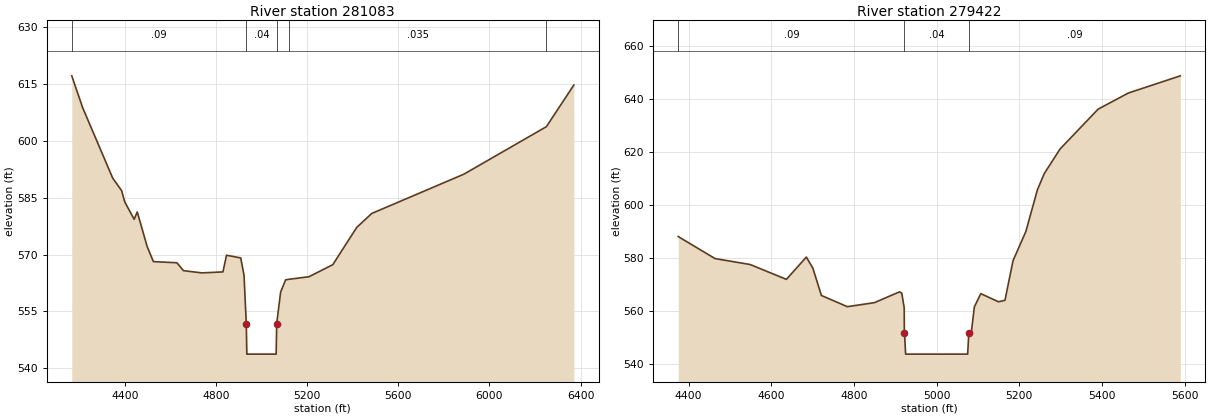
Type RM Length L Ch R = 1 ,281083  ,1661,1661,1661
BEGIN DESCRIPTION:
Dan River 4.0
END DESCRIPTION:
XS GIS Cut Line= 6
      1702159.62       952186.14      1702200.96       951701.81
       1702047.4       951128.88      1701882.02       950804.03
      1701817.04       950390.57       1701687.1       950077.53
#Sta/Elev= 30
  4167.6  617.07  4215.4  608.68  4347.4   590.1  4386.4  586.82  4399.9  583.87
  4441.3  579.28  4454.9  581.21  4498.7  572.05  4525.7  568.13  4628.9  567.83
  4657.7  565.75  4738.2  565.16  4830.8  565.42  4846.6  569.82  4908.8   569.1
  4923.3  564.57  4933.3  551.76  4935.7  543.76  5064.3  543.76  5066.7  551.76
  5083.9  560.11    5106  563.34    5120  563.47  5208.4  564.15  5312.9  567.33
    5418  577.15  5483.9  580.82  5887.6  591.15    6250  603.68  6370.4  614.64
#Mann= 5 ,-1 , 0
  4167.6     .09       0  4933.3     .04       0  5066.7     .09       0
    5120    .035       0    6250     .09       0
Bank Sta=4933.3,5066.7
Exp/Cntr=0.3,0.1

Type RM Length L Ch R = 1 ,279422  ,1070,1070,1070
BEGIN DESCRIPTION:
Dan River 3.0
END DESCRIPTION:
XS GIS Cut Line= 5
      1702944.77       952669.29      1703083.03       952382.86
      1703276.64       952162.91      1703445.56       951990.17
      1703587.12       951657.02
#Sta/Elev= 30
  4374.8  588.06  4463.8  579.76  4548.8  577.52  4636.5  571.92  4684.7  580.33
  4700.5  576.16  4721.2  565.85  4783.9  561.63  4849.4  563.14  4910.2  567.22
  4915.6  566.73  4921.5  561.22  4921.9  551.74  4922.2  551.74    4925  543.74
    5075  543.74  5077.8  551.74  5083.8  551.74  5091.2  561.53  5106.8  566.54
  5149.8  563.46  5165.3  564.04  5184.8  578.96  5215.8  589.95  5243.8  605.71
  5260.4  611.82  5298.7  621.09  5390.6  636.08  5463.7  642.16  5589.5  648.65
#Mann= 3 ,-1 , 0
  4374.8     .09       0  4922.2     .04       0  5077.8     .09       0
#XS Ineff= 2 , 0
       0  4684.7                       0
Permanent Ineff=
       F       F
Bank Sta=4922.2,5077.8
Exp/Cntr=0.3,0.1