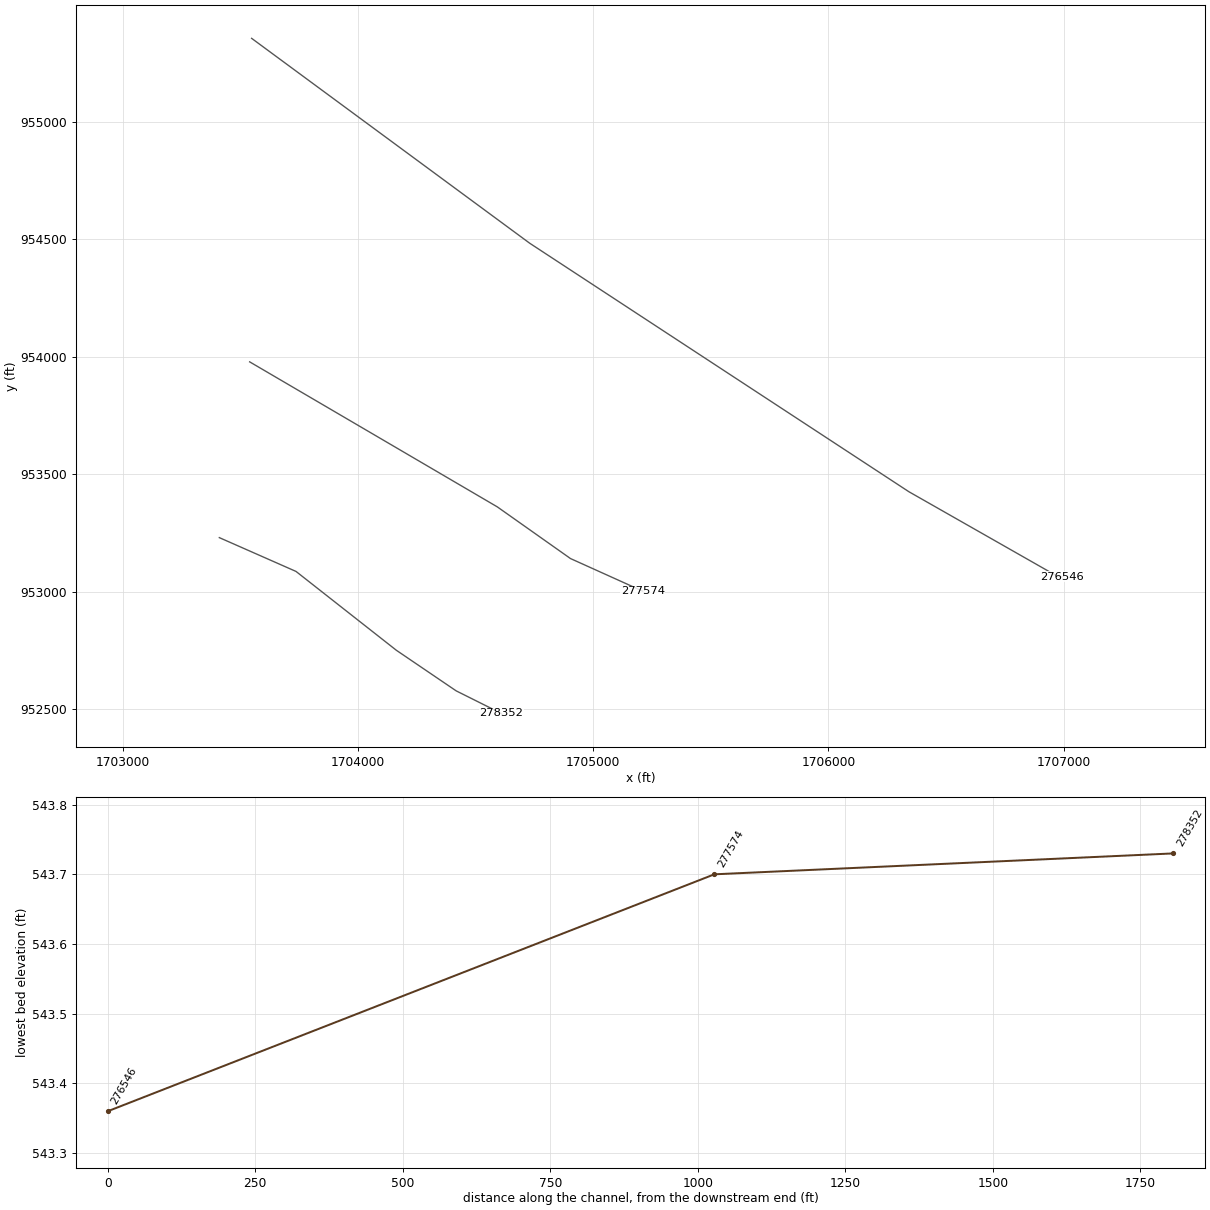
HEC-RAS study lds_dan_rvr_bctfud_lower.prj: Dan River Limited Detail Study Lower

--- lds_dan_rvr_bctfud_lower.g02 (geometry) --- (continued)

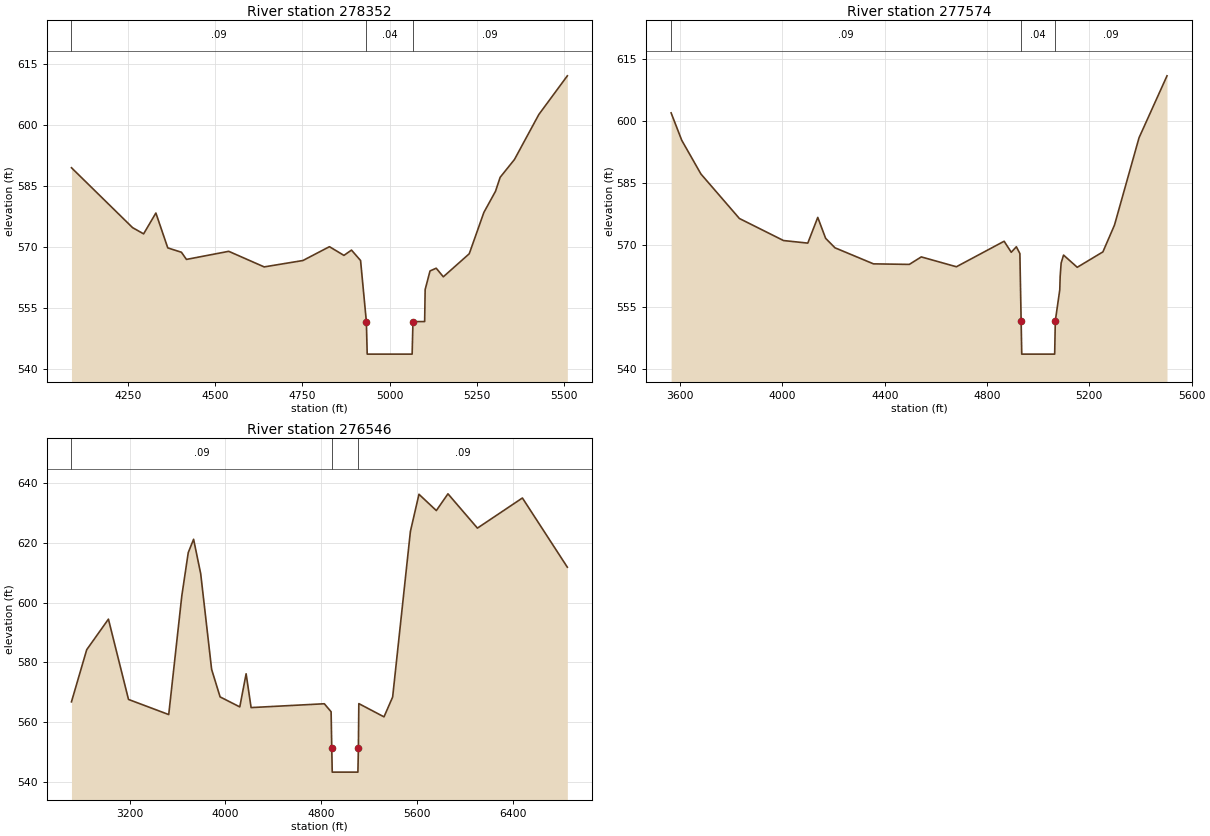
Type RM Length L Ch R = 1 ,278352  ,778,778,778
BEGIN DESCRIPTION:
Dan River 2.0
END DESCRIPTION:
XS GIS Cut Line= 5
      1703409.15       953229.45      1703735.31       953085.55
       1704162.2        952749.8      1704416.41       952577.13
      1704608.27        952481.2
#Sta/Elev= 30
  4087.9  589.53  4263.1  574.81  4294.7  573.28  4329.9   578.4    4364  569.83
  4403.1  568.76  4417.5     567  4538.7  568.99  4640.3  565.16  4751.4  566.73
  4827.4  570.13  4868.9  567.99  4890.6  569.29  4916.6  566.73  4933.2  551.73
  4935.6  543.73  5064.4  543.73  5066.8  551.73  5100.3  551.73  5101.7  559.59
  5115.7  564.17  5133.4  564.84  5153.8  562.73  5228.1  568.39    5270  578.54
  5303.3  583.73  5316.8  587.19  5357.6  591.54  5427.6  602.61  5509.3  612.11
#Mann= 3 ,-1 , 0
  4087.9     .09       0  4933.2     .04       0  5066.8     .09       0
#XS Ineff= 2 , 0
       0  4329.9                       0
Permanent Ineff=
       F       F
Bank Sta=4933.2,5066.8
Exp/Cntr=0.3,0.1

Type RM Length L Ch R = 1 ,277574  ,1028,1028,1028
BEGIN DESCRIPTION:
Dan River 1.0
END DESCRIPTION:
XS GIS Cut Line= 4
      1703538.16       953977.82       1704591.8       953360.18
      1704902.82       953140.33      1705209.78        953001.7
#Sta/Elev= 30
  3564.6  601.96    3606  595.36  3681.1  587.21  3831.5  576.46  4004.1  571.13
    4099  570.51    4138  576.72  4168.8  571.66  4205.3  569.38  4355.8   565.5
    4496  565.37  4542.7  567.18  4680.1   564.8  4866.7  570.96  4894.6   568.3
  4914.5  569.63  4928.3  567.99  4933.2   551.7  4935.6   543.7  5064.4   543.7
  5066.8   551.7  5084.3  559.24  5085.8  562.45  5089.7  565.71  5099.1  567.62
  5152.6  564.67  5252.9  568.39  5298.2  574.86  5394.2  595.95  5503.6  610.91
#Mann= 3 ,-1 , 0
  3564.6     .09       0  4933.2     .04       0  5066.8     .09       0
#XS Ineff= 2 , 0
       0    4138                       0
Permanent Ineff=
       F       F
Bank Sta=4933.2,5066.8
Exp/Cntr=0.3,0.1

Type RM Length L Ch R = 1 ,276546  ,0,0,0
BEGIN DESCRIPTION:
Dan River 0.0
END DESCRIPTION:
XS GIS Cut Line= 5
       1703546.5       955355.17       1704729.8       954482.49
      1706342.04       953424.92      1706978.06       953062.53
      1706992.85       953062.53
#Sta/Elev= 30
  2712.8  566.83  2840.3  584.24  3021.8  594.44  3189.7  567.63  3525.9  562.58
  3635.2  602.22  3689.1  616.67  3733.8  621.11  3793.2  609.61  3884.5  577.67
  3955.3  568.48  4119.9  565.14  4172.8   576.2  4214.5  564.91  4826.6  566.19
  4883.3  563.51  4888.7  551.36  4892.7  543.36  5107.3  543.36  5111.3  551.36
    5115  566.24  5325.5  561.82  5397.7  568.44  5546.1  623.72  5617.7  636.14
  5762.9   630.7  5860.1  636.29  6106.4  624.84  6482.4   634.9  6858.1  611.79
#Mann= 3 ,-1 , 0
  2712.8     .09       0  4888.7     .05       0  5111.3     .09       0
#XS Ineff= 2 , 0
       0    3700                       0
Permanent Ineff=
       F       F
Bank Sta=4888.7,5111.3
Exp/Cntr=0.3,0.1

Chan Stop Cuts=-1
Use User Specified Reach Order=0
User Specified Reach Order=Dan River       ,Reach-1

--- lds_dan_rvr_bctfud_lower.g01 (geometry) ---

Geom Title=Existing Conditions
Program Version=3.12

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
River Reach=Dan River       ,Reach-1

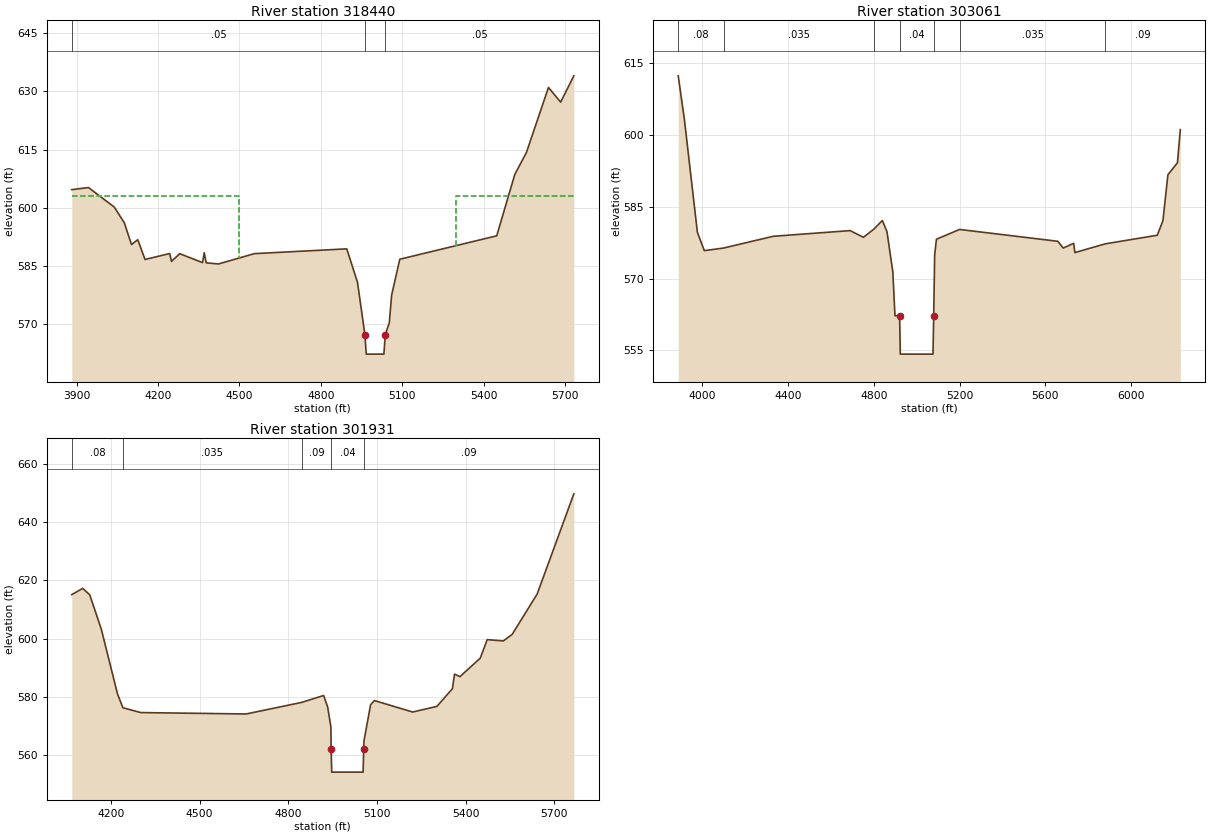
Type RM Length L Ch R = 1 ,318440  ,905,905,905
BEGIN DESCRIPTION:
Railroad - US
END DESCRIPTION:
XS GIS Cut Line= 6
        1684706.       934319.07      1684332.41       934016.25
      1684253.54       933890.99      1684156.12       933696.15
      1684026.22       932990.99      1683831.38       932786.87
#Sta/Elev= 30
  3882.1   604.7  3943.7  605.24  4038.5  600.23  4075.7  596.17  4102.1  590.56
  4125.4  591.79  4152.1   586.7    4243  588.23  4249.5   586.2    4280  588.19
  4364.1  585.89  4370.3  588.44  4377.6  585.83  4422.7  585.54  4554.8   588.2
  4895.7  589.44  4935.3  580.79  4962.5   567.3  4967.5   562.3  5032.5   562.3
  5037.5   567.3  5052.3  570.35  5061.1  577.54  5091.1  586.76  5448.4   592.8
    5515  608.62  5557.8  614.27  5639.1  631.04    5684  627.25  5732.6  634.04
#Mann= 3 ,-1 , 0
  3882.1     .05       0  4962.5     .05       0  5037.5     .05       0
#XS Ineff= 2 , 0
       0    4500     603    5300       0     603
Permanent Ineff=
       F       F
Bank Sta=4962.5,5037.5
Exp/Cntr=0.5,0.3

Type RM Length L Ch R = 1 ,303061  ,1130,1130,1130
BEGIN DESCRIPTION:
Dan River 20.0
END DESCRIPTION:
XS GIS Cut Line= 5
      1695573.95       941961.95      1695684.25       941878.34
      1696285.99       941127.14      1696676.71       940510.49
      1696826.08       940023.17
#Sta/Elev= 30
  3888.5   612.3  3917.8  602.99  3977.8  579.63  4010.1  575.82    4100  576.36
  4331.1  578.81  4689.7     580    4752   578.6    4800  580.29  4840.1  582.11
  4861.6  579.78  4888.9  571.39  4898.9  562.22  4920.6  562.22  4923.8  554.22
  5076.2  554.22  5079.4  562.22    5084  574.96  5092.2   578.2    5200  580.24
  5657.9  577.77  5683.2  576.36  5731.9  577.34  5737.6  575.41  5879.9  577.24
  6121.8  579.03    6148  582.07  6171.3  591.66  6215.7  594.15  6229.1  601.07
#Mann= 7 ,-1 , 0
  3888.5     .08       0    4100    .035       0    4800     .09       0
  4920.6     .04       0  5079.4     .09       0    5200    .035       0
  5879.9     .09       0
Bank Sta=4920.6,5079.4
Exp/Cntr=0.3,0.1

Type RM Length L Ch R = 1 ,301931  ,1074,1074,1074
BEGIN DESCRIPTION:
Dan River 19.0
END DESCRIPTION:
XS GIS Cut Line= 4
      1695782.19       942285.32      1695971.51       942214.33
      1696685.83       942140.08      1697463.98       942145.14
#Sta/Elev= 30
  4067.5  615.12  4104.6  617.26  4128.3  615.06  4167.6  603.21  4222.3     581
  4240.5   576.3  4300.9  574.64  4657.4  574.16  4845.1  578.13  4919.7   580.5
  4933.2  576.54  4944.1  569.76  4944.9   562.2  4946.9   554.2  5053.1   554.2
  5055.1   562.2    5056   564.9  5078.4  577.33  5091.4  578.76  5220.7  574.83
  5302.8  576.76  5355.3  582.85  5362.3  587.85  5380.6  586.97  5449.2  593.29
    5473  599.68  5527.5  599.23  5557.4  601.49  5641.8   615.3    5766  649.72
#Mann= 5 ,-1 , 0
  4067.5     .08       0  4240.5    .035       0  4845.1     .09       0
  4944.9     .04       0  5055.1     .09       0
Bank Sta=4944.9,5055.1
Exp/Cntr=0.3,0.1