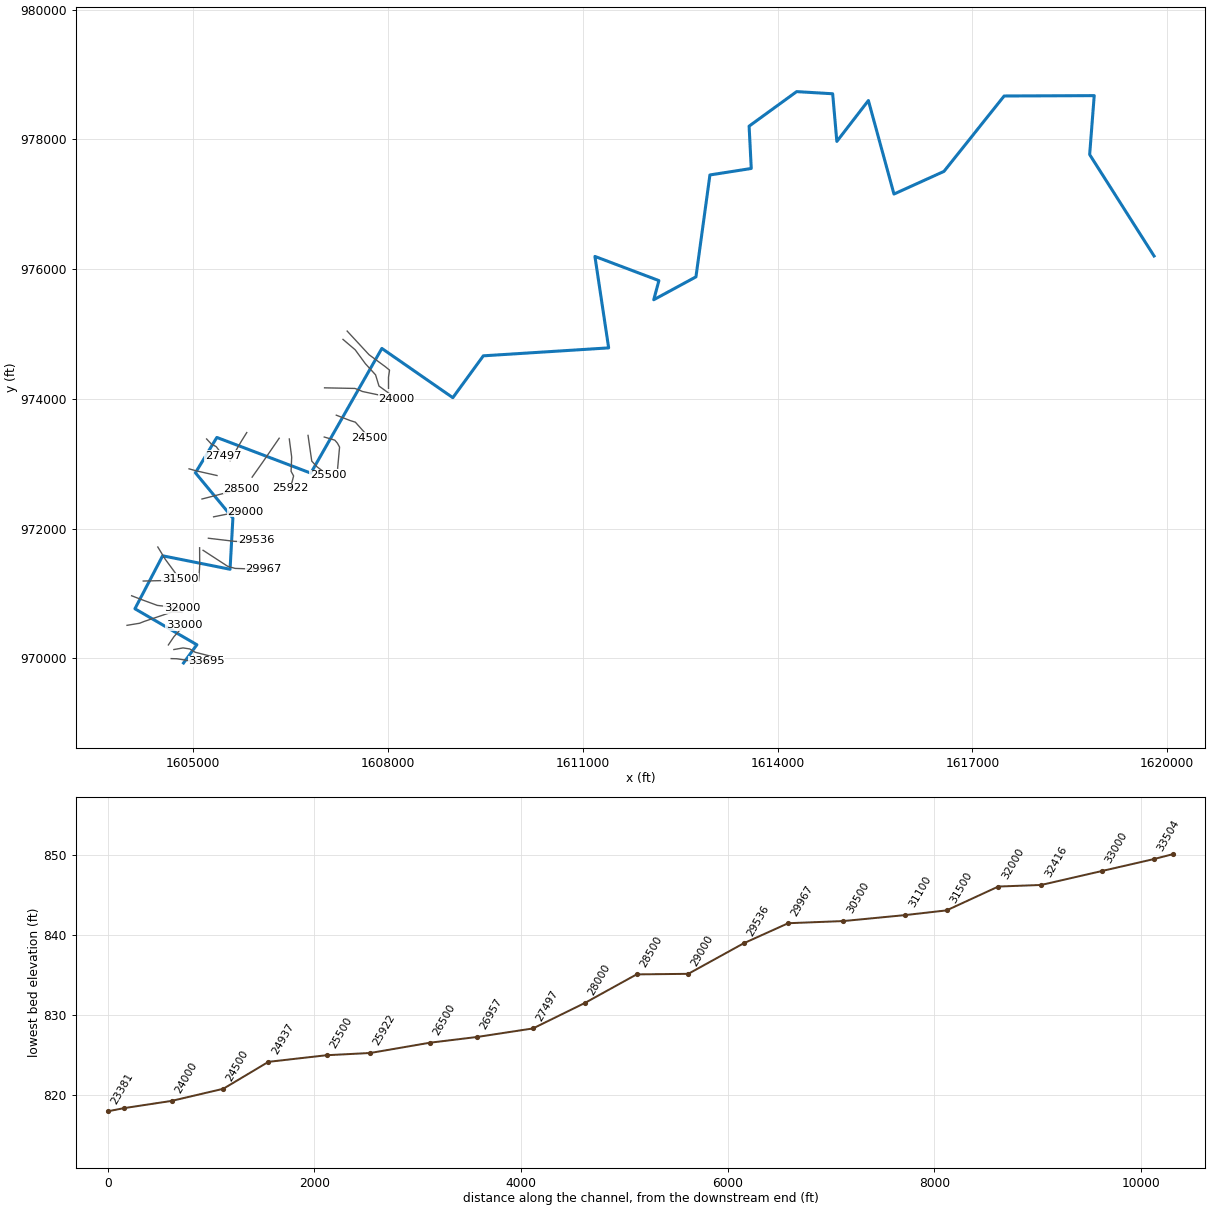
--- lds_south_double_crk.prj (project) ---

Proj Title=South Double Creek Limited Detail Study
Current Plan=p01
Default Exp/Contr=0.3,0.1
English Units
Geom File=g01
Flow File=f01
Plan File=p01
Y Axis Title=Elevation
X Axis Title(PF)=Main Channel Distance
X Axis Title(XS)=Station
BEGIN DESCRIPTION:
South Double Creek
END DESCRIPTION:
DSS Export Rating Curves= 0
DSS Export Rating Curve Sorted= 0
DSS Export Volume Flow Curves= 0
DXF OffsetX= 0
DXF OffsetY= 0
DXF ScaleX= 1
DXF ScaleY= 10

--- lds_south_double_crk.p01 (plan) ---

Plan Title=Floodway Run
Program Version=3.12
Short Identifier=Floodway
Geom File=g01
Flow File=f01
Subcritical Flow
K Sum by GR= 0
Std Step Tol= 0.01
Critical Tol= 0.01
Num of Std Step Trials= 20
Max Error Tol= 0.3
Flow Tol Ratio= 0.001
Split Flow NTrial= 30
Split Flow Tol= 0.02
Split Flow Ratio= 0.02
Log Output Level= 0
Friction Slope Method= 1
Unsteady Friction Slope Method= 2
Unsteady Bridges Friction Slope Method= 1
Parabolic Critical Depth
Global Vel Dist= 0 , 0 , 0
Global Log Level= 0
CheckData=True
Encroach Param=-1 ,5,5, 2
Encroach River=South Double Cre
Encroach Reach=Reach-1
Encroach Node=33695
       4      .7
Encroach Node=33504
       4      .7
Encroach Node=33000
       4      .7
Encroach Node=32416
       4      .7
Encroach Node=32000
       1  4991.2  5108.6
Encroach Node=31500
       4      .7
Encroach Node=31100
       4      .7
Encroach Node=30500
       4      .7
Encroach Node=29967
       4      .7
Encroach Node=29536
       4      .7
Encroach Node=29000
       4      .7
Encroach Node=28500
       4      .7
Encroach Node=28000
       1  4986.6  5052.1
Encroach Node=27497
       4      .7
Encroach Node=26957
       4      .7
Encroach Node=26500
       4      .7
Encroach Node=25922
       4      .7
Encroach Node=25500
       4      .7
Encroach Node=24937
       4      .7
Encroach Node=24500
       4      .7
Encroach Node=24000
       4      .7
Encroach Node=23538
       1    4915    5080
Encroach Node=23381
       1    4920    5075
Encroach Node=22862
       4       1
Encroach Node=22482
       4      .9
Encroach Node=22000
       4      .7
Encroach Node=21500
       4      .7
Encroach Node=20916
       4      .7
Encroach Node=20291
       4      .7
Encroach Node=19503
       4      .7
Encroach Node=19003
       4      .7
Encroach Node=18329
       4      .7
Encroach Node=17949
       4      .7
Encroach Node=17434
       4      .7
Encroach Node=17000
       4      .7
Encroach Node=16500
       4      .7
Encroach Node=15677
       4      .7
Encroach Node=15036
       4      .7
Encroach Node=14500
       4      .7
Encroach Node=14058
       4      .7
Encroach Node=13817
       1    4922  5076.4
Encroach Node=13706
       1  4922.1  5075.2
Encroach Node=13290
       4      .7
Encroach Node=12803
       4      .7
Encroach Node=12602
       4      .7
Encroach Node=12398
       4      .7
Encroach Node=12007
       4      .7
Encroach Node=11500
       4      .7
Encroach Node=10980
       4      .7
Encroach Node=10492
       4      .7
Encroach Node=10021
       4      .7
Encroach Node=9635
       4      .7
Encroach Node=9356
       4      .7
Encroach Node=8889
       4      .7
Encroach Node=8653
       4      .7
Encroach Node=8554
       4      .7
Encroach Node=8068
       4      .7
Encroach Node=7506
       4      .7
Encroach Node=6952
       4      .7
Encroach Node=6454
       4      .7
Encroach Node=5943
       4      .7
Encroach Node=5501
       4      .7
Encroach Node=5016
       4      .7
Encroach Node=4440
       4      .7
Encroach Node=3932
       1  4944.4  5054.5
Encroach Node=3793
       1    4900    5100
Encroach Node=3385
       4      .1
Encroach Node=3000
       1    4983    5110
Encroach Node=2089
       4      .7
Encroach Node=1344
       1  4941.9  5029.8
Encroach Node=1163
       1    4955    5045
Encroach Node=636
       4      .7
BEGIN DESCRIPTION:
Floodway Run
END DESCRIPTION:
Computation Interval=1HOUR
Output Interval=1HOUR
Run HTab= 0
Run UNet= 0
Run PostProcess= 0
UNET Theta= 1
UNET Theta Warmup= 1
UNET ZTol= 0.02
UNET ZSATol= 0.05
UNET MxIter= 20
UNET MaxInSteps= 0
UNET DtIC= 0
UNET DtMin= 0
UNET MaxCRTS= 20
UNET WFStab= 2
UNET SFStab= 1
UNET WFX= 1
UNET SFX= 1
UNET DSS MLevel= 4
UNET DZMax Abort= 100
UNET Convert EG Bridges=-1
UNET Use Existing IB Tables=-1
UNET Froude Reduction=False
UNET Froude Limit= 1
UNET Froude Power= 10
Instantaneous Interval=1HOUR
Write IC File= 0
Echo Input=False
Echo Output=False
Write Detailed= 0
Detailed Automatic Start=False, 10

--- lds_south_double_crk.f01 (steady flow) ---

Flow Title=Floodway
Number of Profiles=2
Profile Names=100-year,100-FW
River Rch & RM= South Double Cre,Reach-1,33695
    2486    2486
River Rch & RM= South Double Cre,Reach-1,31500
    2544    2544
River Rch & RM= South Double Cre,Reach-1,28000
    2881    2881
River Rch & RM= South Double Cre,Reach-1,22862
    3052    3052
River Rch & RM= South Double Cre,Reach-1,19003
    3126    3126
River Rch & RM= South Double Cre,Reach-1,13706
    3223    3223
River Rch & RM= South Double Cre,Reach-1,11500
    3251    3251
River Rch & RM= South Double Cre,Reach-1,6952
    4342    4342
Boundary for River Rch & Prof#=South Double Cre,Reach-1,1
Up Type=0
Dn Type=3
Dn Slope=0.004
Boundary for River Rch & Prof#=South Double Cre,Reach-1,2
Up Type=0
Dn Type=3
Dn Slope=0.004

--- lds_south_double_crk.g01 (geometry) ---

Geom Title=Existing Conditions
Program Version=3.12

River Reach=South Double Cre,Reach-1
Reach XY= 30
      1604851.13       969928.81      1605056.38       970209.88
      1604102.25        970764.5      1604528.88       971580.94
      1605567.38       971373.44        1605611.       972161.75
        1605034.       972859.88      1605363.75       973405.31
      1606810.88       972855.06      1607904.88       974777.25
      1608997.88       974018.06      1609467.88       974663.25
      1611397.75       974785.63      1611186.25       976195.22
      1612171.75       975822.63      1612091.88        975527.5
        1612742.       975880.31      1612957.25       977451.06
      1613593.88       977550.88      1613560.63       978203.19
      1614292.75       978735.63       1614847.5       978702.38
      1614911.75         977968.      1615397.63       978598.06
       1615791.5       977156.81       1616561.5       977505.88
      1617488.13       978668.19      1618875.38       978673.63
      1618805.25         977765.        1619797.       976201.81

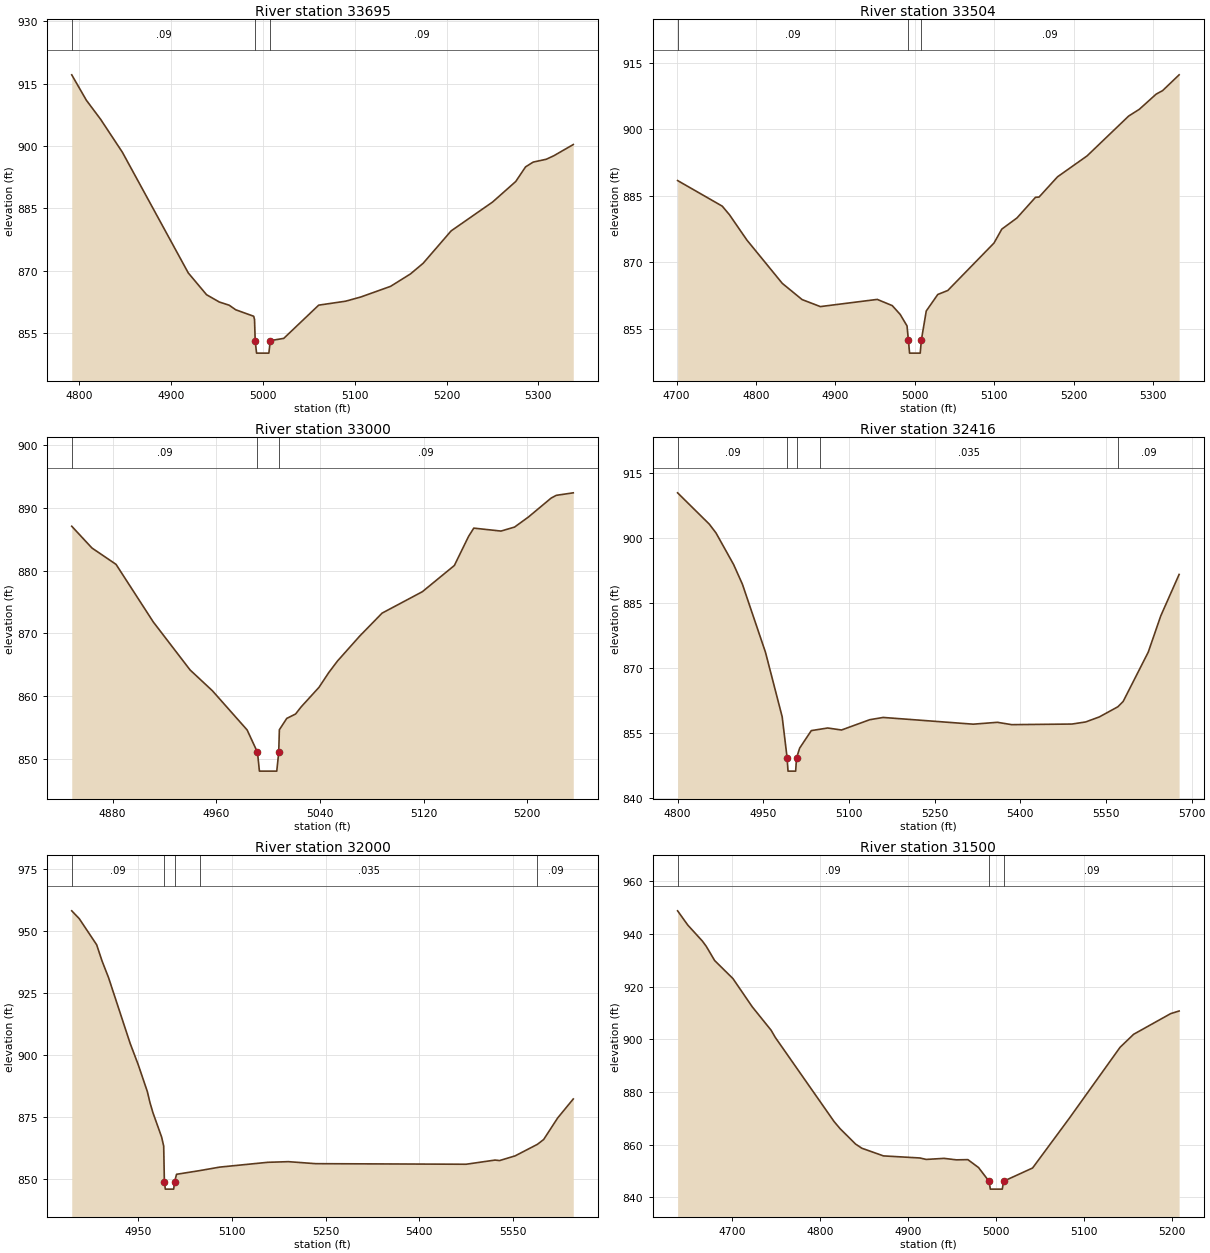
Type RM Length L Ch R = 1 ,33695   ,191,191,191
BEGIN DESCRIPTION:
South Double Creek 69.0
END DESCRIPTION:
XS GIS Cut Line= 5
      1604660.78       969996.25      1604747.82       969993.96
       1604850.9       969977.93      1604940.24       969961.89
      1605203.66       969955.02
#Sta/Elev= 30
  4792.2  917.12  4808.1  911.01  4823.6  906.43  4847.3   898.5    4919  869.47
  4938.9  864.23  4952.8  862.47  4963.5  861.71  4970.6  860.61  4990.2  859.05
  4991.1  858.25  4991.8  853.18  4993.3  850.18  5006.7  850.18  5008.2  853.18
  5022.9  853.73  5060.9  861.72  5090.2  862.67  5106.7  863.68  5139.1  866.24
  5160.7  869.22  5174.6   871.8    5205  879.58  5250.1  886.52  5275.3  891.46
    5286  894.98  5294.3  896.13  5308.5  896.81  5316.7  897.65  5337.9  900.35
#Mann= 3 ,-1 , 0
  4792.2     .09       0  4991.8     .05       0  5008.2     .09       0
Bank Sta=4991.8,5008.2
Exp/Cntr=0.3,0.1

Type RM Length L Ch R = 1 ,33504   ,504,504,504
BEGIN DESCRIPTION:
South Double Creek 68.0
END DESCRIPTION:
XS GIS Cut Line= 5
      1604702.01       970135.98      1604844.03       970161.18
      1604947.11       970145.14      1605029.57       970094.75
      1605306.74       970023.74
#Sta/Elev= 30
  4701.3  888.44  4757.5  882.67  4766.6  880.73  4788.6  875.01  4833.1  865.26
    4858  861.61    4881  860.03  4952.6  861.65  4971.5  860.25  4981.5  858.26
  4990.1  855.67  4991.8  852.54  4993.3  849.54  5006.7  849.54  5008.2  852.54
  5014.3  859.04  5028.8  862.76  5041.4  863.66  5099.6  874.36  5109.4  877.49
  5128.5  880.01  5151.8  884.66  5156.3  884.72  5179.5  889.28  5216.7  893.99
  5269.1  902.98  5282.5   904.5  5303.7  907.92  5311.8  908.71  5332.6  912.27
#Mann= 3 ,-1 , 0
  4701.3     .09       0  4991.8     .05       0  5008.2     .09       0
Bank Sta=4991.8,5008.2
Exp/Cntr=0.3,0.1

Type RM Length L Ch R = 1 ,33000   ,584,584,584
BEGIN DESCRIPTION:
South Double Creek 67.0
END DESCRIPTION:
XS GIS Cut Line= 3
      1604617.26       970206.99      1604701.72       970332.82
      1604857.77       970509.35
#Sta/Elev= 30
  4848.4   887.1    4864  883.63  4882.6  881.02  4911.4  871.82  4939.8  864.17
    4957  860.86  4983.8  854.61  4991.8  851.04  4993.3  848.04  5006.7  848.04
  5008.2  851.04  5008.7  854.64  5014.4  856.45  5021.2  857.15  5025.4  858.26
  5039.3  861.41  5046.8  863.75  5053.6  865.61  5070.9  869.62    5088  873.24
  5119.1  876.66  5143.8  880.84  5154.8  885.49  5158.8   886.8  5179.8  886.33
  5190.3  886.97  5201.1  888.59  5218.5  891.59  5222.5  892.03  5235.6  892.43
#Mann= 3 ,-1 , 0
  4848.4     .09       0  4991.8     .05       0  5008.2     .09       0
Bank Sta=4991.8,5008.2
Exp/Cntr=0.3,0.1

Type RM Length L Ch R = 1 ,32416   ,416,416,416
BEGIN DESCRIPTION:
South Double Creek 66.0
END DESCRIPTION:
XS GIS Cut Line= 5
      1603980.46       970509.35      1604175.16       970541.42
      1604237.01       970566.62      1604683.68        970717.8
       1604825.8       970708.28
#Sta/Elev= 30
    4800  910.38  4855.5  903.17  4867.3  901.13  4898.1  893.86  4913.4  889.37
  4953.9  873.65  4983.1  858.81  4991.8   849.3  4993.3   846.3  5006.7   846.3
  5008.2   849.3  5009.1  849.68  5013.7   851.6  5034.1  855.63    5050  855.96
  5062.8  856.23    5087  855.77  5136.4  858.14  5159.9  858.66  5317.6  857.11
  5359.9  857.54  5385.1     857  5490.5  857.14  5514.4  857.62  5538.4  858.78
  5570.9  861.12  5580.1  862.34    5624  873.69    5646  882.06  5678.1  891.59
#Mann= 5 ,-1 , 0
    4800     .09       0  4991.8     .05       0  5009.1     .09       0
    5050    .035       0  5570.9     .09       0
Bank Sta=4991.8,5008.2
Exp/Cntr=0.3,0.1

Type RM Length L Ch R = 1 ,32000   ,500,500,500
BEGIN DESCRIPTION:
South Double Creek 65.0
END DESCRIPTION:
XS GIS Cut Line= 4
      1604051.47       970965.19      1604197.35       970908.59
      1604447.75        970816.3        1604825.         970775.
#Sta/Elev= 30
  4843.5  958.29  4855.5  955.14  4883.4  944.61    4892  938.09  4902.5  931.31
    4937  904.86  4950.1  896.15  4964.5  885.45  4968.8  880.93  4973.5  876.91
  4987.4  867.09  4990.7  863.45  4991.8   849.1  4993.3   846.1  5006.7   846.1
  5008.2   849.1  5011.3  852.08  5048.5  853.57  5080.5  854.98  5157.3  856.91
  5190.3  857.17    5234  856.36  5474.9  856.13  5521.1  857.81  5528.5  857.62
  5553.3   859.5    5589  864.16    5599   866.1  5621.4  874.78  5646.4  882.44
#Mann= 5 ,-1 , 0
  4843.5     .09       0  4991.8     .05       0  5008.2     .09       0
  5048.5    .035       0    5589     .09       0
Bank Sta=4991.8,5008.2
Exp/Cntr=0.3,0.1

Type RM Length L Ch R = 1 ,31500   ,400,400,400
BEGIN DESCRIPTION:
South Double Creek 64.0
END DESCRIPTION:
XS GIS Cut Line= 3
      1604230.14       971191.96      1604592.13       971200.31
      1604798.22       971226.32
#Sta/Elev= 30
  4637.9   948.8  4649.5  943.38  4666.1   937.3  4670.5   935.3    4680  929.92
  4700.8  923.06  4722.6   912.4  4744.2  903.43  4748.9  900.72  4815.6  868.82
  4822.4  866.11  4840.1  860.23  4847.3  858.63  4871.8  855.73  4913.2  854.94
  4920.3  854.39  4940.7  854.79  4954.6  854.23  4967.7  854.31  4979.8  851.31
  4991.7  846.11  4993.2  843.11  5006.8  843.11  5008.3  846.11  5041.2  851.13
  5082.5  869.82  5140.6  896.97    5156  901.91  5198.1  909.76  5207.7  910.76
#Mann= 3 ,-1 , 0
  4637.9     .09       0  4991.7     .05       0  5008.3     .09       0
Bank Sta=4991.7,5008.3
Exp/Cntr=0.3,0.1

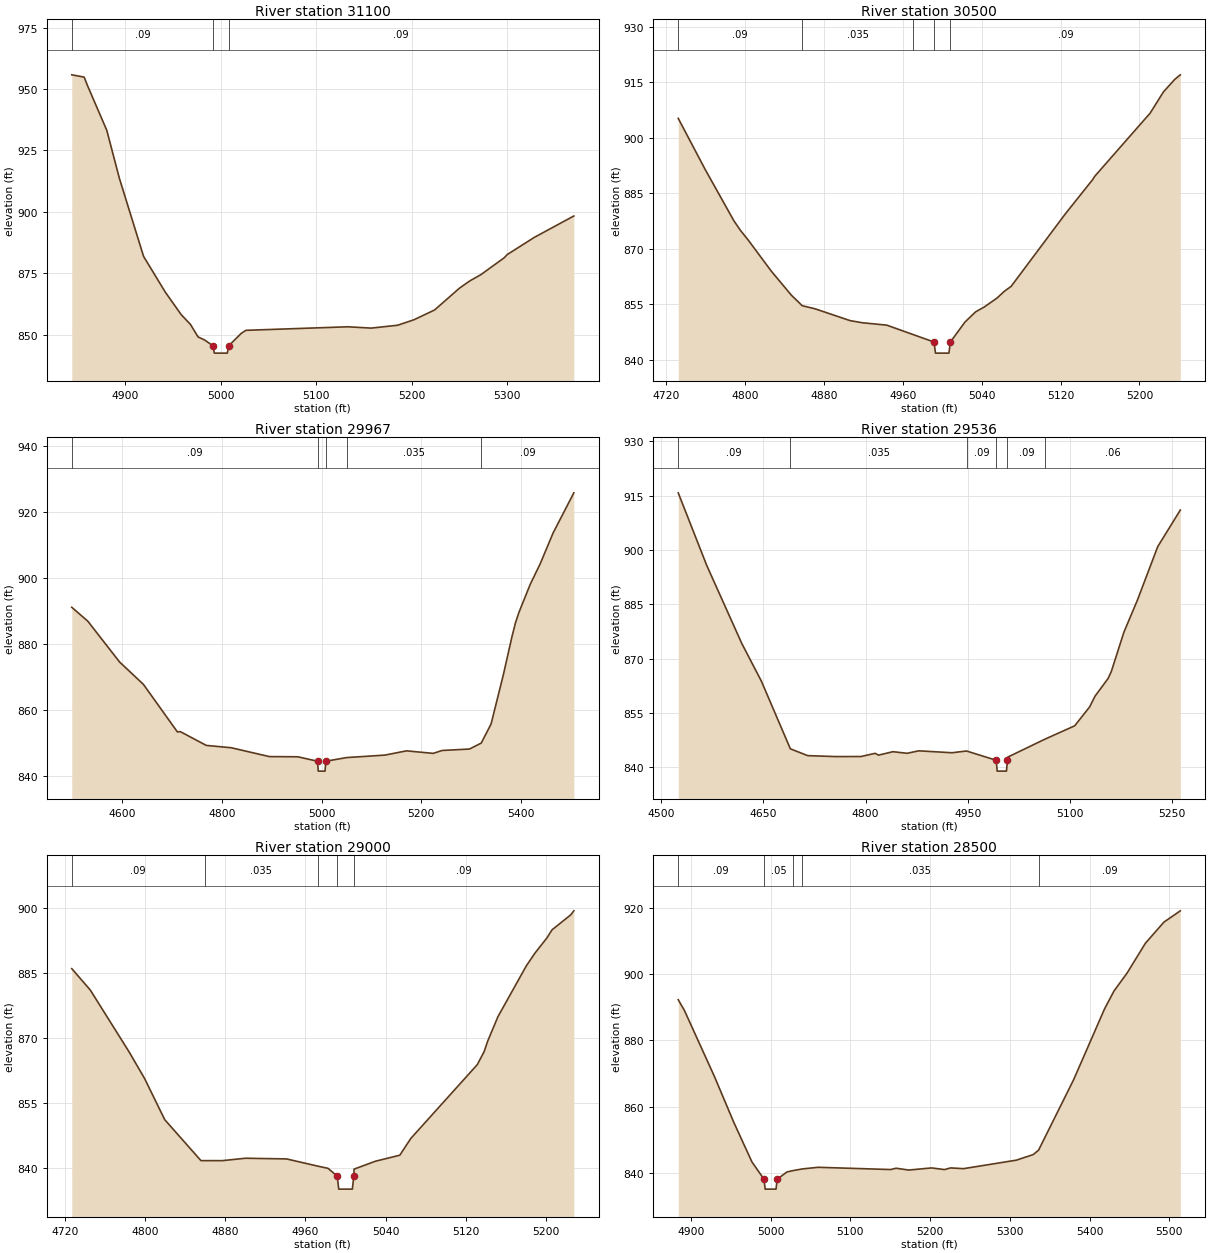
Type RM Length L Ch R = 1 ,31100   ,600,600,600
BEGIN DESCRIPTION:
South Double Creek 63.0
END DESCRIPTION:
XS GIS Cut Line= 4
      1604454.62       971716.52      1604530.21       971592.82
      1604566.86       971530.98      1604750.11        971281.3
#Sta/Elev= 30
  4843.7  955.79  4856.7  954.87    4860  951.59  4880.4  933.23  4893.6  913.72
  4918.9  882.03  4919.5  881.58  4941.9  867.27  4958.4  858.22  4968.3  854.14
  4976.1  849.13  4983.1  847.85  4991.7  845.52  4993.2  842.52  5006.8  842.52
  5008.3  845.52  5021.4  850.56  5026.3   851.8  5133.2  853.24  5157.6   852.7
  5185.4  853.87  5202.6  856.11  5224.2  860.09  5250.4  869.01  5261.1  871.91
  5272.7  874.46  5297.1  881.31  5300.5  882.67  5328.7  889.62  5370.2  898.34
#Mann= 3 ,-1 , 0
  4843.7     .09       0  4991.7     .05       0  5008.3     .09       0
Bank Sta=4991.7,5008.3
Exp/Cntr=0.3,0.1

Type RM Length L Ch R = 1 ,30500   ,533,533,533
BEGIN DESCRIPTION:
South Double Creek 62.0
END DESCRIPTION:
XS GIS Cut Line= 3
      1605098.29       971705.06      1605100.01       971437.44
      1605084.55       971196.54
#Sta/Elev= 30
  4732.4   905.2  4759.8  891.35  4788.8  877.54  4795.5  874.92  4803.3  872.34
  4826.8   863.9  4847.2   857.4  4858.1  854.58  4870.7  853.78  4906.7  850.55
    4919  849.98  4943.8  849.33  4970.6  846.78  4991.7  844.77  4993.2  841.77
  5006.8  841.77  5008.3  844.77    5023  850.14  5033.9  852.93  5042.5  854.21
  5055.5  856.63    5063  858.47  5069.9  859.81    5125  879.45  5152.6  888.67
  5154.6  889.53  5210.9  906.64  5224.3  912.35  5235.8  915.74  5241.4  916.96
#Mann= 5 ,-1 , 0
  4732.4     .09       0  4858.1    .035       0  4970.6     .09       0
  4991.7     .05       0  5008.3     .09       0
Bank Sta=4991.7,5008.3
Exp/Cntr=0.3,0.1

Type RM Length L Ch R = 1 ,29967   ,431,431,431
BEGIN DESCRIPTION:
South Double Creek 61.0
END DESCRIPTION:
XS GIS Cut Line= 4
      1605151.74       971665.74      1605531.22       971418.73
      1605645.75       971386.67      1606080.97       971370.63
#Sta/Elev= 30
  4498.7  891.09  4530.7  886.92  4594.7  874.52  4642.4  867.77  4710.7  853.35
  4716.3  853.47  4768.5  849.29  4818.6  848.58  4895.1   845.9  4952.2  845.84
  4991.7   844.5  4993.2   841.5  5006.8   841.5  5008.3   844.5    5050   845.6
  5126.9  846.35  5170.2  847.64  5223.8  846.87  5241.6  847.75  5296.6  848.19
  5320.1  849.99  5339.9  855.78  5364.3  870.55  5381.6  882.09  5388.8   886.4
  5395.6  889.49  5418.4  898.04  5438.7  904.36  5464.2  913.56  5505.9  925.74
#Mann= 5 ,-1 , 0
  4498.7     .09       0  4991.7     .05       0  5008.3     .09       0
    5050    .035       0  5320.1     .09       0
Bank Sta=4991.7,5008.3
Exp/Cntr=0.3,0.1

Type RM Length L Ch R = 1 ,29536   ,536,536,536
BEGIN DESCRIPTION:
South Double Creek 60.0
END DESCRIPTION:
XS GIS Cut Line= 4
      1605233.44       971851.66      1605638.88       971803.56
      1605767.15       971798.98      1605966.44        971819.6
#Sta/Elev= 30
    4525  915.74  4566.9  895.69  4618.4  874.15    4647  863.82  4689.6  845.13
  4715.1  843.25  4756.9  842.99  4793.3  843.01    4814  843.89    4819  843.39
  4840.2  844.34    4861   843.9    4878  844.58  4926.8  844.05  4948.2  844.53
  4991.7  841.98  4993.2  838.98  5006.8  838.98  5008.3  841.98  5009.1  842.88
  5063.8  847.84  5106.9  851.47  5128.9  856.69  5136.8  859.65    5156  864.54
  5160.6  866.39  5179.1  877.25    5199  886.13  5228.9  900.92    5262  910.99
#Mann= 6 ,-1 , 0
    4525     .09       0  4689.6    .035       0  4948.2     .09       0
  4991.7     .05       0  5008.3     .09       0  5063.8     .06       0
Bank Sta=4991.7,5008.3
Exp/Cntr=0.3,0.1

Type RM Length L Ch R = 1 ,29000   ,500,500,500
BEGIN DESCRIPTION:
South Double Creek 59.0
END DESCRIPTION:
XS GIS Cut Line= 3
      1605313.61       972181.52      1605581.59       972235.61
      1605808.39        972259.4
#Sta/Elev= 30
  4726.6  886.04  4745.1   881.1  4783.8  866.85  4799.4  860.65  4819.4  851.19
  4855.6  841.73  4859.2  841.73  4876.8  841.72  4900.1  842.28  4941.1  842.12
  4972.2  840.46  4982.5  839.95  4991.7  838.15  4993.2  835.15  5006.8  835.15
  5008.3  838.15  5008.5  839.76  5029.7  841.58  5054.2  842.98  5065.2  846.85
  5131.6  863.89  5138.4  866.88    5142  869.33  5152.2  874.95  5180.6   886.7
  5189.2  889.63  5201.2  893.16  5206.2  894.99  5224.9  898.45    5228  899.38
#Mann= 5 ,-1 , 0
  4726.6     .09       0  4859.2    .035       0  4972.2     .09       0
  4991.7     .05       0  5008.3     .09       0
Bank Sta=4991.7,5008.3
Exp/Cntr=0.3,0.1

Type RM Length L Ch R = 1 ,28500   ,500,500,500
BEGIN DESCRIPTION:
South Double Creek 58.0
END DESCRIPTION:
XS GIS Cut Line= 3
      1605134.94       972456.39      1605247.15        972485.1
      1605744.25       972614.45
#Sta/Elev= 30
  4884.2  892.25    4892  888.99  4929.9   868.9  4953.8  855.27  4976.6   843.3
  4991.7  838.08  4993.2  835.08  5006.8  835.08  5008.3  838.08  5020.5  840.26
  5028.4  840.68  5039.6  841.17  5059.6  841.67  5150.5  840.99  5157.3  841.39
  5173.2  840.84  5201.9  841.48    5218  840.98  5225.7  841.48  5241.9  841.26
  5308.1  843.82  5329.3  845.51    5336  846.85  5379.9  868.08  5418.6  889.42
  5430.6   894.9  5446.9  900.27  5469.9  909.29  5493.2  915.68  5513.7  919.08
#Mann= 5 ,-1 , 0
  4884.2     .09       0  4991.7     .05       0  5028.4     .09       0
  5039.6    .035       0    5336     .09       0
Bank Sta=4991.7,5008.3
Exp/Cntr=0.3,0.1

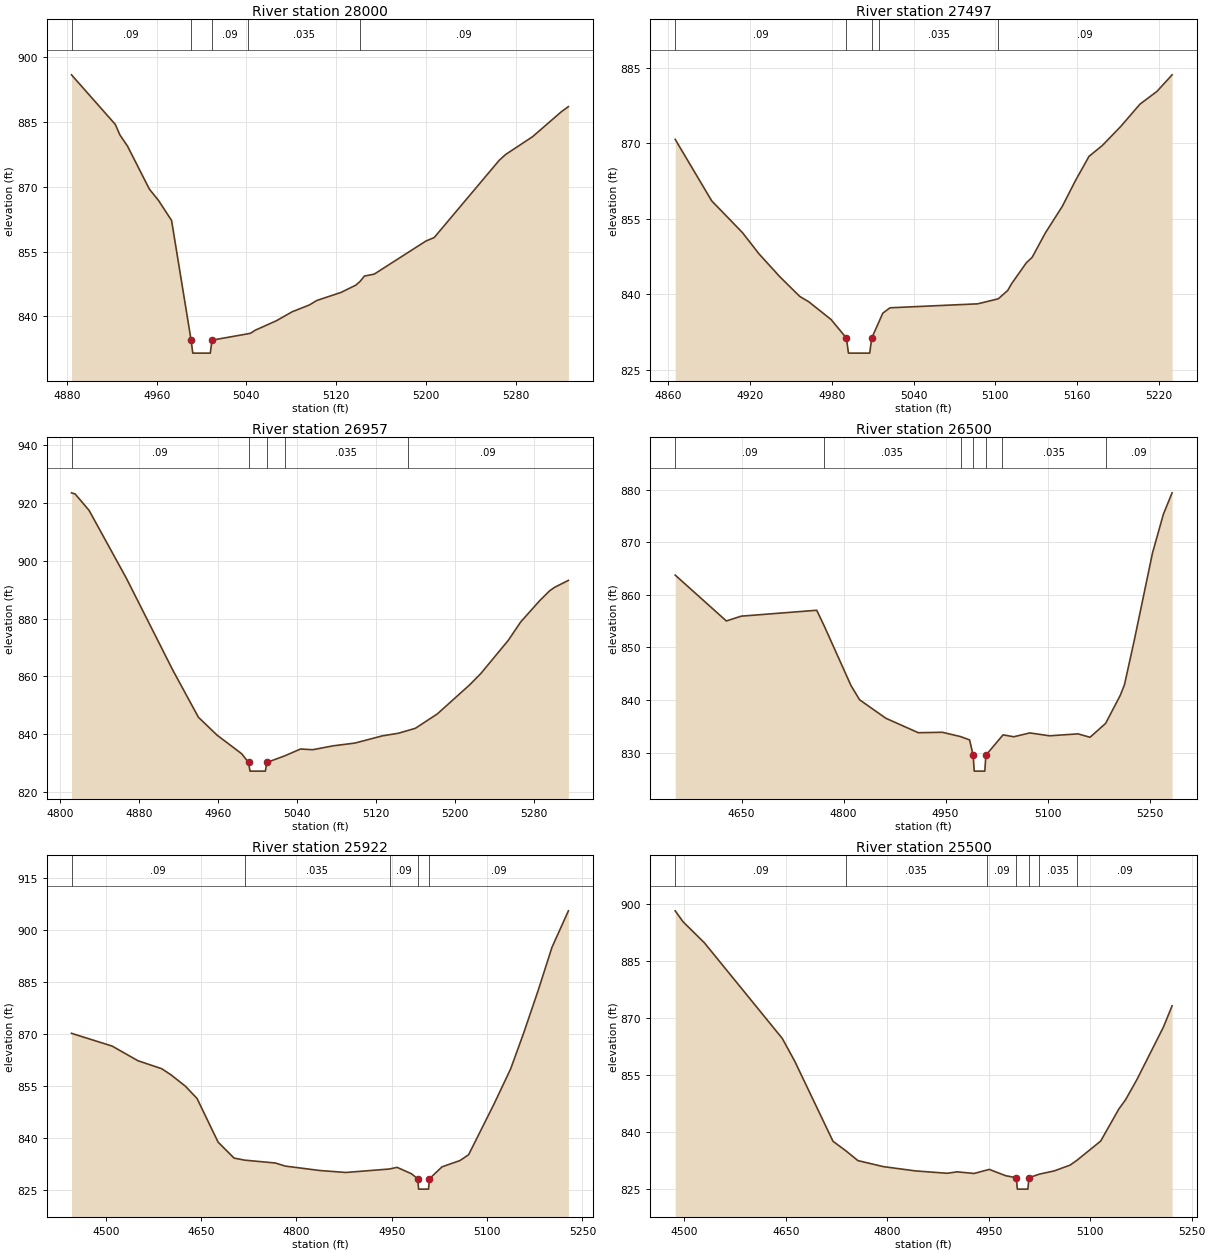
Type RM Length L Ch R = 1 ,28000   ,503,503,503
BEGIN DESCRIPTION:
South Double Creek 57.0
END DESCRIPTION:
XS GIS Cut Line= 3
      1604935.65       972921.39      1605047.28        972890.2
      1605366.29       972818.31
#Sta/Elev= 30
  4884.1  895.87  4923.2  884.38  4927.2  881.98    4934  879.39  4953.5  869.44
  4961.7   866.8  4973.3  862.18  4990.7   834.5  4992.2   831.5  5007.8   831.5
  5009.3   834.5  5041.3  835.97  5043.9  836.12  5047.7  836.78  5066.7  838.99
  5080.9  841.08    5096  842.62  5102.7  843.67  5124.4  845.55  5137.5  847.22
  5141.4  848.11  5145.2  849.33  5153.9  849.77  5199.9  857.41  5207.4  858.24
  5265.4  876.12  5271.2  877.47  5295.1  881.57  5320.9  887.37    5327  888.52
#Mann= 5 ,-1 , 0
  4884.1     .09       0  4990.7     .05       0  5009.3     .09       0
  5041.3    .035       0  5141.4     .09       0
Bank Sta=4990.7,5009.3
Exp/Cntr=0.3,0.1

Type RM Length L Ch R = 1 ,27497   ,540,540,540
BEGIN DESCRIPTION:
South Double Creek 56.0
END DESCRIPTION:
XS GIS Cut Line= 4
      1605205.95       973381.81      1605279.25       973303.93
      1605354.84        973262.7      1605457.92       973125.26
#Sta/Elev= 30
    4865  870.79  4891.8  858.57  4914.4  852.25  4926.5  848.04  4941.8  843.49
  4956.5  839.56    4963  838.52  4979.4  834.99  4990.7   831.3  4992.2   828.3
  5007.8   828.3  5009.3   831.3  5014.8  834.65  5017.4  836.24  5022.7  837.31
  5087.1   838.1  5102.2   839.1  5109.1  840.75    5112  842.11  5122.8  846.26
  5127.1  847.36  5136.7  852.17  5149.2  857.48  5158.9  862.62  5168.8  867.41
  5178.7   869.6  5192.1  873.36  5206.2  877.79  5218.7  880.33  5229.8  883.62
#Mann= 5 ,-1 , 0
    4865     .09       0  4990.7     .05       0  5009.3     .09       0
  5014.8    .035       0  5102.2     .09       0
Bank Sta=4990.7,5009.3
Exp/Cntr=0.3,0.1

Type RM Length L Ch R = 1 ,26957   ,457,457,457
BEGIN DESCRIPTION:
South Double Creek 55.0
END DESCRIPTION:
XS GIS Cut Line= 3
      1605824.42       973480.31      1605737.38       973340.58
      1605567.32       973046.92
#Sta/Elev= 30
  4811.2  923.47  4814.9  923.07    4829  917.41  4866.8  893.96  4913.9  862.17
  4939.9  845.86  4958.9  839.65  4983.8  833.24  4990.7  830.23  4992.2  827.23
  5007.8  827.23  5009.3  830.23  5027.4  832.51  5043.4  834.87  5055.8  834.64
  5076.8  835.99  5098.7  836.94  5126.5  839.43  5142.7  840.33  5152.4  841.29
  5159.9  842.04  5182.1  846.99  5215.2  857.14  5226.4  861.03  5254.1  872.45
  5266.8  878.85    5286  886.19  5296.1   889.6  5301.3  890.83  5315.1  893.19
#Mann= 5 ,-1 , 0
  4811.2     .09       0  4990.7     .05       0  5009.3     .09       0
  5027.4    .035       0  5152.4     .09       0
Bank Sta=4990.7,5009.3
Exp/Cntr=0.3,0.1

Type RM Length L Ch R = 1 ,26500   ,578,578,578
BEGIN DESCRIPTION:
South Double Creek 54.0
END DESCRIPTION:
XS GIS Cut Line= 3
      1606323.78       973393.26       1606070.2        973024.5
      1605906.88       972793.12
#Sta/Elev= 30
  4552.5  863.75  4627.7  855.04  4649.6  855.95  4760.6  857.07  4771.6   854.1
    4811  842.77  4823.6  840.07  4862.3  836.55    4910  833.81  4945.4  833.89
  4972.1  833.07  4985.4  832.44  4990.7  829.51  4992.2  826.51  5007.8  826.51
  5009.3  829.51  5032.5  833.08  5034.6   833.4  5050.4  833.04  5074.1  833.77
  5102.9  833.22  5144.9  833.59  5162.5  832.94  5185.4  835.57  5206.9  840.89
  5213.1  842.89  5227.2  851.13  5254.4  867.96  5270.4  875.32  5283.2  879.38
#Mann= 7 ,-1 , 0
  4552.5     .09       0  4771.6    .035       0  4972.1     .09       0
  4990.7     .05       0  5009.3     .09       0  5032.5    .035       0
  5185.4     .09       0
Bank Sta=4990.7,5009.3
Exp/Cntr=0.3,0.1

Type RM Length L Ch R = 1 ,25922   ,422,422,422
BEGIN DESCRIPTION:
South Double Creek 53.0
END DESCRIPTION:
XS GIS Cut Line= 5
      1606479.54       973381.81      1606516.19       973102.35
      1606507.03       972882.45      1606545.97       972811.44
      1606495.58       972619.03
#Sta/Elev= 30
    4446   870.2  4509.9  866.52  4550.6  862.28    4588  859.98  4602.5  858.22
    4625  854.97  4643.5  851.41  4676.7  838.78  4701.8  834.18  4718.4  833.59
  4766.8  832.76  4782.4  831.87    4837  830.59  4877.7  830.03  4946.4  831.03
  4958.3  831.51  4980.9  829.66  4990.7  828.22  4992.2  825.22  5007.8  825.22
  5009.3  828.22    5029  831.65  5057.4  833.48  5070.9  835.16  5111.1  849.88
  5137.1  859.97  5157.5  870.28  5180.4  882.62    5202  895.01  5227.9  905.56
#Mann= 5 ,-1 , 0
    4446     .09       0  4718.4    .035       0  4946.4     .09       0
  4990.7     .05       0  5009.3     .09       0
Bank Sta=4990.7,5009.3
Exp/Cntr=0.3,0.1

Type RM Length L Ch R = 1 ,25500   ,563,563,563
BEGIN DESCRIPTION:
South Double Creek 52.0
END DESCRIPTION:
XS GIS Cut Line= 4
      1606768.16       973436.78      1606825.43        973040.5
      1606901.39       972956.63       1607077.4       972822.89
#Sta/Elev= 30
  4486.4  898.16  4498.1  895.27  4529.5  889.76  4644.7  864.59  4663.2  858.57
  4719.7  837.53  4738.6  835.04  4756.6  832.44  4794.2  830.86  4841.2  829.74
  4888.6  829.11  4903.2  829.49  4928.2  829.06  4946.7  829.94  4950.7  830.13
    4975  828.47  4990.7  827.94  4992.2  824.94  5007.8  824.94  5009.3  827.94
  5024.7  828.88  5047.1  829.75  5070.3  831.27  5080.5  832.55  5115.4  837.58
  5142.3  846.03  5152.1  848.42    5169  853.77  5208.3  867.62    5221  873.17
#Mann= 7 ,-1 , 0
  4486.4     .09       0  4738.6    .035       0  4946.7     .09       0
  4990.7     .05       0  5009.3     .09       0  5024.7    .035       0
  5080.5     .09       0
Bank Sta=4990.7,5009.3
Exp/Cntr=0.3,0.1

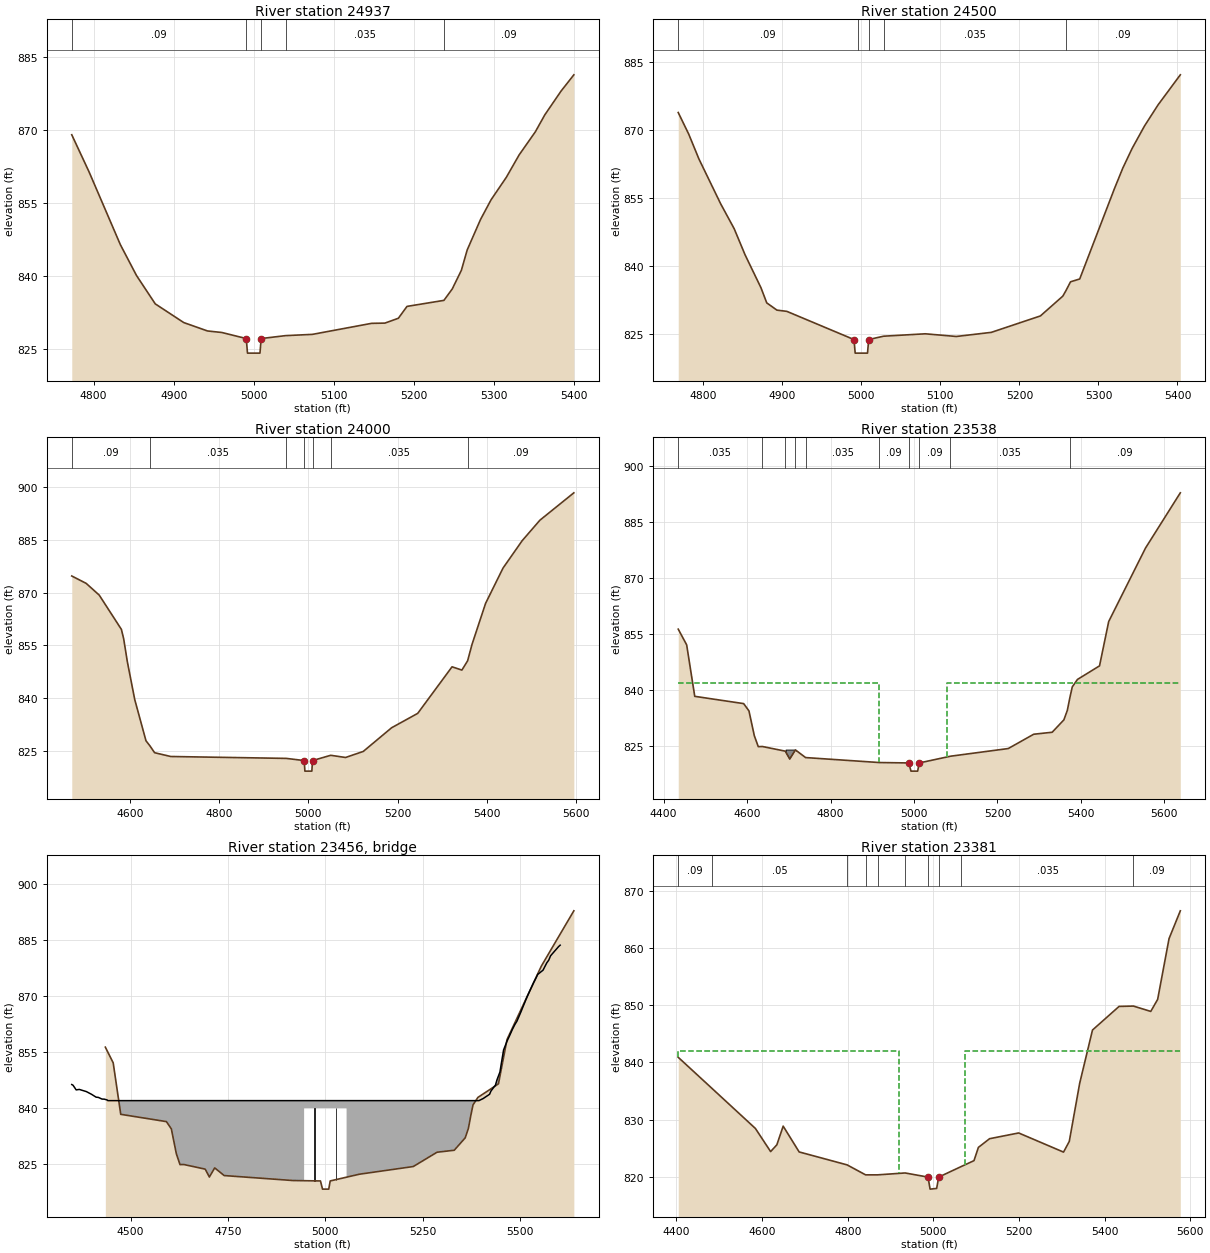
Type RM Length L Ch R = 1 ,24937   ,437,437,437
BEGIN DESCRIPTION:
South Double Creek 51.0
END DESCRIPTION:
XS GIS Cut Line= 5
      1607017.84       973411.59      1607180.48       973363.48
      1607221.71       973315.38      1607253.78       973255.82
        1607224.       972930.55
#Sta/Elev= 30
  4772.7  869.06  4794.4  861.39  4833.4  846.44  4853.6  840.08    4877  834.25
  4912.6   830.4  4942.3  828.67  4960.1  828.36  4990.7  827.11  4992.2  824.11
  5007.8  824.11  5009.3  827.11  5039.7  827.71  5073.3  827.97  5147.2  830.24
  5163.9  830.29  5180.7  831.29  5191.5  833.73  5237.6  834.97    5248  837.32
  5259.4  841.16  5266.7  845.36  5283.3  851.61  5296.5  855.68  5315.5  860.29
  5331.5   864.9  5351.8  869.67  5363.7  873.18    5384  878.07  5399.9   881.4
#Mann= 5 ,-1 , 0
  4772.7     .09       0  4990.7     .05       0  5009.3     .09       0
  5039.7    .035       0  5237.6     .09       0
Bank Sta=4990.7,5009.3
Exp/Cntr=0.3,0.1

Type RM Length L Ch R = 1 ,24500   ,500,500,500
BEGIN DESCRIPTION:
South Double Creek 50.0
END DESCRIPTION:
XS GIS Cut Line= 4
      1607203.38       973748.31      1607419.38       973664.55
      1607496.58       973640.65       1607711.9       973400.13
#Sta/Elev= 30
  4768.3  873.89  4781.6  869.11  4794.4  863.66    4822  853.72  4839.1  848.22
  4852.8  842.48    4873  835.17  4880.3  831.83  4893.2  830.23  4905.7  829.96
  4990.7  823.73  4992.2  820.73  4995.3  820.73  5007.8  820.73  5009.3  823.73
  5028.1  824.47  5080.8     825  5120.2  824.41  5164.5  825.32  5226.6  828.95
  5254.9  833.32  5258.5  834.41  5264.7  836.49  5276.3  837.11  5319.9  856.92
  5330.8   861.6  5342.7  865.98  5358.2  870.89  5375.4  875.57  5403.6  882.22
#Mann= 5 ,-1 , 0
  4768.3     .09       0  4995.3     .05       0  5009.3     .09       0
  5028.1    .035       0  5258.5     .09       0
Bank Sta=4990.7,5009.3
Exp/Cntr=0.3,0.1

Type RM Length L Ch R = 1 ,24000   ,462,462,462
BEGIN DESCRIPTION:
South Double Creek 49.0
END DESCRIPTION:
XS GIS Cut Line= 5
      1607022.42       974169.79      1607489.71       974160.62
      1607548.76       974139.12      1607605.91       974113.43
      1608126.51       974002.57
#Sta/Elev= 30
  4469.8   874.7  4502.1   872.6  4531.3  869.27    4581  859.52  4586.1  856.85
  4594.4  850.28    4611  839.52  4636.1  827.84  4645.1  826.37  4655.4  824.45
  4691.5  823.37  4950.7  822.83  4990.7  822.21  4992.2  819.21  5007.8  819.21
  5009.3  822.21    5050  823.71  5083.4  823.09    5123  824.81  5186.5  831.54
    5245  835.63    5322  848.88    5344  847.94  5356.9  850.59  5366.6   855.2
  5397.1  866.91  5436.2  876.95    5479  884.72  5518.8  890.56  5594.9  898.35
#Mann= 7 ,-1 , 0
  4469.8     .09       0  4645.1    .035       0  4950.7     .09       0
  4990.7     .05       0  5009.3     .09       0    5050    .035       0
  5356.9     .09       0
Bank Sta=4990.7,5009.3
Exp/Cntr=0.5,0.3

Type RM Length L Ch R = 1 ,23538   ,157,157,157
BEGIN DESCRIPTION:
NC HWY 66S - US
END DESCRIPTION:
XS GIS Cut Line= 6
      1607306.46       974916.53      1607494.29       974756.19
      1607651.25       974541.74      1607808.29       974369.98
      1607860.79       974197.27      1608085.28       974034.64
#Sta/Elev= 30
    4435  856.32  4455.2  852.12  4474.6  838.33  4591.8  836.38  4604.5  834.43
  4617.4  827.76  4626.8  824.86  4636.7  824.89  4691.5  823.65  4702.2  821.54
  4715.9  823.98  4740.2  821.93  4916.8   820.6  4987.5  820.49 4992.79   818.3
 5008.77   818.3  5012.5  820.49  5087.3  822.29  5225.9  824.35 5286.89  828.18
  5331.1  828.71  5359.2  832.03  5367.5  834.59  5373.6  838.01  5379.3  840.86
  5391.8  842.86  5444.6  846.49  5466.6  858.37  5554.8  878.04  5638.2  892.83
#Mann= 10 ,-1 , 0
    4435    .035       0  4636.7     .07       0  4691.5    .045       0
  4715.9     .07       0  4740.2    .035       0  4916.8     .09       0
  4987.5     .05       0  5012.5     .09       0  5087.3    .035       0
  5373.6     .09       0
#XS Ineff= 2 , 0
       0    4915     842    5080       0     842
Permanent Ineff=
       F       F
#Block Obstruct= 1 ,-1
  4693.5  4717.9  823.94
Bank Sta=4987.5,5012.5
Exp/Cntr=0.5,0.3

Type RM Length L Ch R = 3 ,23456   ,,,
BEGIN DESCRIPTION:
NC HWY 66S
Structure ID: NC 66
Approximate Survey Structure
END DESCRIPTION:
Bridge Culvert--1,0,-1,-1, 0
Deck Dist Width WeirC Skew NumUp NumDn MinLoCord MaxHiCord MaxSubmerge Is_Ogee
64.5,35,3,0, 45, 45, , , , 0, 1,1,,
  4348.8    4352  4360.1  4368.1  4386.3  4399.8  4411.2  4417.2  4426.4  4432.6
  4439.9  4441.3  4945.5  4945.5  5054.5  5054.5  5394.5  5400.6  5404.1  5404.6
  5421.8  5425.2  5434.4  5436.5  5440.8  5448.4    5452  5457.8  5467.1  5477.3
  5480.1    5487  5491.8  5500.6  5515.4  5520.4  5534.4  5540.2  5545.3    5559
  5568.9  5573.6  5578.5  5599.1    5603
  846.31  846.13  844.88     845  844.42  843.68  842.93  842.86  842.42  842.39
  842.16     842     842     842     842     842     842  842.32  842.49  842.51
   843.7  844.54  845.85  846.03  847.57  849.66     852   855.6  858.04  860.34
  861.02  862.43  863.23  865.34  869.12  870.32  873.49  874.67  875.79  876.93
  878.94  879.59   880.8  883.26  883.63
     798     798     798     798     798     798     798     798     798     798
     798     798     798     840     840     798     798     798     798     798
     798     798     798     798     798     798     798     798     798     798
     798     798     798     798     798     798     798     798     798     798
     798     798     798     798     798
  4348.8    4352  4360.1  4368.1  4386.3  4399.8  4411.2  4417.2  4426.4  4432.6
  4439.9  4441.3  4945.5  4945.5  5054.5  5054.5  5394.5  5400.6  5404.1  5404.6
  5421.8  5425.2  5434.4  5436.5  5440.8  5448.4    5452  5457.8  5467.1  5477.3
  5480.1    5487  5491.8  5500.6  5515.4  5520.4  5534.4  5540.2  5545.3    5559
  5568.9  5573.6  5578.5  5599.1    5603
  846.31  846.13  844.88     845  844.42  843.68  842.93  842.86  842.42  842.39
  842.16     842     842     842     842     842     842  842.32  842.49  842.51
   843.7  844.54  845.85  846.03  847.57  849.66     852   855.6  858.04  860.34
  861.02  862.43  863.23  865.34  869.12  870.32  873.49  874.67  875.79  876.93
  878.94  879.59   880.8  883.26  883.63
     798     798     798     798     798     798     798     798     798     798
     798     798     798     840     840     798     798     798     798     798
     798     798     798     798     798     798     798     798     798     798
     798     798     798     798     798     798     798     798     798     798
     798     798     798     798     798
Pier Skew, UpSta & Num, DnSta & Num=  ,4972.8, 2 ,4972.8, 2 , 0 , 0 , 0 ,0,0
       2       2
  820.51     840
       2       2
  824.96     840
Pier Skew, UpSta & Num, DnSta & Num=  ,5027.3, 2 ,5027.3, 2 , 0 , 0 , 0 ,0,0
       2       2
  821.64     840
       2       2
  825.53     840
Abutment Skew #Up #Dn= , 2 , 2
  4945.5    4965
     840  820.64
  4945.5    4965
     840  823.48
Abutment Skew #Up #Dn= , 2 , 2
    5035  5054.5
  821.75     840
    5035  5054.5
  824.38     840
BR Coef= 1 , 1 , 0 ,1.25, 0 ,,,0.8,0,2,0,
WSPro=,,,, 1 ,,,, 0 ,,,, 0 ,,,,-1 ,-1 ,-1 , 0 , 0 , 0 , 0 , 0
BC Design=,, 0 ,, 0 ,,,,,,
BC HTab HWMax=892.83

Type RM Length L Ch R = 1 ,23381   ,519,519,519
BEGIN DESCRIPTION:
NC HWY 66S - DS
END DESCRIPTION:
XS GIS Cut Line= 6
       1607370.6       975044.81      1607707.32        974680.6
      1607959.29       974495.06      1608023.43       974442.37
      1608007.39       974334.71      1608007.39       974162.92
#Sta/Elev= 30
  4404.2   840.9  4482.1  835.54  4584.5  828.48    4620  824.45  4634.5  825.63
  4649.3  828.89  4686.6  824.39  4798.6  822.13 4841.79  820.39  4869.8  820.39
  4934.2  820.72  4987.5     820 4992.45   817.9 5007.74  818.02  5012.5     820
 5065.72  821.86 5094.96  822.87  5105.2  825.18  5131.4   826.7  5199.3   827.7
  5304.1  824.36  5317.5  826.23  5341.8  836.38  5371.7  845.66  5433.8  849.78
  5467.3  849.84  5507.8  848.91  5523.9  851.01  5550.5  861.61  5576.8  866.46
#Mann= 10 ,-1 , 0
  4404.2     .09       0  4482.1     .05       0  4798.6     .07       0
 4841.79     .04       0  4869.8     .07       0  4934.2     .09       0
  4987.5    .055       0  5012.5     .09       0 5065.72    .035       0
  5467.3     .09       0
#XS Ineff= 2 , 0
       0    4920     842    5075       0     842
Permanent Ineff=
       F       F
#Block Obstruct= 1 ,-1
  4831.9  4875.8     820
Bank Sta=4987.5,5012.5
Exp/Cntr=0.5,0.3