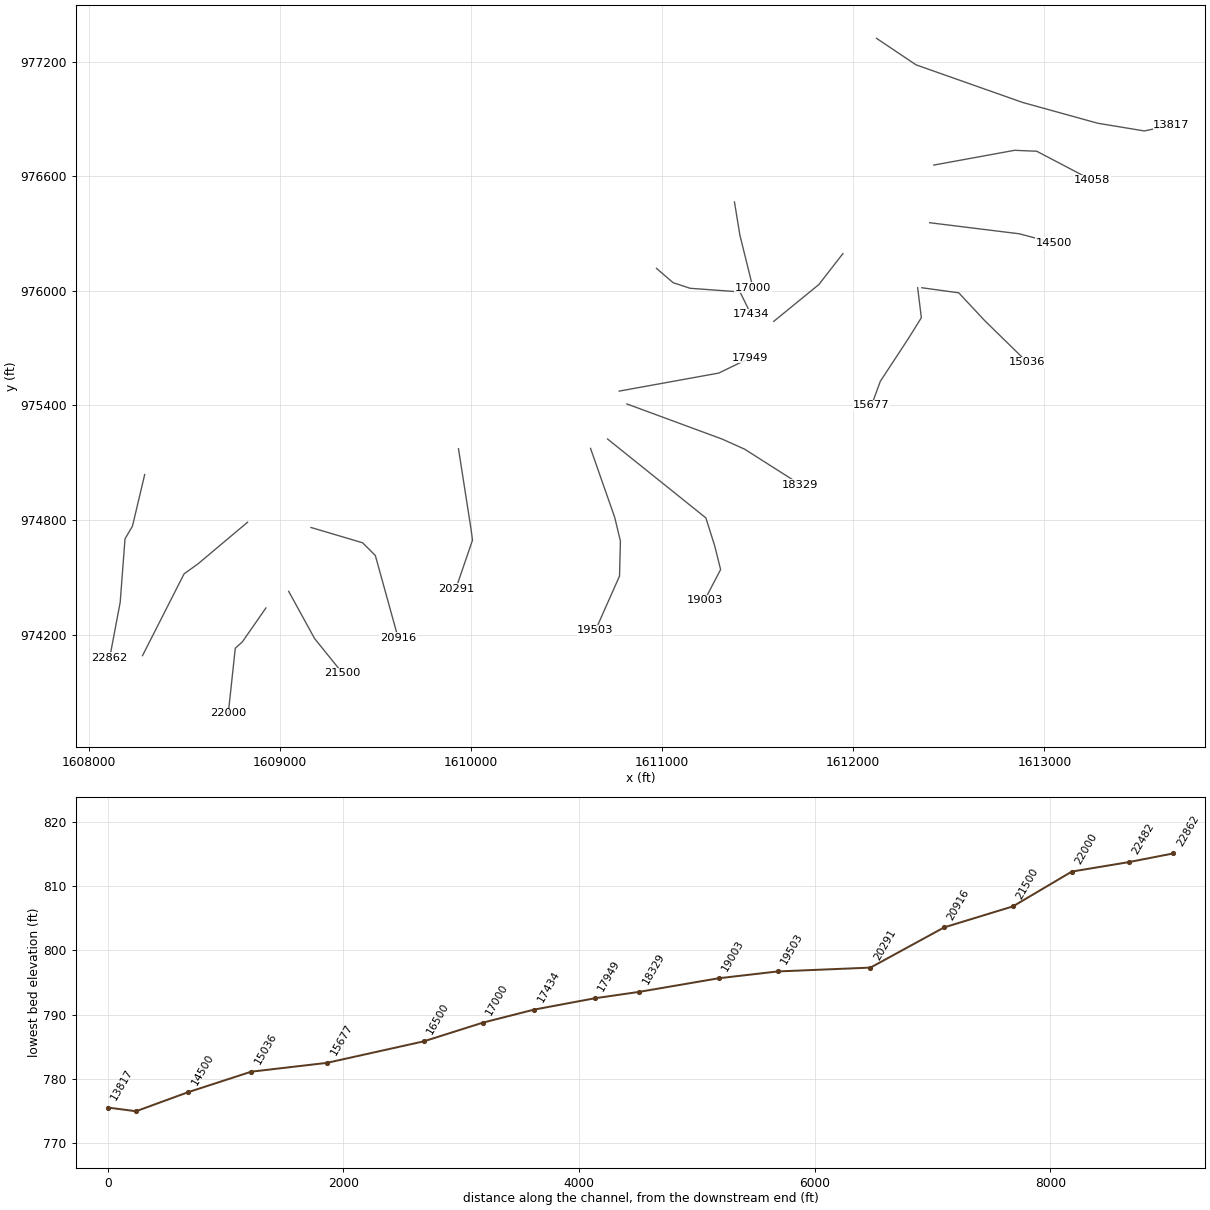
HEC-RAS study lds_south_double_crk.prj: South Double Creek Limited Detail Study

--- lds_south_double_crk.g01 (geometry) --- (continued)

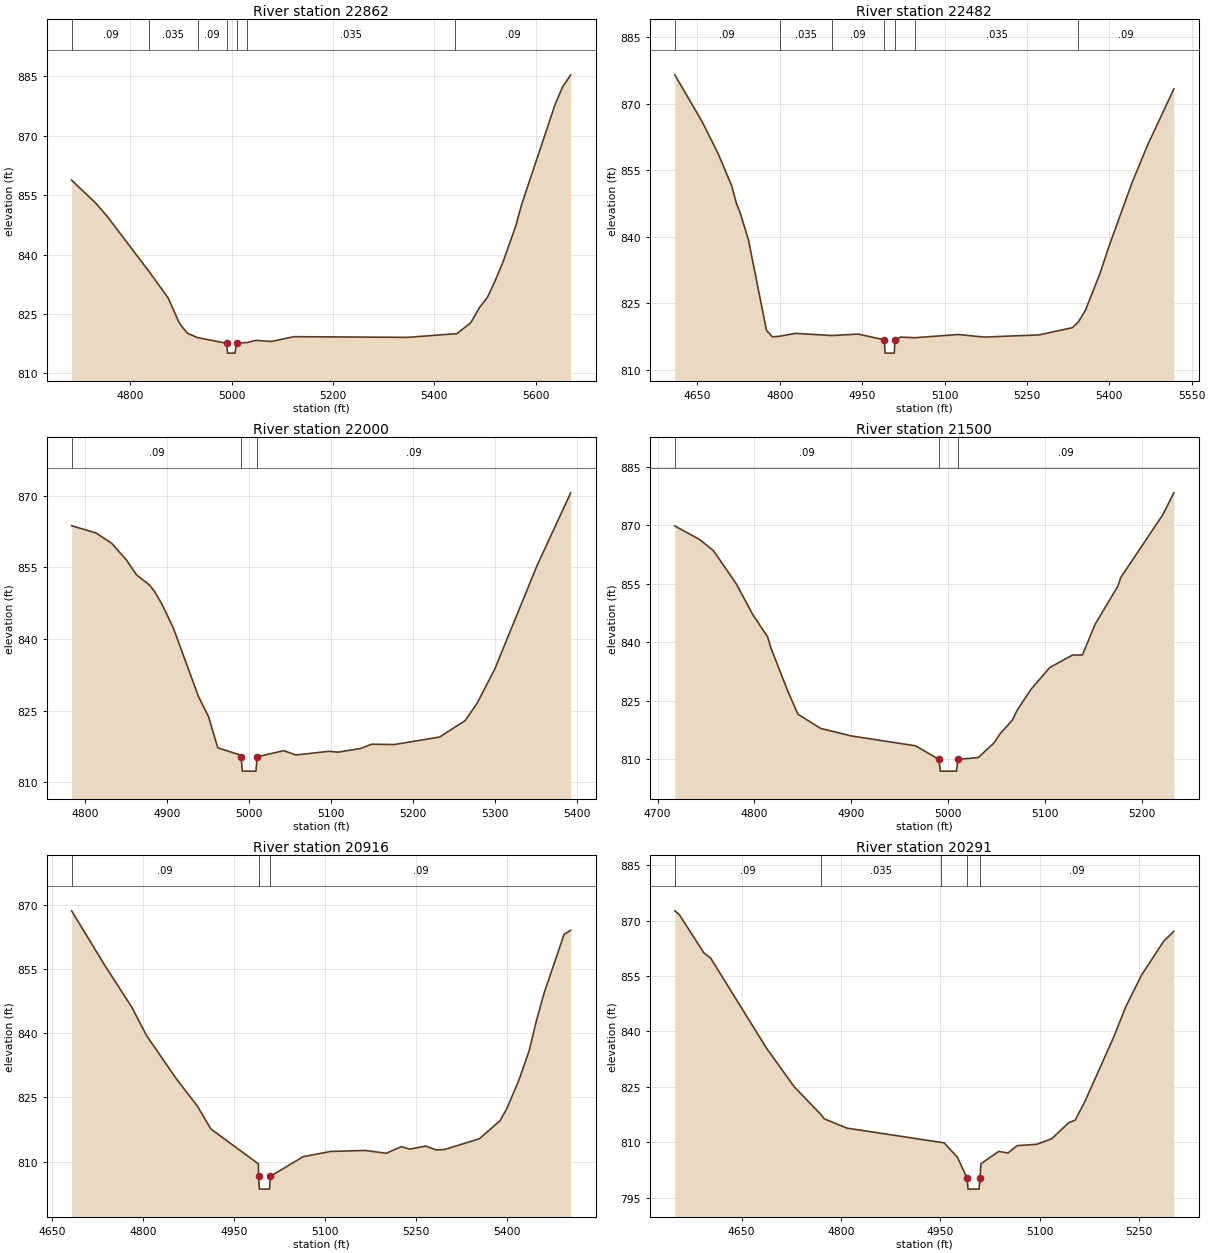
Type RM Length L Ch R = 1 ,22862   ,380,380,380
BEGIN DESCRIPTION:
South Double Creek 47.0
END DESCRIPTION:
XS GIS Cut Line= 5
      1608291.43       975037.94       1608227.3       974767.64
      1608188.36       974701.21      1608163.16       974369.07
      1608108.18       974078.16
#Sta/Elev= 30
  4684.7  858.77  4733.2  852.86  4754.6  849.68  4837.5  835.71  4875.2  829.02
  4896.3  822.93  4901.8   821.9  4913.1  820.14  4933.1  819.04  4990.2  817.63
 4992.18  815.13 5006.83  815.13  5009.8  817.63  5031.2  817.81  5048.3  818.36
  5078.3  818.07  5123.1  819.28  5347.2  819.11  5440.2  820.01  5443.8  819.99
  5471.7  822.81  5488.1  826.48  5504.5  829.21  5519.8  833.41  5535.6  838.25
  5560.2  847.14  5572.3  852.76  5637.7  877.77  5652.4  882.24  5668.7  885.35
#Mann= 7 ,-1 , 0
  4684.7     .09       0  4837.5    .035       0  4933.1     .09       0
  4990.2    .055       0  5009.8     .09       0  5031.2    .035       0
  5440.2     .09       0
Bank Sta=4990.2,5009.8
Exp/Cntr=0.3,0.1

Type RM Length L Ch R = 1 ,22482   ,482,482,482
BEGIN DESCRIPTION:
South Double Creek 46.0
END DESCRIPTION:
XS GIS Cut Line= 4
      1608829.73       974788.26      1608570.89       974570.65
      1608497.59       974517.96      1608279.98       974089.61
#Sta/Elev= 30
  4608.7  876.53  4657.8  866.12  4687.2  858.88  4712.4  851.49  4720.8  847.59
  4728.4  845.16    4743  839.24  4775.7   818.9  4786.4  817.45  4799.5  817.57
  4828.1  818.23  4894.9  817.74  4942.8  818.06  4990.2  816.77  4991.7  813.77
  5008.3  813.77  5009.8  816.77  5020.1  817.38  5046.3  817.25  5125.1  817.97
  5172.2  817.39  5272.2  817.88  5332.8  819.51  5343.8  820.82  5356.4  823.39
  5383.5  831.88  5398.8  837.63  5441.8  852.33  5469.6  860.63  5517.6  873.35
#Mann= 7 ,-1 , 0
  4608.7     .09       0  4799.5    .035       0  4894.9     .09       0
  4990.2     .05       0  5009.8     .09       0  5046.3    .035       0
  5343.8     .09       0
Bank Sta=4990.2,5009.8
Exp/Cntr=0.3,0.1

Type RM Length L Ch R = 1 ,22000   ,500,500,500
BEGIN DESCRIPTION:
South Double Creek 45.0
END DESCRIPTION:
XS GIS Cut Line= 4
      1608925.94       974339.29      1608802.29       974161.33
       1608765.6       974128.56      1608728.94       973787.25
#Sta/Elev= 30
  4783.3  863.71    4813   862.2  4832.2  860.03  4850.2  856.54  4862.6  853.39
  4878.6  851.25    4885  849.82  4893.6  847.27  4907.7  842.19  4938.1  827.94
  4950.5  823.69  4961.7  817.18  4988.4  815.72  4990.2   815.3  4991.7   812.3
  5008.3   812.3  5009.8   815.3  5042.3  816.59    5057  815.68  5097.3  816.45
  5108.5  816.28    5136  817.04  5149.6  817.94  5177.2  817.87  5232.3  819.44
  5263.7  822.88  5278.3  826.54  5299.6  833.59  5351.4  855.35  5392.5   870.6
#Mann= 3 ,-1 , 0
  4783.3     .09       0  4990.2     .05       0  5009.8     .09       0
Bank Sta=4990.2,5009.8
Exp/Cntr=0.3,0.1

Type RM Length L Ch R = 1 ,21500   ,584,584,584
BEGIN DESCRIPTION:
South Double Creek 44.0
END DESCRIPTION:
XS GIS Cut Line= 3
      1609045.05       974426.34       1609180.8        974178.9
       1609326.8       973997.99
#Sta/Elev= 30
  4717.8  869.82  4743.2  866.36  4757.7  863.46  4781.5  854.83  4798.2  847.07
  4813.4   841.4  4817.2  838.29  4834.2  827.53  4844.8  821.49  4868.3  817.83
  4899.9   815.9  4966.2  813.37  4990.2  809.87  4991.7  806.87  5008.3  806.87
  5009.8  809.87  5030.9  810.37  5047.1  814.14  5053.4   816.5  5065.9  819.95
  5071.2  822.66  5085.2  827.86  5104.3  833.43  5127.9  836.66  5138.2  836.69
  5151.4  844.62  5174.9  854.43  5177.7  856.56    5221  872.65  5232.5  878.31
#Mann= 3 ,-1 , 0
  4717.8     .09       0  4990.2     .05       0  5009.8     .09       0
Bank Sta=4990.2,5009.8
Exp/Cntr=0.3,0.1

Type RM Length L Ch R = 1 ,20916   ,625,625,625
BEGIN DESCRIPTION:
South Double Creek 43.0
END DESCRIPTION:
XS GIS Cut Line= 4
      1609161.87       974760.77      1609432.17        974680.6
       1609498.6       974614.17      1609617.71       974183.53
#Sta/Elev= 30
  4682.1  868.55  4736.9   855.8  4781.2  846.09  4805.9  839.37  4855.1  829.27
    4889  823.06  4911.6  817.65    4990  809.48  4990.2  806.59  4991.7  803.59
  5008.3  803.59  5009.8  806.59  5063.7  811.16  5109.3  812.39  5166.2  812.62
  5200.8  811.96  5225.7  813.51  5239.4  812.93  5265.8  813.65  5282.5  812.76
  5297.1  812.84  5354.3  815.35  5388.3  819.56  5399.2  822.31  5419.7  829.12
  5436.4  835.94  5448.4  842.96  5461.2  849.45  5493.9  863.05  5504.8     864
#Mann= 3 ,-1 , 0
  4682.1     .09       0  4990.2     .05       0  5009.8     .09       0
Bank Sta=4990.2,5009.8
Exp/Cntr=0.3,0.1

Type RM Length L Ch R = 1 ,20291   ,788,788,788
BEGIN DESCRIPTION:
South Double Creek 42.0
END DESCRIPTION:
XS GIS Cut Line= 4
      1609933.82       975173.09      1610000.25       974747.03
      1610007.12       974694.34      1609920.08       974440.08
#Sta/Elev= 30
  4549.2  872.64  4555.8  871.67  4593.4  861.19  4603.1   859.9  4687.6  835.47
  4729.6  824.98  4769.7  817.51  4774.6  816.36  4808.7  813.84  4951.2  809.96
  4955.9  809.82  4975.8  805.92  4990.2  800.32  4991.7  797.32  5008.3  797.32
  5009.8  800.32  5011.2  804.19    5038  807.52  5051.9  807.11    5066  809.09
  5095.3  809.45    5118  810.95  5143.6  815.29  5153.4     816  5167.6  820.86
    5212  838.68  5229.6  846.62  5253.5  855.25  5287.4  864.52  5302.3   867.1
#Mann= 5 ,-1 , 0
  4549.2     .09       0  4769.7    .035       0  4951.2     .09       0
  4990.2     .05       0  5009.8     .09       0
Bank Sta=4990.2,5009.8
Exp/Cntr=0.3,0.1

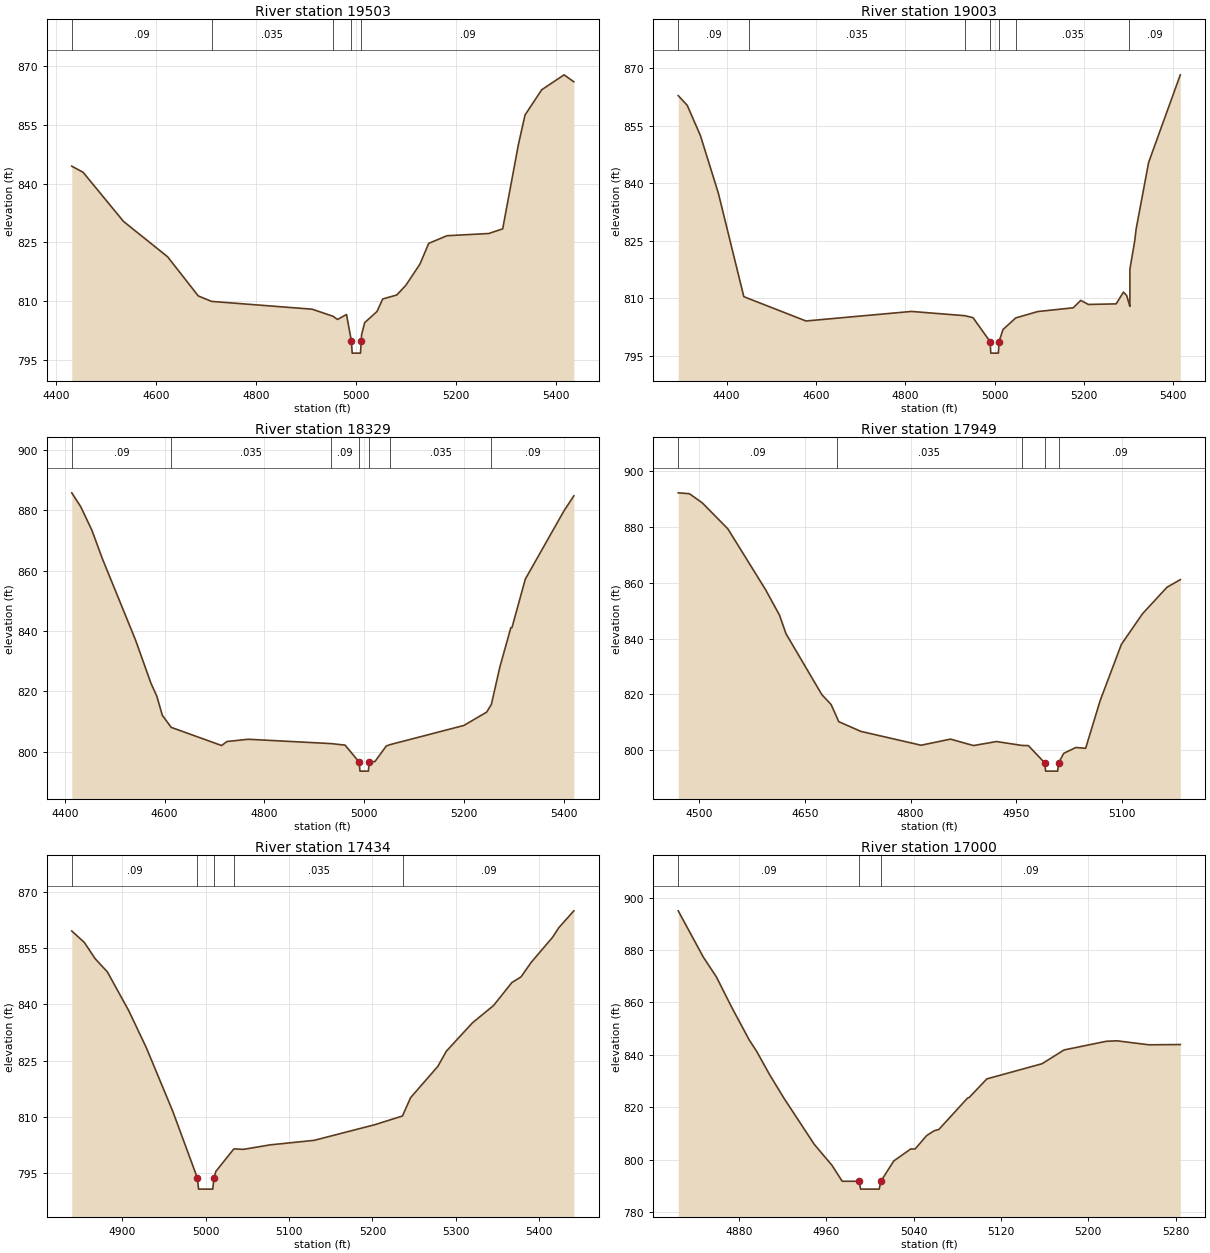
Type RM Length L Ch R = 1 ,19503   ,500,500,500
BEGIN DESCRIPTION:
South Double Creek 40.0
END DESCRIPTION:
XS GIS Cut Line= 5
        1610625.         975175.      1610751.58       974813.46
      1610781.35       974689.76      1610776.77       974506.51
      1610650.79       974222.47
#Sta/Elev= 30
  4430.8  844.42  4453.4  842.87  4534.4  830.31  4622.4  821.32  4683.9  811.31
  4710.5  809.92  4911.6  807.93  4953.3  806.13  4962.4  805.31  4980.4  806.57
  4990.2  799.72  4991.7  796.72  5008.3  796.72  5009.8  799.72  5010.5  801.39
  5016.7   804.5  5041.4  807.35  5052.8  810.54    5081  811.56    5099  814.02
  5127.2  819.42  5144.8  824.73  5181.5  826.68    5265  827.24  5292.8  828.44
  5324.2  849.94  5337.5  857.49  5370.8  863.91  5415.6  867.73  5435.1  865.95
#Mann= 5 ,-1 , 0
  4430.8     .09       0  4710.5    .035       0  4953.3     .09       0
  4990.2     .05       0  5009.8     .09       0
Bank Sta=4990.2,5009.8
Exp/Cntr=0.3,0.1

Type RM Length L Ch R = 1 ,19003   ,674,674,674
BEGIN DESCRIPTION:
South Double Creek 39.0
END DESCRIPTION:
XS GIS Cut Line= 5
      1610714.08       975224.06      1611228.55       974811.04
      1611274.44       974666.12      1611305.84       974540.53
       1611221.3        974378.7
#Sta/Elev= 30
  4291.9  862.85  4311.9  860.35  4341.6  852.42  4381.7   837.4  4438.7   810.4
    4450  809.87  4577.8  804.05  4813.9  806.54  4933.4  805.43  4951.7  804.92
    4990  798.66  4991.5  795.66  5008.5  795.66    5010  798.66  5018.8  801.81
  5047.2  804.84  5096.6  806.51    5176  807.49  5192.8  809.42    5210  808.36
  5272.1  808.51  5288.4  811.58  5295.6  810.71  5301.3  808.45  5302.8  807.86
  5302.9  817.57  5313.6   824.9  5316.9  828.08  5344.8  845.43  5415.7  868.28
#Mann= 7 ,-1 , 0
  4291.9     .09       0    4450    .035       0  4933.4     .09       0
    4990     .05       0    5010     .09       0  5047.2    .035       0
  5301.3     .09       0
Bank Sta=4990,5010
Exp/Cntr=0.3,0.1

Type RM Length L Ch R = 1 ,18329   ,380,380,380
BEGIN DESCRIPTION:
South Double Creek 38.0
END DESCRIPTION:
XS GIS Cut Line= 4
      1610815.53       975407.63      1611313.08       975224.06
      1611431.44       975170.93      1611723.69       974984.95
#Sta/Elev= 30
  4413.8  885.85    4432  881.18  4454.1  873.46  4475.2  863.99  4541.7     837
  4572.6  822.66  4584.2  818.45  4595.3  812.09  4613.1  808.06  4714.2  802.03
  4724.9  803.36  4767.6  804.11    4934  802.67  4961.7  802.17    4990  796.54
  4991.5  793.54  5008.5  793.54    5010  796.54  5021.6  796.73  5044.2  801.85
  5051.2   802.3  5199.9  808.69  5245.6  813.12    5255  815.69    5272  828.09
    5294  841.11  5296.3  841.16    5323  857.23  5400.7  879.92  5420.3  884.85
#Mann= 7 ,-1 , 0
  4413.8     .09       0  4613.1    .035       0    4934     .09       0
    4990     .05       0    5010     .09       0  5051.2    .035       0
    5255     .09       0
Bank Sta=4990,5010
Exp/Cntr=0.3,0.1

Type RM Length L Ch R = 1 ,17949   ,515,515,515
BEGIN DESCRIPTION:
South Double Creek 37.0
END DESCRIPTION:
XS GIS Cut Line= 3
        1610775.         975475.      1611296.18       975569.46
      1611460.42       975649.16
#Sta/Elev= 30
  4470.3  892.14  4486.2  891.82  4504.6  888.51  4540.7  879.24  4594.2  857.48
    4614  848.34  4623.1  841.74  4674.1  819.88  4687.2  816.37  4695.4  811.74
    4698  810.23  4729.3  806.76  4814.8   801.8  4856.5  803.99  4889.1  801.68
  4921.8  803.12  4957.4  801.74    4967  801.66    4990  795.53  4991.5  792.53
  5008.5  792.53    5010  795.53  5017.1  798.89  5034.3  800.99  5048.2   800.7
  5068.8  817.77  5098.9   837.9  5128.9  848.87  5163.5  858.32  5182.5  861.07
#Mann= 5 ,-1 , 0
  4470.3     .09       0  4695.4    .035       0  4957.4     .09       0
    4990     .05       0    5010     .09       0
Bank Sta=4990,5010
Exp/Cntr=0.3,0.1

Type RM Length L Ch R = 1 ,17434   ,434,434,434
BEGIN DESCRIPTION:
South Double Creek 36.0
END DESCRIPTION:
XS GIS Cut Line= 5
      1610970.11       976117.74      1611057.06       976042.86
       1611146.3       976013.44      1611407.28       975994.55
      1611465.25        975876.2
#Sta/Elev= 30
  4839.4  859.56  4854.5  856.51  4867.4   852.2  4882.1  848.66  4907.7  838.35
  4928.9  828.42  4960.6  811.48    4990  793.76  4991.5  790.76  5008.5  790.76
    5010  793.76  5012.2  795.48  5033.8  801.48  5045.3  801.36  5077.1  802.55
  5130.3  803.77    5203  807.94  5236.1  810.26    5237  810.75  5245.8  815.14
  5278.5  823.49  5288.7  827.53    5320  835.09  5345.3   839.7  5367.2  845.81
  5378.3  847.34  5390.3  851.17  5416.1  857.89  5423.5  860.43  5441.6  864.94
#Mann= 5 ,-1 , 0
  4839.4     .09       0    4990     .05       0    5010     .09       0
  5033.8    .035       0    5237     .09       0
Bank Sta=4990,5010
Exp/Cntr=0.3,0.1

Type RM Length L Ch R = 1 ,17000   ,500,500,500
BEGIN DESCRIPTION:
South Double Creek 35.0
END DESCRIPTION:
XS GIS Cut Line= 3
       1611378.3       976465.54      1611406.62       976292.27
      1611474.91       976016.29
#Sta/Elev= 30
  4824.4  894.96  4847.4  877.28  4859.4  869.71  4873.3  858.21  4889.4   845.7
  4896.2  841.35  4908.2  832.36  4921.2  823.47    4949  805.83  4965.2  797.84
  4974.6  791.73    4990  791.73  4991.5  788.73  5008.5  788.73    5010  791.73
  5021.8  799.47  5037.3  804.05  5041.4  804.06    5052   809.2  5059.1  811.06
  5063.1  811.49  5089.3  823.44    5091  823.74  5107.1  830.81  5157.6  836.59
  5177.8  841.85  5216.5  845.16  5226.2  845.35  5255.6  843.82  5284.3  843.92
#Mann= 3 ,-1 , 0
  4824.4     .09       0    4990     .05       0    5010     .09       0
Bank Sta=4990,5010
Exp/Cntr=0.3,0.1

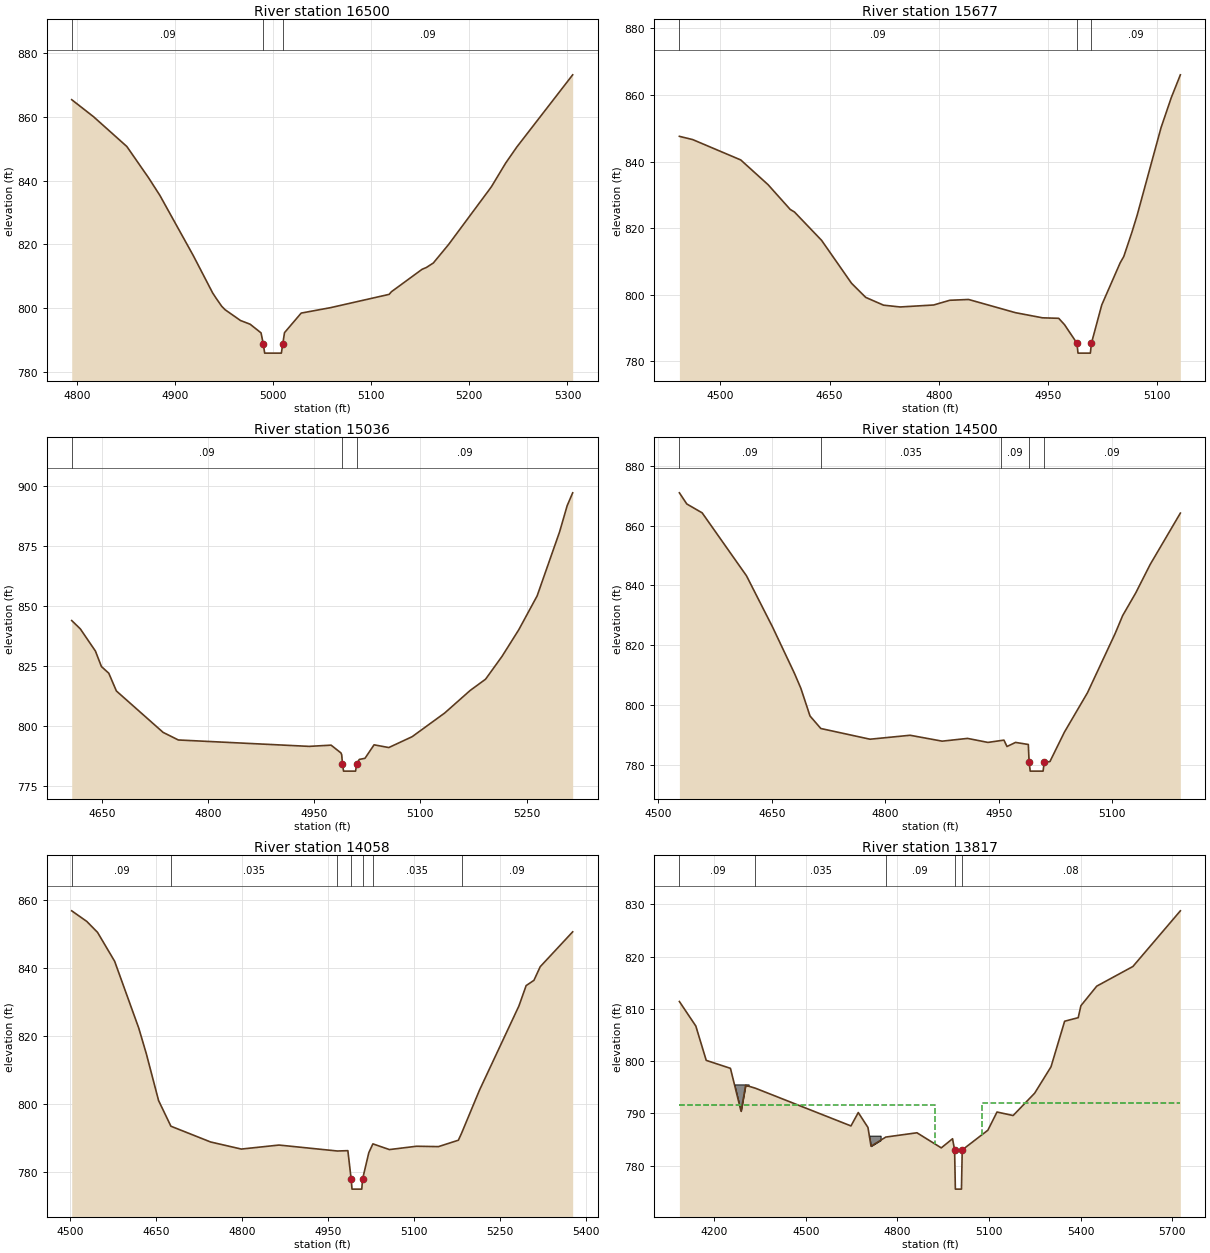
Type RM Length L Ch R = 1 ,16500   ,823,823,823
BEGIN DESCRIPTION:
South Double Creek 34.0
END DESCRIPTION:
XS GIS Cut Line= 3
       1611945.9       976195.03      1611820.06       976033.08
       1611583.6       975839.97
#Sta/Elev= 30
  4794.9  865.44  4817.1   860.1  4851.1  850.72  4873.3  840.86  4884.7  835.39
  4918.8  816.44  4938.5  804.73  4941.9  803.13  4947.7  800.55  4951.2  799.45
  4966.9  796.06  4976.7   794.9  4987.8  792.18    4990  788.82  4991.5  785.82
  5008.5  785.82    5010  788.82  5011.7  792.25  5028.7   798.4  5058.7  800.11
  5118.3  804.28  5120.6   805.1  5151.8  812.14  5156.2  812.72  5163.3  814.13
  5178.9  819.95  5222.4  838.04  5237.1  845.56  5248.4  850.58  5305.3  873.25
#Mann= 3 ,-1 , 0
  4794.9     .09       0    4990     .05       0    5010     .09       0
Bank Sta=4990,5010
Exp/Cntr=0.3,0.1

Type RM Length L Ch R = 1 ,15677   ,641,641,641
BEGIN DESCRIPTION:
South Double Creek 32.0
END DESCRIPTION:
XS GIS Cut Line= 5
      1612337.18       976016.29      1612356.51        975859.3
      1612288.88       975750.61      1612141.54       975525.98
      1612095.65       975400.38
#Sta/Elev= 30
  4443.6   847.6  4461.9  846.62  4527.9  840.51  4565.4  833.09  4595.9  825.64
  4601.8  824.86  4639.1  816.33  4680.2  803.45  4699.7  799.21  4724.2  796.87
    4747  796.33    4793  796.92  4815.3  798.34  4841.1  798.58  4905.6  794.61
  4942.7  793.07    4965  792.92    4973     791    4990  785.46  4991.5  782.46
  5008.5  782.46    5010  785.46  5024.1  796.91  5049.4  809.57  5054.4  811.48
  5065.6  818.78  5072.9  823.98  5105.6  850.18  5119.7  859.22  5132.2  866.08
#Mann= 3 ,-1 , 0
  4443.6     .09       0    4990     .05       0    5010     .09       0
Bank Sta=4990,5010
Exp/Cntr=0.3,0.1

Type RM Length L Ch R = 1 ,15036   ,536,536,536
BEGIN DESCRIPTION:
South Double Creek 31.0
END DESCRIPTION:
XS GIS Cut Line= 4
      1612358.92       976016.29      1612552.15       975989.72
      1612687.41        975844.8      1612912.03       975625.01
#Sta/Elev= 30
  4607.6  843.88  4619.7  840.43  4641.1  831.15  4649.6  824.69    4660   821.9
  4670.7  814.51  4736.7  797.24  4758.2  794.08  4942.9  791.41  4973.9  791.92
  4987.8  788.69  4988.9  787.94    4990  784.09  4991.5  781.09  5008.5  781.09
    5010  784.09  5013.7  785.96  5021.8  786.44  5034.6  792.06  5055.4  790.92
  5088.4  795.45  5134.3  805.31  5170.3  814.72  5192.1  819.43  5215.3  828.94
  5238.9     840  5264.9  854.16  5296.7  880.95  5307.3  891.77  5315.1  897.14
#Mann= 3 ,-1 , 0
  4607.6     .09       0    4990     .05       0    5010     .09       0
Bank Sta=4990,5010
Exp/Cntr=0.3,0.1

Type RM Length L Ch R = 1 ,14500   ,442,442,442
BEGIN DESCRIPTION:
South Double Creek 30.0
END DESCRIPTION:
XS GIS Cut Line= 3
      1612399.98       976356.85       1612868.5       976298.95
      1613052.12       976250.58
#Sta/Elev= 30
  4527.9  870.94  4537.7  867.21    4558  864.24  4616.6  843.18  4650.9  826.12
    4680  810.55  4688.4  805.59  4700.5  796.32  4714.8  792.14  4779.8  788.56
  4832.8  789.88  4875.1  787.91  4908.7  788.83  4935.6  787.49 4956.76  788.26
 4960.82  786.12 4972.08  787.49    4989   786.8    4990  780.89  4991.5  777.89
  5008.5  777.89    5010  780.89  5017.5  781.07  5036.7  790.94  5067.1  804.07
  5103.7  823.89  5113.7  829.92  5130.9  837.46    5150  846.98  5189.9  864.16
#Mann= 5 ,-1 , 0
  4527.9     .09       0  4714.8    .035       0  4952.7     .09       0
    4990     .05       0    5010     .09       0
Bank Sta=4990,5010
Exp/Cntr=0.3,0.1

Type RM Length L Ch R = 1 ,14058   ,241,241,241
BEGIN DESCRIPTION:
South Double Creek 29.0
END DESCRIPTION:
XS GIS Cut Line= 4
      1612421.72       976658.77       1612844.4       976736.06
      1612960.34       976731.23      1613250.18       976579.06
#Sta/Elev= 30
    4503  856.89  4529.2  853.78    4548  850.55  4577.8  842.04  4619.9  822.32
  4633.1  814.76  4654.4  801.01  4675.9  793.45    4745  788.81  4798.6  786.72
  4864.3   787.9  4966.1  786.15  4984.3  786.25    4990  777.92  4991.5  774.92
  5008.5  774.92    5010  777.92  5020.8  785.66  5027.9  788.25  5056.7  786.57
    5104  787.55  5142.2  787.44  5176.9  789.33  5182.6  791.44  5213.7  804.08
  5282.4  828.87    5295  834.87  5308.6  836.42  5319.5  840.43  5376.1   850.7
#Mann= 7 ,-1 , 0
    4503     .09       0  4675.9    .035       0  4966.1     .09       0
    4990     .05       0    5010     .09       0  5027.9    .035       0
  5182.6     .09       0
Bank Sta=4990,5010
Exp/Cntr=0.5,0.3

Type RM Length L Ch R = 1 ,13817   ,111,111,111
BEGIN DESCRIPTION:
Keaton Rd. SR-1479 - US
END DESCRIPTION:
XS GIS Cut Line= 6
      1612121.78       977322.48      1612328.92       977183.54
       1612887.2       976986.51      1613280.17       976877.72
      1613523.79       976837.46      1613665.25       976867.78
#Sta/Elev= 30
  4086.1  811.39  4139.9   806.7    4174  800.13  4253.3  798.61    4288   790.4
    4303  795.37  4335.3   794.8  4648.1  787.59    4672  790.15  4703.8  787.29
  4713.7  783.71  4762.2  785.46  4864.2  786.28  4943.9  783.39  4980.8  785.14
  4987.5     783    4990   775.5    5010   775.5  5012.5     783  5096.5  786.77
  5126.4  790.25  5179.2  789.58  5249.7  793.85  5303.3   798.9  5347.9  807.62
  5392.4   808.3  5401.2  810.59  5453.1  814.33  5571.5  818.09    5727  828.74
#Mann= 5 ,-1 , 0
  4086.1     .09       0  4335.3    .035       0  4762.2     .09       0
  4987.5     .05       0  5012.5     .08       0
#XS Ineff= 2 , 0
       0    4922  791.68  5076.4       0  791.93
Permanent Ineff=
       F       F
#Block Obstruct= 2 ,-1
  4251.1  4312.8  795.53  4677.8  4745.1  785.73
Bank Sta=4987.5,5012.5
Exp/Cntr=0.5,0.3