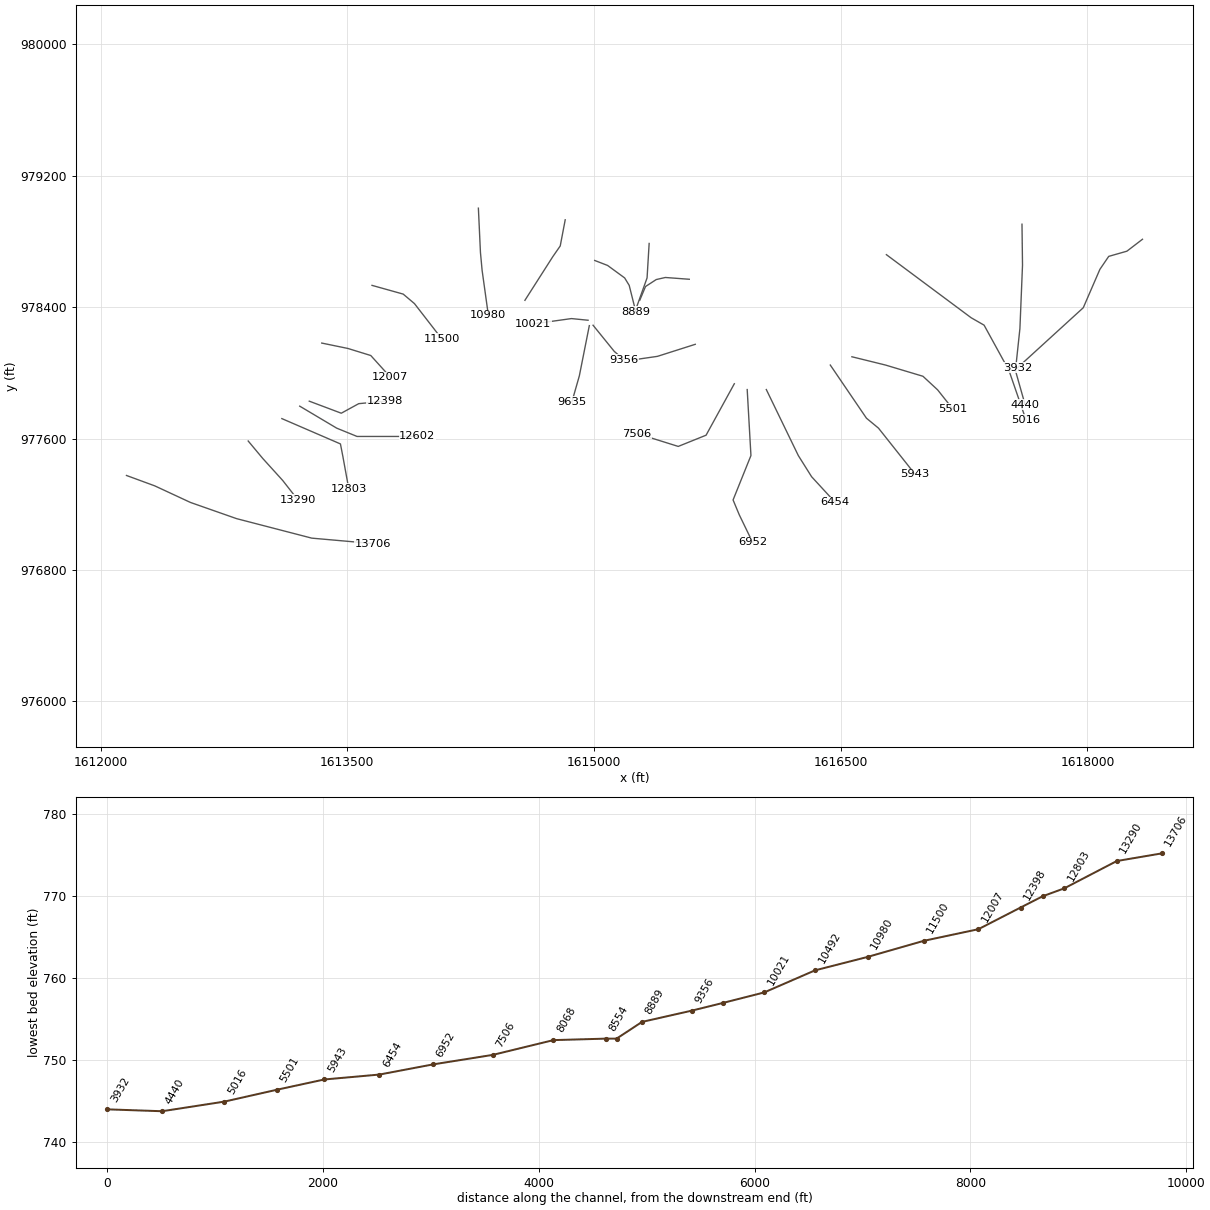
HEC-RAS study lds_south_double_crk.prj: South Double Creek Limited Detail Study

--- lds_south_double_crk.g01 (geometry) --- (continued)

Type RM Length L Ch R = 3 ,13753   ,,,
BEGIN DESCRIPTION:
Keaton Rd. SR-1479
Structure ID: Keaton Rd
Approximate Survey Structure
END DESCRIPTION:
Bridge Culvert--1,0,-1,-1, 0
Deck Dist Width WeirC Skew NumUp NumDn MinLoCord MaxHiCord MaxSubmerge Is_Ogee
52,24,3,0, 60, 60, , , , 0, 1,1,,
  4129.6  4164.8  4176.4  4194.8  4215.8  4242.4  4246.4  4255.6  4263.5  4314.8
  4321.7  4346.7  4367.3  4374.8  4409.3    4432  4439.2  4473.4  4537.4  4546.2
  4559.9  4606.8    4616  4630.5  4640.6  4679.1    4940    4940    5060    5060
  5124.1    5153  5187.3  5235.9  5267.4  5276.5  5285.4  5300.1  5306.4  5315.9
  5324.2    5330  5342.8  5369.3  5386.8  5396.3  5408.9  5416.9  5430.3  5459.9
  5482.3  5495.3  5504.3  5544.3  5559.3  5564.2  5578.4  5610.7  5628.3  5639.5
   811.8  808.71  808.03  806.61  805.28   804.3  803.95  803.66  803.11  801.81
  801.77  800.97  800.79  800.23  799.41  799.21  798.79  797.89  795.75  795.74
  795.17  794.04  793.28  792.94  792.92     792     792     792     792     792
     792  793.28  795.66   799.8  802.88  803.57  804.61   805.9  806.64   807.4
  808.33  809.21  810.27  812.87  814.63  815.87  816.82  817.86  819.07  822.23
  824.07   824.9  825.98  828.62  829.39  829.99  831.09  833.05  834.71  835.45
   755.5   755.5   755.5   755.5   755.5   755.5   755.5   755.5   755.5   755.5
   755.5   755.5   755.5   755.5   755.5   755.5   755.5   755.5   755.5   755.5
   755.5   755.5   755.5   755.5   755.5   755.5   755.5     790     790   755.5
   755.5   755.5   755.5   755.5   755.5   755.5   755.5   755.5   755.5   755.5
   755.5   755.5   755.5   755.5   755.5   755.5   755.5   755.5   755.5   755.5
   755.5   755.5   755.5   755.5   755.5   755.5   755.5   755.5   755.5   755.5
  4129.6  4164.8  4176.4  4194.8  4215.8  4242.4  4246.4  4255.6  4263.5  4314.8
  4321.7  4346.7  4367.3  4374.8  4409.3    4432  4439.2  4473.4  4537.4  4546.2
  4559.9  4606.8    4616  4630.5  4640.6  4679.1    4940    4940    5060    5060
  5124.1    5153  5187.3  5235.9  5267.4  5276.5  5285.4  5300.1  5306.4  5315.9
  5324.2    5330  5342.8  5369.3  5386.8  5396.3  5408.9  5416.9  5430.3  5459.9
  5482.3  5495.3  5504.3  5544.3  5559.3  5564.2  5578.4  5610.7  5628.3  5639.5
   811.8  808.71  808.03  806.61  805.28   804.3  803.95  803.66  803.11  801.81
  801.77  800.97  800.79  800.23  799.41  799.21  798.79  797.89  795.75  795.74
  795.17  794.04  793.28  792.94  792.92     792     792     792     792     792
     792  793.28  795.66   799.8  802.88  803.57  804.61   805.9  806.64   807.4
  808.33  809.21  810.27  812.87  814.63  815.87  816.82  817.86  819.07  822.23
  824.07   824.9  825.98  828.62  829.39  829.99  831.09  833.05  834.71  835.45
   755.5   755.5   755.5   755.5   755.5   755.5   755.5   755.5   755.5   755.5
   755.5   755.5   755.5   755.5   755.5   755.5   755.5   755.5   755.5   755.5
   755.5   755.5   755.5   755.5   755.5   755.5   755.5     790     790   755.5
   755.5   755.5   755.5   755.5   755.5   755.5   755.5   755.5   755.5   755.5
   755.5   755.5   755.5   755.5   755.5   755.5   755.5   755.5   755.5   755.5
   755.5   755.5   755.5   755.5   755.5   755.5   755.5   755.5   755.5   755.5
Pier Skew, UpSta & Num, DnSta & Num=  ,4970, 2 ,4970, 2 , 0 , 0 , 0 ,0,0
       2       2
  784.68     790
       2       2
  784.14     790
Pier Skew, UpSta & Num, DnSta & Num=  ,5030, 2 ,5030, 2 , 0 , 0 , 0 ,0,0
       2       2
  784.99     790
       2       2
  783.64     790
Abutment Skew #Up #Dn= , 2 , 2
    4940    4950
     790  783.76
    4940    4950
     790  784.61
Abutment Skew #Up #Dn= , 2 , 2
    5050    5060
  784.49     790
    5050    5060
  785.67     790
BR Coef= 1 , 1 , 0 ,1.25, 0 ,,,0.8,0,2,0,
WSPro=,,,, 1 ,,,, 0 ,,,, 0 ,,,,-1 ,-1 ,-1 , 0 , 0 , 0 , 0 , 0
BC Design=,, 0 ,, 0 ,,,,,,
BC HTab HWMax=828.74

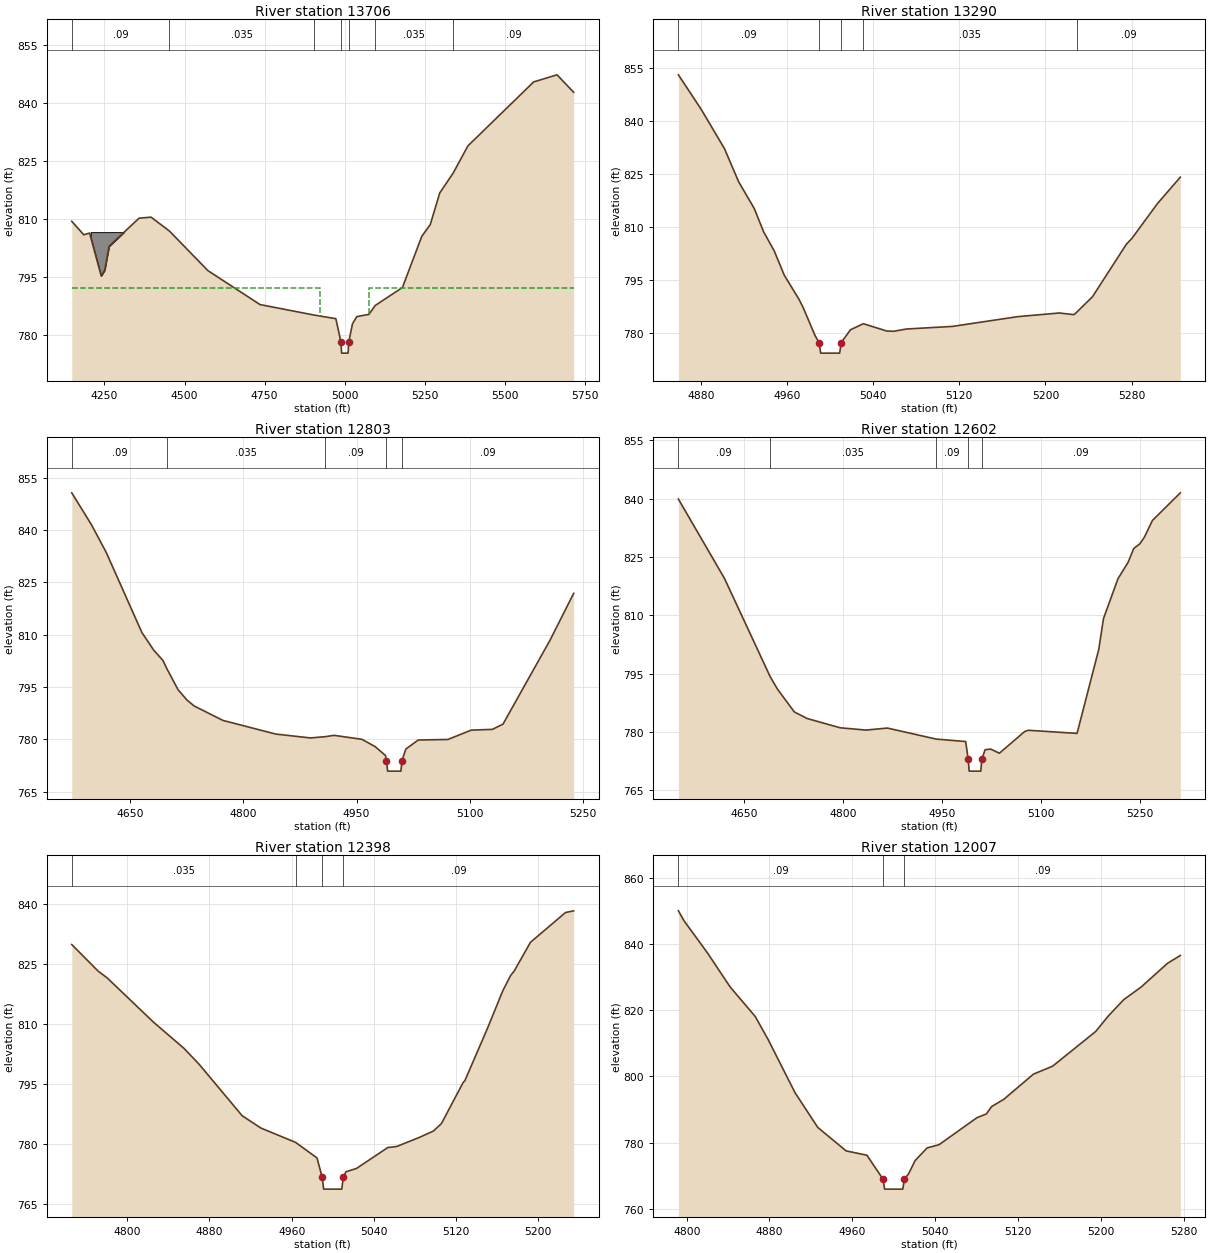
Type RM Length L Ch R = 1 ,13706   ,416,416,416
BEGIN DESCRIPTION:
Keaton Rd. SR-1479 - DS
END DESCRIPTION:
XS GIS Cut Line= 6
      1612157.15       977375.53      1612328.92       977312.38
      1612546.17       977211.33      1612826.57       977112.81
       1613283.8       976994.08      1613655.15       976961.24
#Sta/Elev= 30
  4148.4   809.3    4186  805.81    4204  806.26  4240.2  795.17  4251.1  796.64
  4264.9  802.85  4358.3  810.11  4395.8  810.37    4453  806.78    4573  796.54
  4735.5  787.76  4904.6  785.04  4971.9  784.12  4987.5   778.2    4990   775.2
    5010   775.2  5012.5   778.2  5023.8  782.77  5037.2  784.65 5075.17  785.22
  5094.7  787.52  5179.6  792.18  5239.8  805.38  5266.4  808.46    5296  816.64
  5337.7  821.76  5383.8  828.81  5588.9  845.36  5661.7  847.19  5713.6  842.68
#Mann= 7 ,-1 , 0
  4148.4     .09       0    4453    .035       0  4904.6     .09       0
  4987.5     .05       0  5012.5     .09       0  5094.7    .035       0
  5337.7     .09       0
#XS Ineff= 2 , 0
       0  4922.1     792  5075.2       0     792
Permanent Ineff=
       F       F
#Block Obstruct= 1 ,-1
  4207.5  4315.7   806.5
Bank Sta=4987.5,5012.5
Exp/Cntr=0.5,0.3

Type RM Length L Ch R = 1 ,13290   ,487,487,487
BEGIN DESCRIPTION:
South Double Creek 28.0
END DESCRIPTION:
XS GIS Cut Line= 4
       1612897.3        977585.2      1612985.72        977479.1
      1613106.97       977345.22      1613197.92       977229.01
#Sta/Elev= 30
    4859  853.18  4880.2  843.38  4901.8  832.25  4914.9   822.9  4929.5  815.26
  4938.2  808.64  4947.9  803.33  4957.4  796.34  4971.1   789.5    4975  787.12
  4986.1  779.15  4989.7  777.27  4991.2  774.27  5008.8  774.27  5010.3  777.27
  5018.8  780.88  5030.8  782.61  5052.6  780.54  5058.8  780.46  5070.9  781.11
  5113.4  781.84  5174.4  784.62  5212.9  785.65  5226.5  785.18    5229  785.86
  5243.7  790.26  5275.1  805.11  5280.5  806.87  5303.9  816.62  5325.3  824.16
#Mann= 5 ,-1 , 0
    4859     .09       0  4989.7     .05       0  5010.3     .09       0
  5030.8    .035       0    5229     .09       0
Bank Sta=4989.7,5010.3
Exp/Cntr=0.3,0.1

Type RM Length L Ch R = 1 ,12803   ,201,201,201
BEGIN DESCRIPTION:
South Double Creek 27.0
END DESCRIPTION:
XS GIS Cut Line= 4
      1613101.92       977721.61      1613458.11       977567.52
      1613473.27       977489.21      1613508.63       977294.69
#Sta/Elev= 30
  4572.4  850.65  4598.5  841.52  4618.1  833.59  4665.4  810.64  4681.3  805.53
  4693.3  802.64  4698.6  800.25  4713.3  794.28    4725  791.34  4734.6  789.61
  4772.8  785.47    4843  781.55  4888.8  780.45  4908.5  780.81  4920.2  781.19
  4957.1  780.05  4974.7  777.96  4988.4  775.41  4989.7  773.94  4991.2  770.94
  5008.8  770.94  5010.3  773.94  5015.3  777.25  5031.8  779.85  5071.2  780.01
    5102  782.68  5130.1   782.9  5144.2   784.4  5206.6  808.46  5237.9  821.86
#Mann= 5 ,-1 , 0
  4572.4     .09       0  4698.6    .035       0  4908.5     .09       0
  4989.7     .05       0  5010.3     .09       0
Bank Sta=4989.7,5010.3
Exp/Cntr=0.3,0.1

Type RM Length L Ch R = 1 ,12602   ,204,204,204
BEGIN DESCRIPTION:
South Double Creek 26.5
END DESCRIPTION:
XS GIS Cut Line= 5
      1613210.55        977797.4      1613435.37       977663.51
      1613559.15       977612.99      1613698.09       977612.99
      1613925.44       977612.99
#Sta/Elev= 30
  4549.9   839.9  4619.9  819.48  4689.2  794.24  4700.2  791.06  4725.8  785.19
  4745.2   783.5  4795.5  781.11  4834.7  780.52    4867  781.04    4941  778.21
  4985.9  777.58  4989.7  772.97  4991.2  769.97  5008.8  769.97  5010.3  772.97
  5015.3  775.47  5023.9  775.64    5037  774.57  5075.4  780.15  5080.9  780.47
  5154.9  779.67  5187.8  801.24    5195  809.18  5216.9   819.4  5232.3  823.63
  5240.9  827.19  5250.2  828.41  5256.9  830.06  5269.3  834.41  5311.6  841.51
#Mann= 5 ,-1 , 0
  4549.9     .09       0  4689.2    .035       0    4941     .09       0
  4989.7     .05       0  5010.3     .09       0
Bank Sta=4989.7,5010.3
Exp/Cntr=0.3,0.1

Type RM Length L Ch R = 1 ,12398   ,391,391,391
BEGIN DESCRIPTION:
South Double Creek 26.0
END DESCRIPTION:
XS GIS Cut Line= 4
      1613268.65       977827.71      1613463.16       977754.45
      1613569.26       977812.55      1613728.41       977827.71
#Sta/Elev= 30
  4745.9  829.86  4771.7  823.18  4780.3  821.53  4825.5  810.42    4855   803.9
  4869.7  799.94  4911.8  786.99  4929.9  783.92  4963.9   780.3  4984.7  776.41
  4989.7   771.6  4991.2   768.6  5008.8   768.6  5010.3   771.6  5012.9  772.95
  5023.2  773.79  5053.7  779.03  5062.3  779.28    5084  781.52  5098.1  783.16
  5105.9  785.04    5127  795.32  5128.6  795.73  5150.8  808.95  5165.5  818.24
  5173.2  822.11  5176.7  823.23  5192.6  830.45  5226.7  837.89  5234.6  838.31
#Mann= 4 ,-1 , 0
  4745.9    .035       0  4963.9     .09       0  4989.7     .05       0
  5010.3     .09       0
Bank Sta=4989.7,5010.3
Exp/Cntr=0.3,0.1

Type RM Length L Ch R = 1 ,12007   ,507,507,507
BEGIN DESCRIPTION:
South Double Creek 25.0
END DESCRIPTION:
XS GIS Cut Line= 4
      1613344.43       978181.37      1613503.58       978148.53
      1613642.52       978105.59      1613761.25       977974.23
#Sta/Elev= 30
    4792  849.96  4797.6  846.88    4820   837.3    4842  826.98  4866.2  818.08
  4878.4  811.28  4904.6  795.11  4926.6   784.6    4954   777.5  4974.1   776.2
  4989.7  768.96  4991.2  765.96  5008.8  765.96  5010.3  768.96  5014.3  770.54
  5020.8  774.62  5032.3   778.4  5043.8  779.37  5080.4  787.52  5089.5  788.65
  5094.6  790.88  5106.5   793.1    5135  800.67  5153.5  803.06  5195.1  813.53
  5207.6  818.32  5222.4  823.19  5238.9  826.92  5264.5  834.11  5276.9  836.49
#Mann= 3 ,-1 , 0
    4792     .09       0  4989.7     .05       0  5010.3     .09       0
Bank Sta=4989.7,5010.3
Exp/Cntr=0.3,0.1

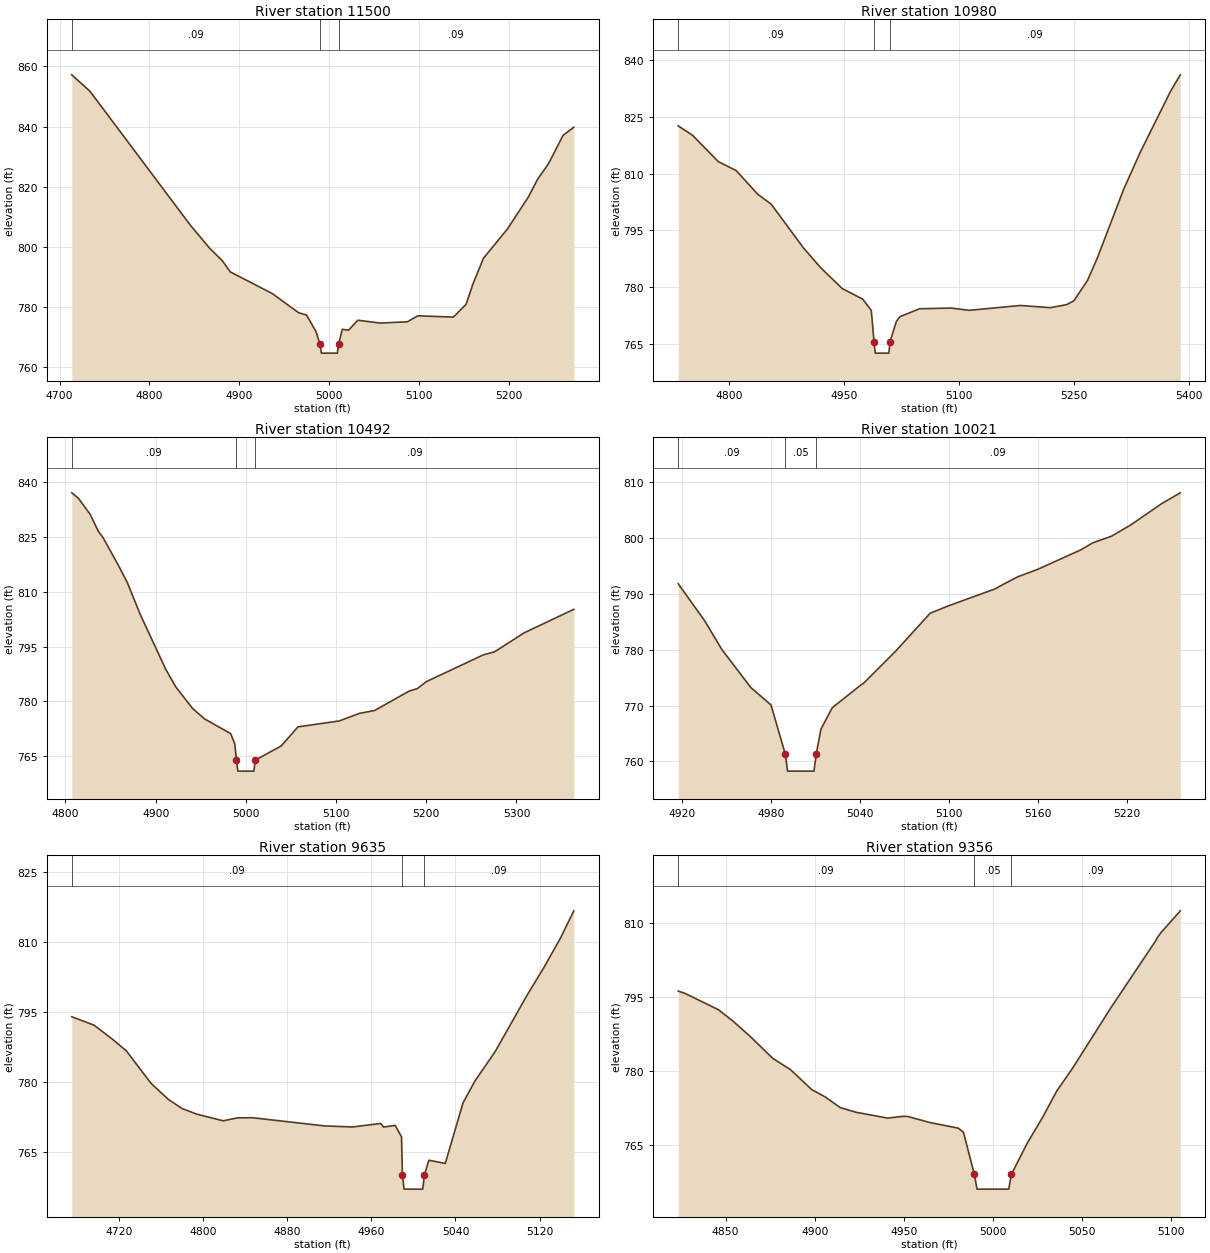
Type RM Length L Ch R = 1 ,11500   ,520,520,520
BEGIN DESCRIPTION:
South Double Creek 24.0
END DESCRIPTION:
XS GIS Cut Line= 4
       1613650.1        978532.5      1613839.56       978479.45
      1613908.08       978421.61      1614074.49       978206.63
#Sta/Elev= 30
  4713.6  857.21  4733.9  851.71  4845.5  807.13    4867  799.45  4880.9  795.35
  4889.9  791.59  4936.7  784.35  4965.8     778  4974.7  777.21  4985.1  771.77
  4989.6  767.54  4991.1  764.54  5008.9  764.54  5010.4  767.54  5014.4  772.48
  5021.3  772.16  5031.7  775.49  5056.5  774.55  5086.8  774.97  5098.3  776.96
    5138  776.54  5152.1  780.81  5159.4  787.35  5171.4  796.14    5198  805.86
  5221.3  816.51  5231.5  822.38  5243.9   827.7  5259.9  837.05  5271.9  839.77
#Mann= 3 ,-1 , 0
  4713.6     .09       0  4989.6     .05       0  5010.4     .09       0
Bank Sta=4989.6,5010.4
Exp/Cntr=0.3,0.1

Type RM Length L Ch R = 1 ,10980   ,488,488,488
BEGIN DESCRIPTION:
South Double Creek 23.0
END DESCRIPTION:
XS GIS Cut Line= 4
      1614296.79       979002.37      1614309.42       978732.07
      1614319.52       978623.44      1614357.41       978350.62
#Sta/Elev= 30
  4734.1  822.58  4752.8  820.09  4786.4  813.14  4809.7  810.78  4837.8  804.54
  4855.4  801.91  4897.2  790.44    4920  785.12  4948.1  779.63  4974.9  776.82
    4986  773.86  4989.6  765.58  4991.1  762.58  5008.9  762.58  5010.4  765.58
  5018.5  770.83  5023.1  772.18  5048.9  774.29  5090.3  774.48  5113.8  773.88
  5180.5  775.16  5219.8  774.58    5241  775.39  5250.2  776.37    5268  781.73
  5280.8  787.63  5315.4   805.9  5337.3  815.76  5376.7  831.81  5389.2  836.06
#Mann= 3 ,-1 , 0
  4734.1     .09       0  4989.6     .05       0  5010.4     .09       0
Bank Sta=4989.6,5010.4
Exp/Cntr=0.3,0.1

Type RM Length L Ch R = 1 ,10492   ,471,471,471
BEGIN DESCRIPTION:
South Double Creek 22.0
END DESCRIPTION:
XS GIS Cut Line= 4
      1614824.75       978931.63      1614794.44       978772.49
      1614748.97       978706.81      1614579.72       978441.56
#Sta/Elev= 30
    4807  837.07  4814.4  835.57  4827.4  831.19  4836.3  826.62  4841.8  824.77
  4859.3  816.96  4868.7  812.46  4882.9   803.8  4911.2   788.8  4922.2  784.03
  4941.1  778.03  4954.2  775.23  4983.2  771.19  4987.7   768.4  4989.6  763.94
  4991.1  760.94  5008.9  760.94  5010.4  763.94  5039.2  767.83  5057.8  773.05
  5103.4  774.66    5126  776.74  5142.8  777.53  5180.8  782.81  5190.1  783.52
  5200.2  785.44  5263.7  792.79  5275.7  793.57  5308.4  798.76  5363.6   805.2
#Mann= 3 ,-1 , 0
    4807     .09       0  4989.6     .05       0  5010.4     .09       0
Bank Sta=4989.6,5010.4
Exp/Cntr=0.3,0.1

Type RM Length L Ch R = 1 ,10021   ,386,386,386
BEGIN DESCRIPTION:
South Double Creek 21.0
END DESCRIPTION:
XS GIS Cut Line= 3
      1614963.69       978320.31      1614862.64       978330.41
      1614627.71       978297.57
#Sta/Elev= 28
  4917.3  791.83  4935.3  785.14  4946.7  780.06  4966.3  773.23  4979.9  770.11
  4989.6  761.25  4991.1  758.25  5008.9  758.25  5010.4  761.25  5013.6  765.78
  5021.3  769.63  5041.1   773.8  5042.1  773.92    5064  779.74  5065.4  780.17
    5066  780.33  5087.3  786.55  5099.3  787.84  5131.6  790.96  5133.3  791.25
  5146.4  793.08  5160.1  794.44  5188.9   797.9  5196.9  799.15  5209.6  800.35
  5222.3  802.31  5243.8  806.24  5256.1  808.13
#Mann= 3 ,-1 , 0
  4917.3     .09       0  4989.6     .05       0  5010.4     .09       0
Bank Sta=4989.6,5010.4
Exp/Cntr=0.3,0.1

Type RM Length L Ch R = 1 ,9635    ,279,279,279
BEGIN DESCRIPTION:
South Double Creek 20.0
END DESCRIPTION:
XS GIS Cut Line= 3
      1614971.27       978287.47      1614910.64        977981.8
      1614865.17       977822.66
#Sta/Elev= 30
  4675.3  793.94  4696.5  792.14  4714.3  789.06  4727.2  786.62  4750.5  779.69
    4767  776.23  4779.9  774.28    4794  773.05  4819.2  771.62  4832.9  772.25
    4847  772.28  4915.7  770.52  4942.4   770.3  4968.9  771.05  4971.6  770.27
  4982.7  770.64  4988.7  768.18  4989.6  759.96  4991.1  756.96  5008.9  756.96
  5010.4  759.96  5014.7  763.16  5030.3  762.48  5047.2  775.48  5058.4  780.12
  5077.8   786.5  5108.2  798.63  5123.7  804.37  5139.6  810.74  5152.5  816.67
#Mann= 3 ,-1 , 0
  4675.3     .09       0  4989.6     .05       0  5010.4     .09       0
Bank Sta=4989.6,5010.4
Exp/Cntr=0.3,0.1

Type RM Length L Ch R = 1 ,9356    ,467,467,467
BEGIN DESCRIPTION:
South Double Creek 19.5
END DESCRIPTION:
XS GIS Cut Line= 3
        1614994.       978289.99      1615122.84       978130.85
      1615180.94       978080.32
#Sta/Elev= 30
  4823.4   796.2  4827.2  795.73    4846  792.41  4854.2   790.1  4863.5   787.1
  4876.6  782.52  4886.4  780.28  4898.3  776.23  4905.8  774.76  4914.4  772.57
  4923.3  771.62    4941  770.45  4949.6  770.81  4952.2  770.78    4965  769.52
  4980.5  768.42  4983.5  767.58  4989.6  759.05  4991.1  756.05  5008.9  756.05
  5010.4  759.05  5019.5  765.51  5028.2  770.78  5035.8  775.91  5044.7  780.55
  5066.4  792.91  5091.6  806.52  5092.4  807.11  5094.7  808.19  5105.2  812.47
#Mann= 3 ,-1 , 0
  4823.4     .09       0  4989.6     .05       0  5010.4     .09       0
Bank Sta=4989.6,5010.4
Exp/Cntr=0.3,0.1

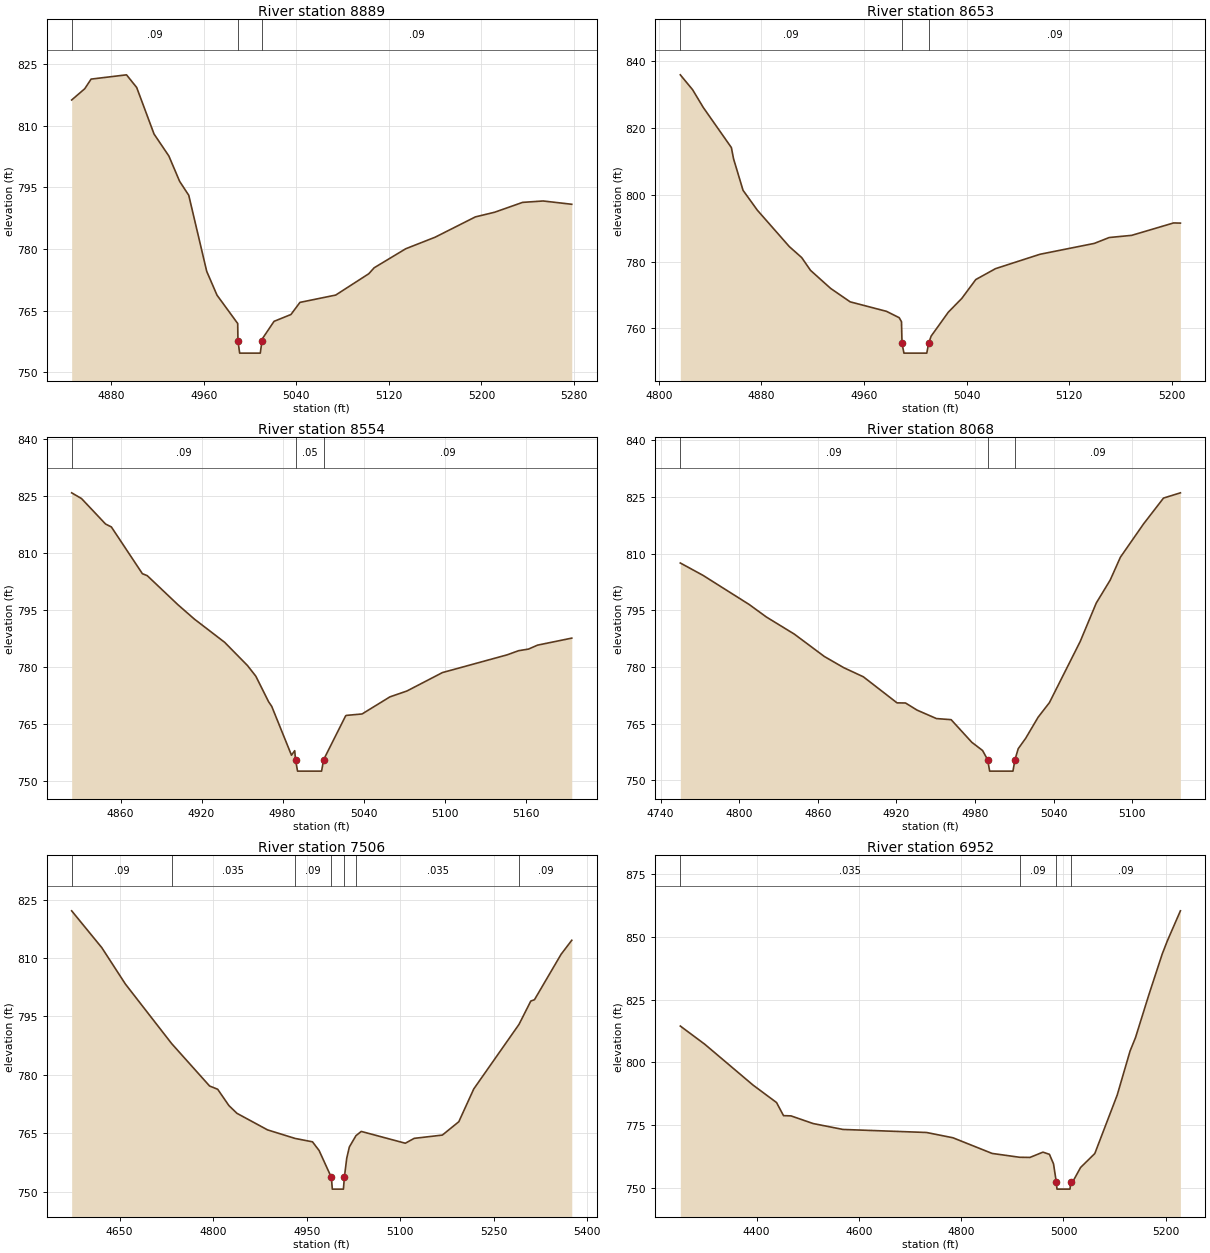
Type RM Length L Ch R = 1 ,8889    ,236,236,236
BEGIN DESCRIPTION:
South Double Creek 19.0
END DESCRIPTION:
XS GIS Cut Line= 5
      1615004.11       978684.07      1615082.42       978653.76
      1615185.99       978577.97      1615213.78        978532.5
       1615254.2       978370.83
#Sta/Elev= 30
  4845.9  816.22  4857.2  818.96  4862.7   821.3  4893.3  822.34  4902.1  819.26
  4917.1  807.94  4929.9   802.6  4939.2  796.44  4947.1  793.04  4962.6  774.56
  4971.5  768.76  4989.4  761.86  4989.6  757.66  4991.1  754.66  5008.9  754.66
  5010.4  757.66  5011.2  758.37  5020.8  762.39  5035.4  764.05  5043.2     767
  5074.1  768.78  5102.7  773.97  5107.3  775.41  5134.6  780.04    5160  782.85
  5194.8  787.79  5211.4  788.92  5235.6  791.32  5253.4  791.66  5278.1  790.86
#Mann= 3 ,-1 , 0
  4845.9     .09       0  4989.6     .05       0  5010.4     .09       0
Bank Sta=4989.6,5010.4
Exp/Cntr=0.3,0.1

Type RM Length L Ch R = 1 ,8653    ,99,99,99
BEGIN DESCRIPTION:
South Double Creek 18.0
END DESCRIPTION:
XS GIS Cut Line= 3
      1615335.03       978787.64       1615322.4       978577.97
      1615261.77       978408.72
#Sta/Elev= 30
  4816.8  835.99  4826.4  831.52  4834.7  826.21  4856.6   814.2  4858.3  810.83
  4865.7  801.39  4876.8  795.46  4901.8  784.52  4911.4  781.25  4918.3  777.41
    4934     772  4949.2  767.98  4977.5  765.14  4987.4  763.24  4989.2  762.03
  4989.6  755.62  4991.1  752.62  5008.9  752.62  5010.4  755.62  5012.3  757.71
  5025.7  764.89  5036.2  769.01  5047.1  774.66  5062.5  777.93  5097.1  782.23
  5139.5  785.49  5151.1  787.25  5168.6   787.9  5201.3  791.62  5206.6  791.57
#Mann= 3 ,-1 , 0
  4816.8     .09       0  4989.6     .05       0  5010.4     .09       0
Bank Sta=4989.6,5010.4
Exp/Cntr=0.3,0.1

Type RM Length L Ch R = 1 ,8554    ,486,486,486
BEGIN DESCRIPTION:
South Double Creek 17.0
END DESCRIPTION:
XS GIS Cut Line= 5
      1615579.07       978569.68      1615433.55        978580.5
      1615377.98       978567.87      1615312.96       978525.46
      1615278.21       978442.54
#Sta/Elev= 30
  4823.8  825.79  4831.1  824.28  4848.9  817.59  4853.2  816.82  4876.2  804.52
  4879.8  804.01  4902.5  796.37  4914.7  792.59  4937.1  786.49    4954  780.39
  4960.2  777.58  4969.7  770.84    4972  769.63  4986.6  756.81    4989     758
  4989.6  755.62  4991.1  752.62  5008.9  752.62  5010.4  755.62  5026.7  767.14
  5027.2  767.27  5038.9  767.65  5059.5  772.14  5072.2   773.7  5098.4  778.53
  5146.3  783.19  5154.8  784.28  5162.2  784.71  5168.8  785.74  5194.2  787.59
#Mann= 3 ,-1 , 0
  4823.8     .09       0  4989.6     .05       0  5010.4     .09       0
Bank Sta=4989.6,5010.4
Exp/Cntr=0.3,0.1

Type RM Length L Ch R = 1 ,8068    ,562,562,562
BEGIN DESCRIPTION:
South Double Creek 16.5
END DESCRIPTION:
XS GIS Cut Line= 3
      1615615.43       978173.79      1615385.55       978100.53
      1615246.62       978080.32
#Sta/Elev= 30
    4755  807.53  4772.4  804.24  4807.5  796.56  4820.7  793.23    4842  788.71
  4864.9  782.79  4879.8  779.81  4894.7  777.41  4920.4  770.51  4926.9  770.47
  4935.7  768.59  4950.5  766.35  4961.7  766.06  4977.5  760.07  4985.7   757.9
  4989.6  755.44  4991.1  752.44  5008.9  752.44  5010.4  755.44  5012.9  758.37
  5018.6  761.13  5028.1  766.71  5036.7  770.56  5060.2  786.74  5072.5  796.95
  5083.1     803  5090.9  809.06  5108.5  817.84  5123.8  824.71  5136.7   826.1
#Mann= 3 ,-1 , 0
    4755     .09       0  4989.6     .05       0  5010.4     .09       0
Bank Sta=4989.6,5010.4
Exp/Cntr=0.3,0.1

Type RM Length L Ch R = 1 ,7506    ,554,554,554
BEGIN DESCRIPTION:
South Double Creek 16.0
END DESCRIPTION:
XS GIS Cut Line= 4
      1615852.89       977933.81      1615681.11       977620.57
      1615511.86       977552.36      1615261.77       977630.67
#Sta/Elev= 30
  4573.2  822.12  4621.5  812.66  4659.4   803.3  4733.6     788  4794.3  777.13
  4807.3  776.29  4825.3   772.1  4838.2  770.11  4887.2  765.86  4931.4  763.66
  4959.3  762.79  4969.9  760.56  4989.6  753.64  4991.1  750.64  5008.9  750.64
  5010.4  753.64  5014.2  758.57  5018.4  761.46    5029  764.37  5037.5  765.46
  5108.1  762.43  5122.4  763.68  5167.5  764.52  5193.9  767.95  5217.9  776.38
  5290.4  792.95  5309.3  798.94  5315.2  799.29  5357.9  810.96    5375  814.56
#Mann= 7 ,-1 , 0
  4573.2     .09       0  4733.6    .035       0  4931.4     .09       0
  4989.6     .05       0  5010.4     .09       0    5029    .035       0
  5290.4     .09       0
Bank Sta=4989.6,5010.4
Exp/Cntr=0.3,0.1

Type RM Length L Ch R = 1 ,6952    ,498,498,498
BEGIN DESCRIPTION:
South Double Creek 15.0
END DESCRIPTION:
XS GIS Cut Line= 5
       1615931.2       977898.44      1615953.94       977496.79
      1615845.31       977226.49       1615883.2       977135.55
      1615964.04       976968.82
#Sta/Elev= 30
  4251.1  814.43  4298.8   807.2  4393.3  790.91  4439.2  783.96  4452.8  778.75
  4467.4  778.65  4510.7   775.6  4568.9  773.25  4732.2  772.04    4784  769.93
  4860.6  763.69  4914.6  762.16  4934.5  762.11  4959.9  764.21  4972.5  763.34
  4980.5  759.56  4985.8  752.48  4987.3  749.48  5012.7  749.48  5014.2  752.48
    5019  752.77  5033.4   758.1  5061.2  763.66    5105  786.96  5130.1  804.48
  5140.6  809.75    5167  826.98  5192.9  843.09    5203  848.38  5228.5  860.32
#Mann= 4 ,-1 , 0
  4251.1    .035       0  4914.6     .09       0  4985.8     .05       0
  5014.2     .09       0
Bank Sta=4985.8,5014.2
Exp/Cntr=0.3,0.1

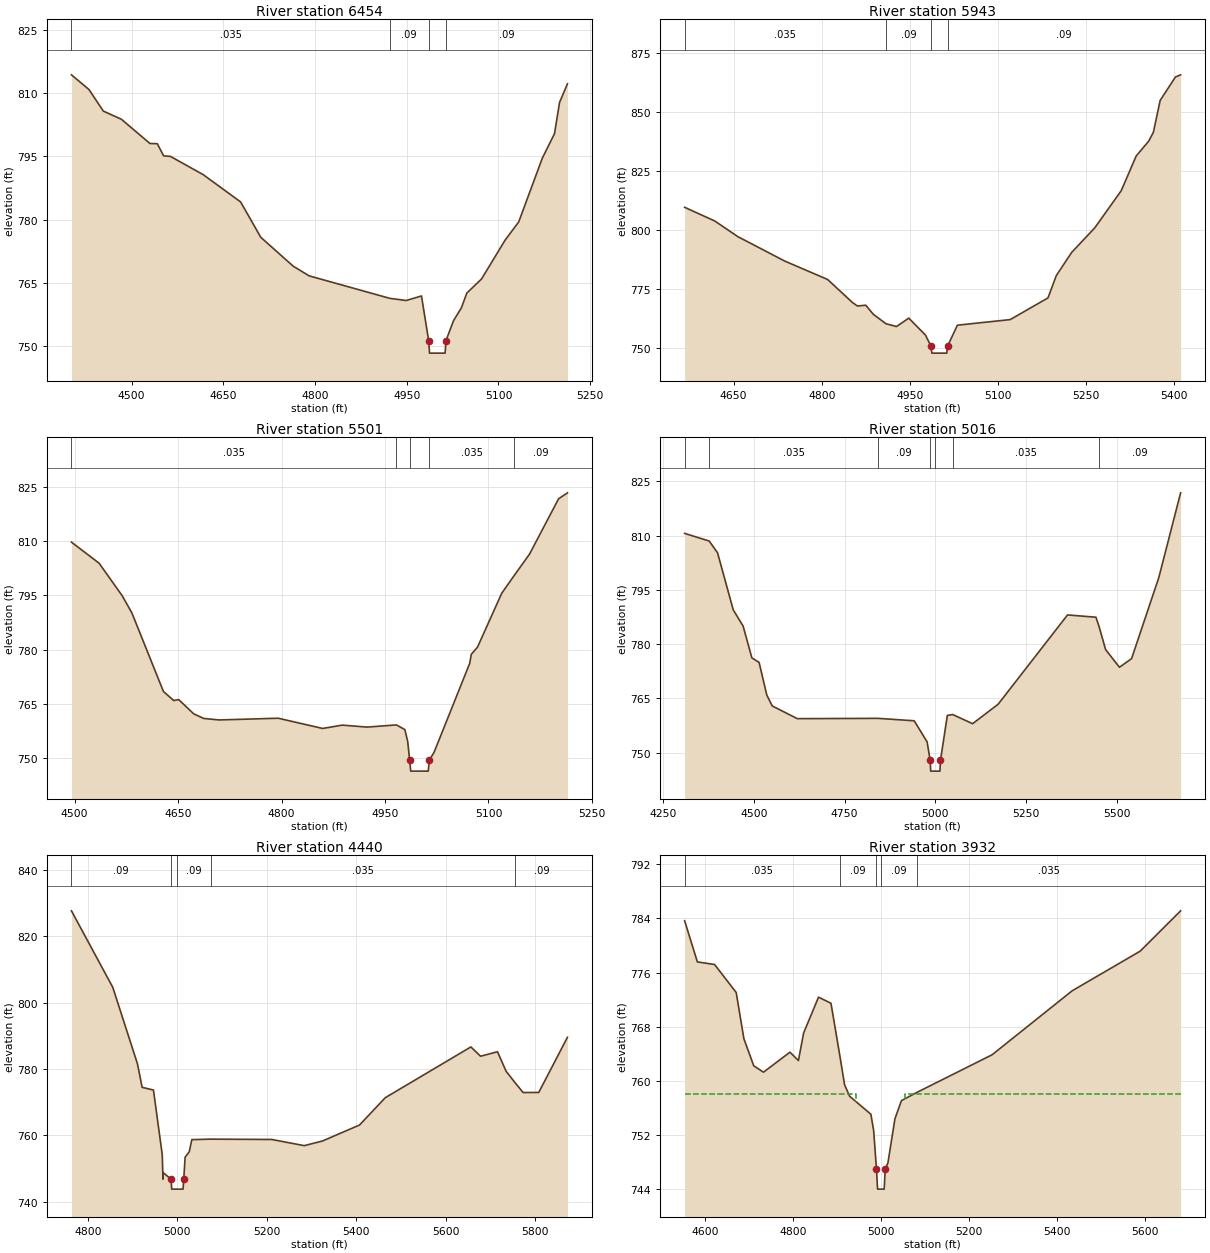
Type RM Length L Ch R = 1 ,6454    ,511,511,511
BEGIN DESCRIPTION:
South Double Creek 14.0
END DESCRIPTION:
XS GIS Cut Line= 4
       1616047.4       977898.44      1616241.92       977496.79
      1616322.75       977367.95      1616466.74       977211.33
#Sta/Elev= 30
  4401.7  814.41  4430.3  810.92  4453.8  805.79  4483.4  803.84    4530  798.09
  4542.1  798.03  4552.4  795.15  4563.5  795.02  4617.2  790.67  4678.3  784.19
  4711.3  775.78  4764.2  768.93  4790.2  766.62  4922.2  761.27    4949  760.75
  4974.1  761.83  4985.8  751.24  4987.3  748.24  5012.7  748.24  5014.2  751.24
  5026.5  755.96  5039.3  758.99  5048.2  762.51  5072.3  765.88    5111  775.14
  5133.1  779.44  5171.7   794.6  5191.6  800.41  5199.9  807.86  5212.8  812.28
#Mann= 4 ,-1 , 0
  4401.7    .035       0  4922.2     .09       0  4985.8     .05       0
  5014.2     .09       0
Bank Sta=4985.8,5014.2
Exp/Cntr=0.3,0.1

Type RM Length L Ch R = 1 ,5943    ,442,442,442
BEGIN DESCRIPTION:
South Double Creek 13.0
END DESCRIPTION:
XS GIS Cut Line= 4
      1616436.43       978047.48       1616656.2       977724.14
      1616729.46       977663.51      1616951.76       977383.11
#Sta/Elev= 30
  4566.7  809.56    4618  803.75  4657.2  797.11  4736.7  786.77    4810  778.91
  4852.2  769.15  4860.7  767.65  4874.9  767.99  4887.7  764.14  4909.3  760.12
  4927.3  758.94  4948.1   762.5  4976.5   755.3  4985.8  750.64  4987.3  747.64
  5012.7  747.64  5014.2  750.64  5030.8   759.5  5120.7  761.88  5184.9  771.08
  5199.1  780.56  5225.3  790.43  5264.5  800.82  5309.5  816.58    5335  831.34
  5356.4  837.68  5364.3  841.45  5375.8  854.94  5401.8   864.9  5410.6  865.81
#Mann= 4 ,-1 , 0
  4566.7    .035       0  4909.3     .09       0  4985.8     .05       0
  5014.2     .09       0
Bank Sta=4985.8,5014.2
Exp/Cntr=0.3,0.1

Type RM Length L Ch R = 1 ,5501    ,485,485,485
BEGIN DESCRIPTION:
South Double Creek 12.0
END DESCRIPTION:
XS GIS Cut Line= 5
      1616567.79       978098.01      1616772.41       978047.48
      1616999.76       977979.28      1617088.95       977896.62
      1617181.64       977779.71
#Sta/Elev= 30
  4495.5   809.7  4535.6  803.86    4569  794.89  4583.1  790.12  4628.8  768.41
  4643.8  765.89  4650.9  766.16  4672.7  762.23  4687.1  760.95  4709.6  760.53
  4795.2  761.01  4859.6  758.18  4888.1   759.1  4924.1  758.55  4966.6  759.16
  4978.8  757.86  4982.9  754.61  4985.8  749.38  4987.3  746.38  5012.7  746.38
  5014.2  749.38  5021.2  751.61  5072.9  776.23  5075.1  778.68  5084.1  780.66
  5119.2  795.55  5137.1  800.42  5159.5  806.38  5201.6  821.67  5214.5  823.33
#Mann= 5 ,-1 , 0
  4495.5    .035       0  4966.6     .09       0  4985.8     .05       0
  5014.2    .035       0  5137.1     .09       0
Bank Sta=4985.8,5014.2
Exp/Cntr=0.3,0.1

Type RM Length L Ch R = 1 ,5016    ,576,576,576
BEGIN DESCRIPTION:
South Double Creek 11.0
END DESCRIPTION:
XS GIS Cut Line= 5
      1616777.46       978719.44      1617292.79       978335.46
       1617371.5       978290.34      1617522.67       978014.64
      1617626.24       977714.03
#Sta/Elev= 30
  4309.7  810.59  4377.4  808.48  4400.4  805.23  4443.6  789.47  4470.8  784.99
  4494.9  776.21  4514.8  774.96  4535.9  765.97  4550.9  762.94    4620  759.43
  4842.8  759.51  4941.9  758.84  4977.4  753.01  4985.8  747.94  4987.3  744.94
    5000  744.94  5012.7  744.94  5014.2  747.94  5033.1  760.32  5047.8  760.57
  5102.7  758.04    5173  763.42    5364  788.07  5442.3  787.44  5451.1  784.79
  5468.9   778.5    5507  773.62  5540.4  776.01  5615.3  798.37  5675.4  821.79
#Mann= 7 ,-1 , 0
  4309.7     .09       0  4377.4    .035       0  4842.8     .09       0
  4985.8     .05       0    5000     .09       0  5047.8    .035       0
  5451.1     .09       0
Bank Sta=4985.8,5014.2
Exp/Cntr=0.3,0.1

Type RM Length L Ch R = 1 ,4440    ,508,508,508
BEGIN DESCRIPTION:
South Double Creek 10.0
END DESCRIPTION:
XS GIS Cut Line= 5
      1617601.93       978904.79      1617605.09       978655.34
       1617589.3        978270.1      1617562.07        978014.2
      1617620.87       977805.92
#Sta/Elev= 30
  4763.2  827.63  4855.6  804.57  4910.7  781.55  4921.2  774.44  4946.5  773.63
  4966.1   754.2  4967.8  746.77  4968.2  748.75  4985.8  746.77  4987.3  743.77
    5000  743.77  5012.7  743.77  5014.2  746.77  5017.3  753.41  5026.5  755.02
  5032.3  758.68  5074.4  758.83    5211  758.73  5283.6  756.87  5324.5  758.28
  5407.2  763.09  5464.7  771.32  5656.1  786.62  5677.7  783.82  5715.6  785.17
  5734.8  779.31  5755.3  775.77  5772.9  772.88  5807.8   772.9    5872  789.53
#Mann= 5 ,-1 , 0
  4763.2     .09       0  4985.8     .05       0    5000     .09       0
  5074.4    .035       0  5755.3     .09       0
Bank Sta=4985.8,5014.2
Exp/Cntr=0.5,0.3

Type RM Length L Ch R = 1 ,3932    ,139,139,139
BEGIN DESCRIPTION:
P-East Rd. SR-1483 - US
END DESCRIPTION:
XS GIS Cut Line= 6
      1618334.51       978813.22      1618239.78       978740.59
      1618129.26       978709.02      1618075.58       978630.08
      1617974.53       978396.41      1617573.51       978030.12
#Sta/Elev= 30
  4553.9  783.67  4582.9  777.58    4622   777.2  4671.1  773.07  4688.7  766.22
    4711  762.23  4733.2  761.28  4793.3  764.24  4812.6  763.01  4824.5  767.09
  4858.3  772.37  4886.6  771.47  4906.5  763.82  4917.5  759.43    4929  757.73
  4977.3  755.07  4983.6  752.67    4990     747  4992.5     744    5000     744
  5007.5     744    5010     747    5016  747.86    5032  754.39  5046.8  757.08
  5082.5  758.31    5253  763.86  5434.6   773.3  5589.5  779.17  5681.4  785.13
#Mann= 5 ,-1 , 0
  4553.9    .035       0  4906.5     .09       0    4990    .045       0
    5000     .09       0  5082.5    .035       0
#XS Ineff= 2 , 0
       0  4944.4  757.99  5054.5       0  757.99
Permanent Ineff=
       F       F
Bank Sta=4990,5010
Exp/Cntr=0.5,0.3