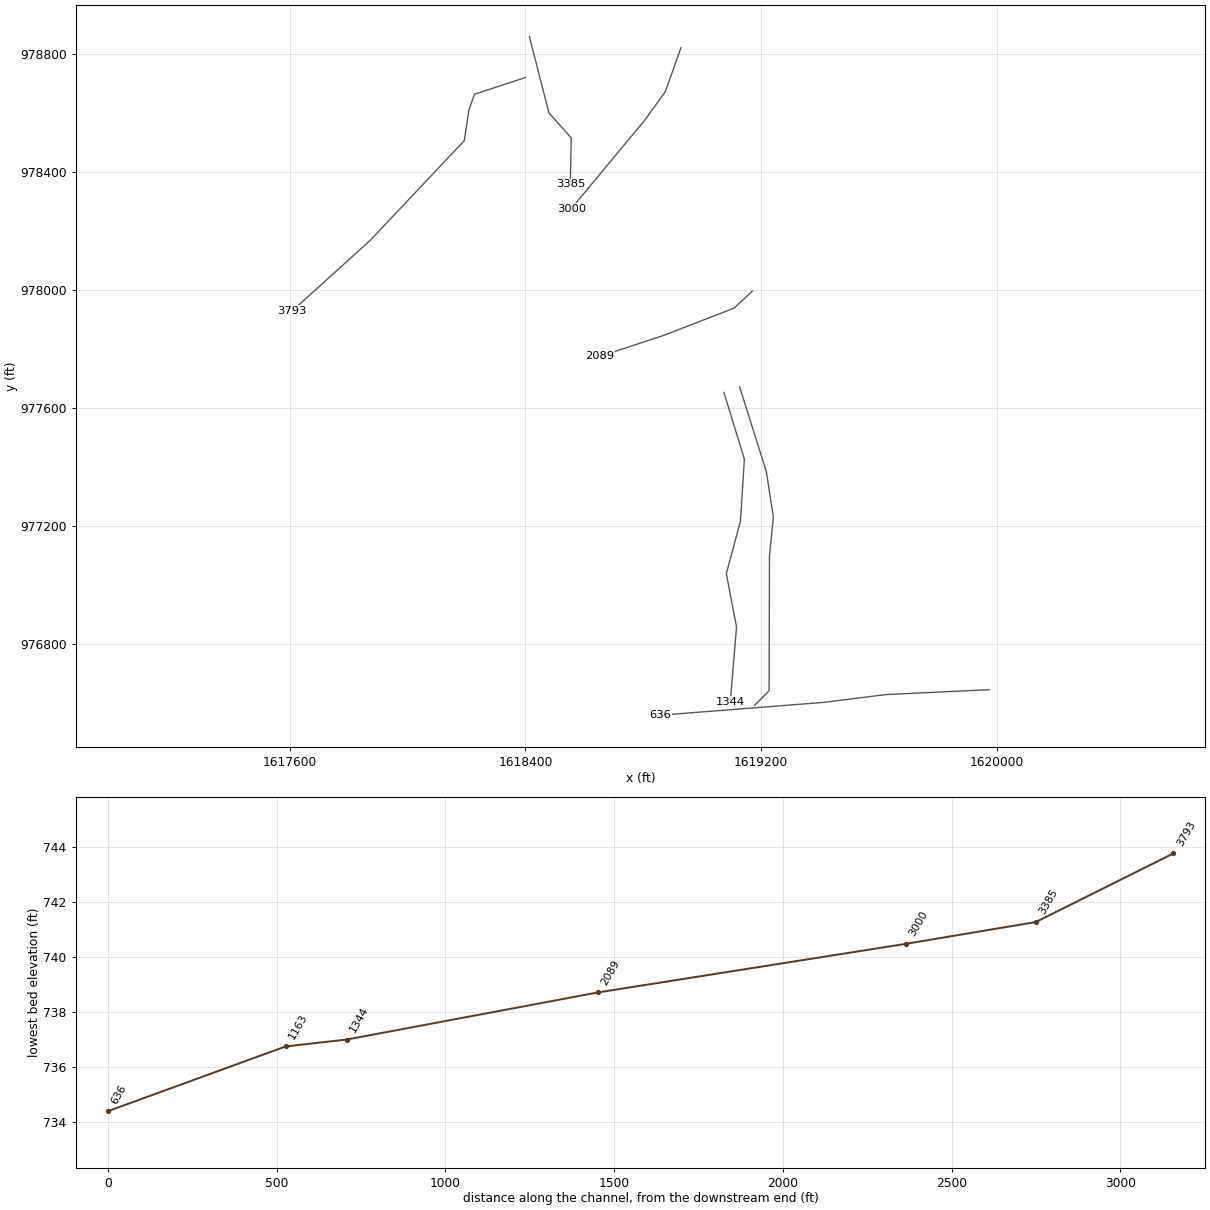
HEC-RAS study lds_south_double_crk.prj: South Double Creek Limited Detail Study

--- lds_south_double_crk.g01 (geometry) --- (continued)

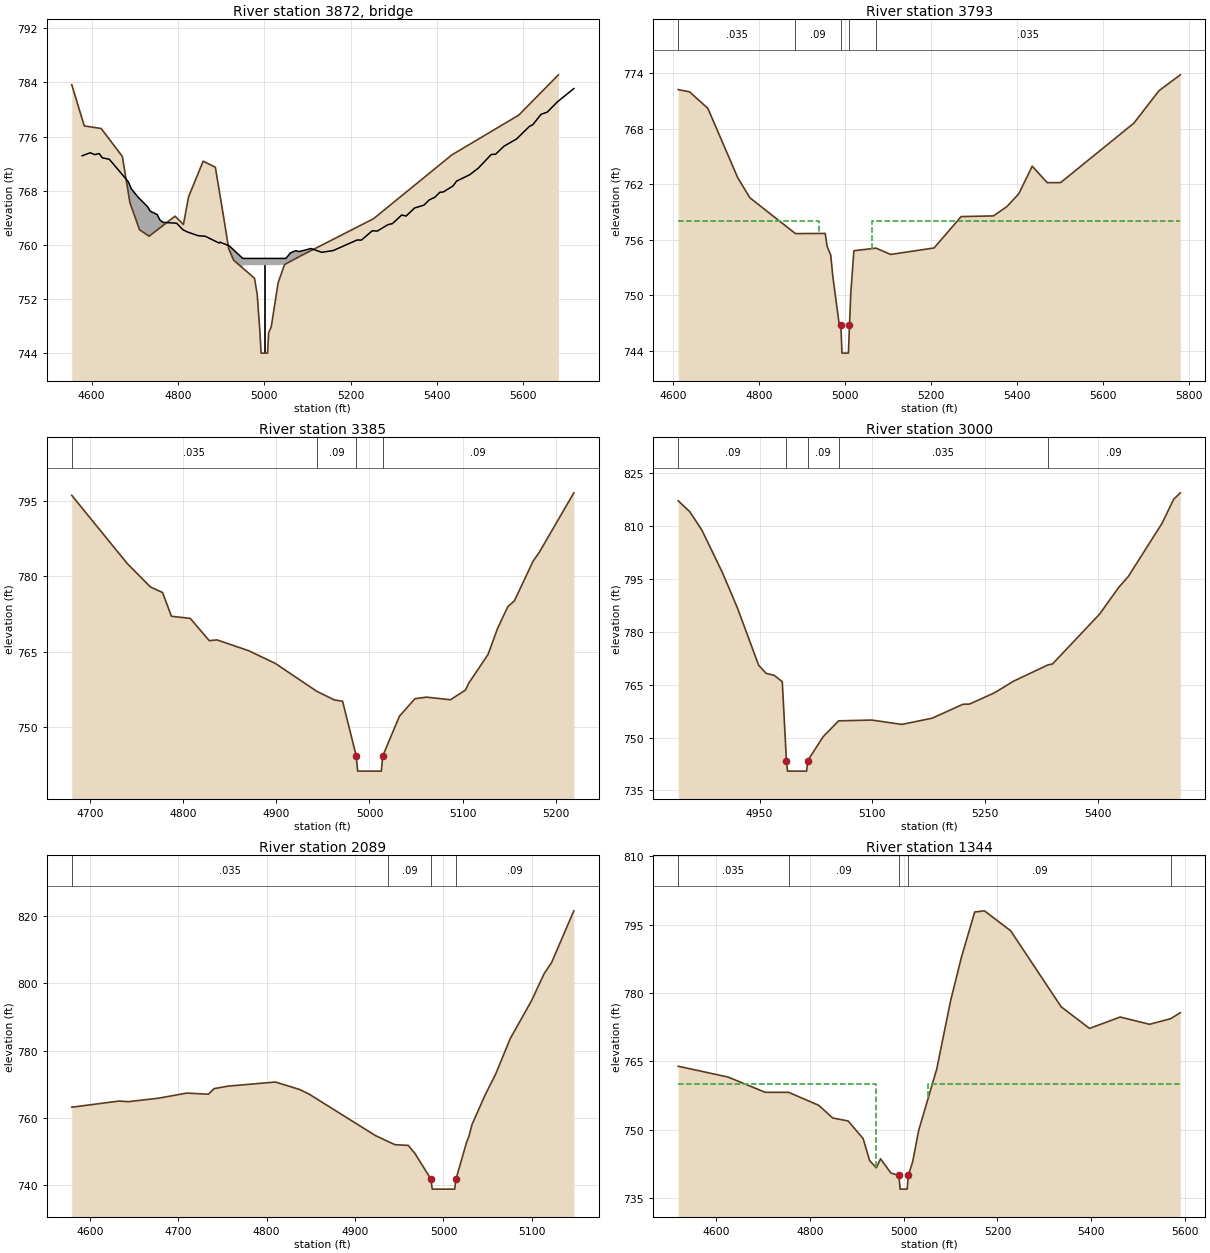
Type RM Length L Ch R = 3 ,3872    ,,,
BEGIN DESCRIPTION:
P-East Rd. SR-1483
Structure ID: P - East Rd.
Approximate Survey Structure
END DESCRIPTION:
Bridge Culvert--1,0,-1,-1, 0
Deck Dist Width WeirC Skew NumUp NumDn MinLoCord MaxHiCord MaxSubmerge Is_Ogee
55,25,3,0, 60, 60, , , , 0, 1,1,,
  4577.8  4596.6    4607  4617.4  4624.8  4640.9  4684.8  4691.7  4707.7  4729.3
  4735.9  4751.8    4758  4765.2  4796.9  4810.9  4820.9  4846.3  4863.2  4895.6
  4897.3  4918.9    4950    4950    5050    5050  5060.6  5072.8  5080.2  5108.2
  5132.9  5159.3  5214.9  5225.2  5250.1  5261.7  5286.7  5296.9  5318.5  5328.4
  5348.1  5369.9  5381.8  5394.8  5406.9  5414.5  5437.3  5445.5  5475.8  5495.5
  5525.9  5535.7  5555.7  5584.3    5614  5622.3  5641.2  5655.6  5679.2  5717.2
  773.16  773.61  773.34  773.49  772.86  772.65  769.34  768.29  767.04  765.66
  764.97  764.48  763.69  763.33   763.2  762.26  761.93  761.36  761.27  760.26
   760.4  759.85     758     758     758     758  758.81  759.15     759  759.46
   758.9  759.15  760.72  760.71  762.08  762.04  762.99  763.14  764.42  764.25
  765.45  765.87  766.63  767.02  767.78  767.81  768.71  769.42  770.36  771.32
  773.36  773.39   774.6  775.64  777.49  777.77  779.29  779.62  781.14   783.1
     724     724     724     724     724     724     724     724     724     724
     724     724     724     724     724     724     724     724     724     724
     724     724     724     757     757     724     724     724     724     724
     724     724     724     724     724     724     724     724     724     724
     724     724     724     724     724     724     724     724     724     724
     724     724     724     724     724     724     724     724     724     724
  4577.8  4596.6    4607  4617.4  4624.8  4640.9  4684.8  4691.7  4707.7  4729.3
  4735.9  4751.8    4758  4765.2  4796.9  4810.9  4820.9  4846.3  4863.2  4895.6
  4897.3  4918.9    4950    4950    5050    5050  5060.6  5072.8  5080.2  5108.2
  5132.9  5159.3  5214.9  5225.2  5250.1  5261.7  5286.7  5296.9  5318.5  5328.4
  5348.1  5369.9  5381.8  5394.8  5406.9  5414.5  5437.3  5445.5  5475.8  5495.5
  5525.9  5535.7  5555.7  5584.3    5614  5622.3  5641.2  5655.6  5679.2  5717.2
  773.16  773.61  773.34  773.49  772.86  772.65  769.34  768.29  767.04  765.66
  764.97  764.48  763.69  763.33   763.2  762.26  761.93  761.36  761.27  760.26
   760.4  759.85     758     758     758     758  758.81  759.15     759  759.46
   758.9  759.15  760.72  760.71  762.08  762.04  762.99  763.14  764.42  764.25
  765.45  765.87  766.63  767.02  767.78  767.81  768.71  769.42  770.36  771.32
  773.36  773.39   774.6  775.64  777.49  777.77  779.29  779.62  781.14   783.1
     724     724     724     724     724     724     724     724     724     724
     724     724     724     724     724     724     724     724     724     724
     724     724     724     757     757     724     724     724     724     724
     724     724     724     724     724     724     724     724     724     724
     724     724     724     724     724     724     724     724     724     724
     724     724     724     724     724     724     724     724     724     724
Pier Skew, UpSta & Num, DnSta & Num=  ,5000, 2 ,5000, 2 , 0 , 0 , 0 ,0,0
       2       2
     744   757.1
       2       2
  743.75   757.1
Abutment Skew #Up #Dn= , 2 , 2
    4950  4957.5
     756  755.44
    4950  4957.5
     756  755.42
Abutment Skew #Up #Dn= , 2 , 2
  5042.5    5050
   756.3     756
  5042.5    5050
  754.71     756
BR Coef= 1 , 1 , 0 ,1.25, 0 ,,,0.8,0,2,0,
WSPro=,,,, 1 ,,,, 0 ,,,, 0 ,,,,-1 ,-1 ,-1 , 0 , 0 , 0 , 0 , 0
BR D #Sta/Elev= 164
  4611.6  772.21  4612.4  772.19  4617.8  772.28  4618.9  772.24  4619.2  772.22
  4620.8  772.23  4635.4  771.92  4637.7  771.98  4640.2  771.78  4648.3   771.4
  4664.2  771.17  4664.3  771.16  4664.5  771.15  4680.5  770.19  4686.4  769.33
  4703.4  768.01  4705.5  767.53  4717.2  766.66    4726  765.73  4727.8  765.33
  4733.1  764.44  4738.1  764.13  4749.5  762.75    4750   762.7  4754.9  762.56
    4758  762.36  4772.5  761.16  4778.5  760.52  4794.3  760.29  4798.6  759.92
  4809.1  759.67  4819.7   759.1  4820.4  758.99  4830.7   758.3  4834.3   758.2
  4841.8  757.82  4851.3  757.56  4861.7  757.31  4865.3  757.16  4874.9   756.9
  4877.6  756.79  4884.3  756.66  4888.2  756.59  4889.8  756.53  4914.7  756.44
  4927.5  756.22    4933   756.3  4940.5  756.34  4949.8  756.55  4953.5  756.68
  4956.7  755.65    4958  755.28  4966.4  754.33    4971  752.12  4985.5  747.05
    4990  746.75  4992.5     744  5007.5     744    5010  746.75  5013.1  750.29
    5017  752.98  5020.2  754.81    5024  755.17    5031  754.75  5037.5   754.8
  5041.6  754.72  5045.9  754.66  5048.5  754.73    5051  754.87  5060.4  755.13
  5069.9  755.13  5071.5  755.09    5073  755.05  5081.9  754.69  5086.9  754.58
  5105.8  754.41  5110.4  754.65  5114.2  754.78  5120.8  754.59  5125.9  754.76
  5138.2  754.91    5141  754.88  5149.9  754.66  5160.5  754.77  5171.2  754.75
  5172.9  754.77  5179.4  754.95  5183.9  754.95  5188.7  755.01  5189.6     755
  5195.8  754.96  5206.8  755.11  5215.9  754.94  5248.3  755.52  5255.2  755.97
  5260.7  755.91  5270.5  756.33  5273.7  756.61  5281.9  756.99  5302.6  757.71
  5311.5  757.53  5312.1  757.52  5334.3  758.45  5339.3  758.55  5344.9  758.57
  5348.3  758.78  5351.4   758.8  5358.9  759.19  5367.2  759.28  5375.9  759.58
  5376.5  759.59  5403.8  760.96  5409.9  761.47  5419.6  762.81  5421.9  762.98
  5430.6  763.75  5435.1  763.94  5440.4  763.74  5447.4  763.14  5454.7  762.94
  5458.4  762.94  5461.7  762.81  5468.2  762.28  5470.1  762.16  5472.9  762.12
  5493.8  762.44  5501.1  762.17  5501.2  762.17  5529.5  762.92  5530.4  762.98
  5539.9  763.74  5549.3  763.88  5550.2  763.96  5551.1  763.99  5558.4   764.2
  5561.2  764.22  5568.8  764.85  5579.3  765.12  5580.4  765.18  5581.2  765.21
    5589  765.72  5591.8  765.78    5601  766.26  5622.4  766.85  5631.6  767.29
  5642.6  767.65  5652.1  767.82  5668.3   768.5  5671.8   768.6  5688.9  769.46
  5702.1  770.34  5710.8  770.59  5714.5  770.83  5729.9  772.09  5740.9  772.39
  5743.8  772.67  5746.9  772.71  5754.2  772.89  5760.8  773.25  5763.5  773.35
  5768.9  773.48  5772.3  773.71  5778.6  773.78  5779.6  773.81
BR D #Mann= 5
  4611.6    .035  4884.3     .09    4990    .055    5010     .09  5071.5    .035
BC Design=,, 0 ,, 0 ,,,,,,
BC HTab HWMax=785.13

Type RM Length L Ch R = 1 ,3793    ,408,408,408
BEGIN DESCRIPTION:
P-East Rd. SR-1483 - DS
END DESCRIPTION:
XS GIS Cut Line= 6
      1618400.82       978721.65      1618227.15       978664.81
       1618208.2       978611.13      1618192.41       978506.93
      1617873.49       978169.06      1617608.24       977929.07
#Sta/Elev= 30
  4611.6  772.21  4637.7  771.98  4680.5  770.19    4750   762.7  4778.5  760.52
  4884.3  756.66  4953.5  756.68    4958  755.28  4966.4  754.33    4971  752.12
  4985.5  747.05    4990  746.75  4992.5  743.75  5007.5  743.75    5010  746.75
  5013.1  750.29  5020.2  754.81  5071.5  755.09  5105.8  754.41  5206.8  755.11
 5269.74   758.5  5344.9  758.57  5376.5  759.59  5403.8  760.96  5435.1  763.94
  5470.1  762.16  5501.2  762.17  5671.8   768.6  5729.9  772.09  5779.6  773.81
#Mann= 5 ,-1 , 0
  4611.6    .035       0  4884.3     .09       0    4990    .055       0
    5010     .09       0  5071.5    .035       0
#XS Ineff= 2 , 0
       0  4938.3  758.03  5062.3       0  758.03
Permanent Ineff=
       F       F
Bank Sta=4990,5010
Exp/Cntr=0.5,0.3

Type RM Length L Ch R = 1 ,3385    ,385,385,385
BEGIN DESCRIPTION:
South Double Creek 8.0
END DESCRIPTION:
XS GIS Cut Line= 4
      1618413.45       978860.59      1618479.76       978601.66
      1618555.55        978516.4      1618552.39       978358.52
#Sta/Elev= 30
  4680.2  796.09  4739.8  782.53  4764.8  777.86  4777.7  776.77  4787.3  772.05
  4807.5  771.62  4827.9   767.2  4836.2  767.35  4870.1  765.21  4898.7  762.69
  4943.5  757.12  4962.2  755.42  4971.1  755.15  4985.8  744.26  4987.3  741.26
  5012.7  741.26  5014.2  744.26  5032.2  752.19  5048.8  755.66  5061.3  755.97
  5086.9  755.45  5103.1  757.37  5106.5  758.71  5127.4  764.48  5137.5   769.6
  5148.6  773.97  5155.6   775.1  5175.8  783.03  5182.3  784.74  5219.5  796.59
#Mann= 4 ,-1 , 0
  4680.2    .035       0  4943.5     .09       0  4985.8    .055       0
  5014.2     .09       0
Bank Sta=4985.8,5014.2
Exp/Cntr=0.3,0.1

Type RM Length L Ch R = 1 ,3000    ,911,911,911
BEGIN DESCRIPTION:
South Double Creek 7.0
END DESCRIPTION:
XS GIS Cut Line= 4
      1618928.15       978822.69      1618875.11       978673.69
        1618805.        978576.4      1618555.55       978276.42
#Sta/Elev= 30
  4841.8  817.11  4857.1  814.05  4873.4  808.76  4900.8  796.68  4920.7  786.69
  4948.9  770.47  4958.9  768.19  4969.7  767.61  4980.3  765.83  4985.8  743.47
  4987.3  740.47  5012.7  740.47  5014.2  743.47  5034.7  750.23  5055.3  754.73
  5099.3  754.95  5139.5  753.72  5179.8  755.48  5220.7  759.42  5229.6  759.49
    5263  762.71  5288.1  765.97  5333.8  770.58    5340  770.86  5402.7     785
  5427.9  792.51    5441   795.7  5485.7  810.71  5501.3  817.57  5510.1  819.38
#Mann= 5 ,-1 , 0
  4841.8     .09       0  4985.8     .05       0  5014.2     .09       0
  5055.3    .035       0  5333.8     .09       0
Bank Sta=4985.8,5014.2
Exp/Cntr=0.3,0.1

Type RM Length L Ch R = 1 ,2089    ,745,745,745
BEGIN DESCRIPTION:
South Double Creek 6.0
END DESCRIPTION:
XS GIS Cut Line= 4
      1619169.92       977995.99      1619108.14       977938.54
      1618871.65       977846.85      1618653.28       977774.95
#Sta/Elev= 30
  4579.6  763.12    4633  764.95  4643.6  764.77  4677.6   765.8  4709.8  767.33
  4734.2  766.99  4740.5  768.65  4756.4   769.4    4810  770.62  4837.3   768.4
  4848.5  766.95  4922.8  754.71  4937.3   752.9  4945.1  751.96  4960.2  751.74
  4967.7  749.37  4985.8  741.71  4987.3  738.71  5012.7  738.71  5014.2  741.71
  5026.3  752.79  5028.7  754.34  5032.4  758.02    5047  766.68  5059.1  773.01
  5075.6  783.59  5099.6  794.83  5113.8  802.85  5122.3  806.21  5147.5  821.63
#Mann= 4 ,-1 , 0
  4579.6    .035       0  4937.3     .09       0  4985.8     .05       0
  5014.2     .09       0
Bank Sta=4985.8,5014.2
Exp/Cntr=0.5,0.3

Type RM Length L Ch R = 1 ,1344    ,181,181,181
BEGIN DESCRIPTION:
Dan George Rd. SR-1484 - US
END DESCRIPTION:
XS GIS Cut Line= 6
      1619074.05       977652.44      1619143.29       977426.08
      1619129.97       977215.69      1619082.04       977037.26
      1619116.66       976856.17      1619095.57        976602.9
#Sta/Elev= 30
  4519.3  763.94  4625.7  761.57  4704.5  758.23  4754.7  758.22    4819  755.37
  4848.7   752.6  4881.7  751.94  4913.6  748.09  4927.5  743.26  4941.8  741.68
  4950.8  743.65  4972.9  740.52    4990     740  4992.5     737  5007.5     737
    5010     740  5019.3     743    5032  749.84  5070.7  763.36  5100.3  778.35
  5123.4  787.89  5151.6  797.75  5172.3  798.01  5228.3  793.64    5336  776.97
  5396.5  772.23  5461.9  774.73  5524.5  773.13  5569.6  774.37  5590.1  775.68
#Mann= 5 ,-1 , 0
  4519.3    .035       0  4754.7     .09       0    4990     .05       0
    5010     .09       0  5569.6    .035       0
#XS Ineff= 2 , 0
       0  4941.9  759.99  5052.8       0  759.99
Permanent Ineff=
       F       F
Bank Sta=4990,5010
Exp/Cntr=0.5,0.3

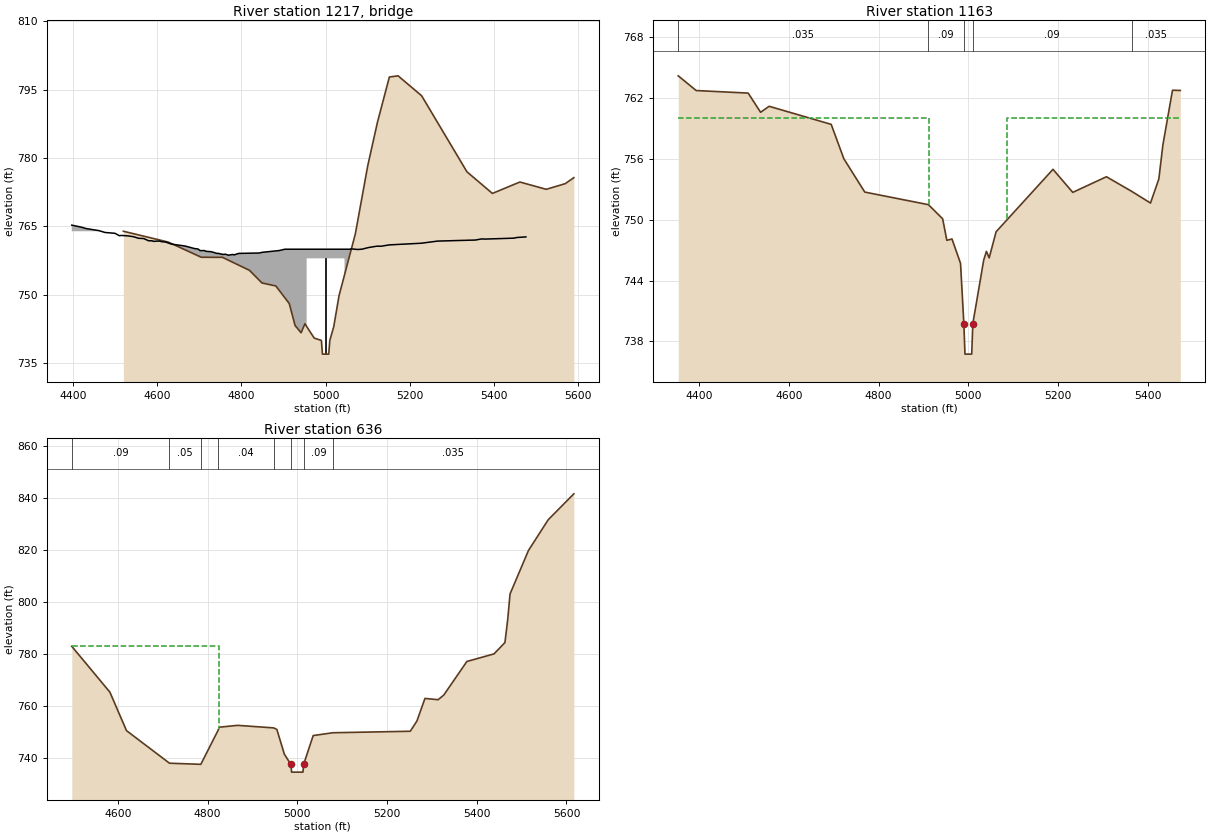
Type RM Length L Ch R = 3 ,1217    ,,,
BEGIN DESCRIPTION:
Dan George Rd. SR-1484
Structure ID: Dan George Rd
Approximate Survey Structure
END DESCRIPTION:
Bridge Culvert--1,0,-1,-1, 0
Deck Dist Width WeirC Skew NumUp NumDn MinLoCord MaxHiCord MaxSubmerge Is_Ogee
115,24,3,0, 58, 58, , , , 0, 1,1,,
  4396.6  4420.3  4429.7  4461.4  4475.5  4499.1  4509.7  4514.8  4530.3  4543.5
  4555.6  4567.5  4579.2  4587.5    4591  4604.1  4610.7  4619.2  4633.9  4665.5
  4688.1  4696.9  4701.6  4712.7  4715.2  4728.4  4742.1  4745.1  4755.4  4762.1
  4768.7  4779.1  4782.1  4793.3  4842.4  4849.3  4889.8  4903.1    4955    4955
    5045    5045  5056.9  5061.5  5076.3  5086.9  5101.8  5121.5  5131.6  5151.7
  5227.2  5266.2  5356.2  5371.3    5379  5446.6  5455.1  5476.2
  765.28  764.82  764.55  764.07  763.67  763.49  762.96  763.02  762.92  762.74
  762.39  762.34  761.85  761.85  761.72   761.8  761.64  761.58  761.11  760.71
  760.15  760.04   759.7   759.7  759.54  759.45  759.07  759.09  758.86   758.9
  758.69  758.85  758.75  759.08  759.17  759.32  759.71     760     760     760
     760     760     760  760.07  759.94  760.01  760.36  760.66  760.65  760.95
  761.31  761.78  762.01  762.26  762.22  762.42  762.57   762.7
     717     717     717     717     717     717     717     717     717     717
     717     717     717     717     717     717     717     717     717     717
     717     717     717     717     717     717     717     717     717     717
     717     717     717     717     717     717     717     717     717     758
     758     717     717     717     717     717     717     717     717     717
     717     717     717     717     717     717     717     717
  4396.6  4420.3  4429.7  4461.4  4475.5  4499.1  4509.7  4514.8  4530.3  4543.5
  4555.6  4567.5  4579.2  4587.5    4591  4604.1  4610.7  4619.2  4633.9  4665.5
  4688.1  4696.9  4701.6  4712.7  4715.2  4728.4  4742.1  4745.1  4755.4  4762.1
  4768.7  4779.1  4782.1  4793.3  4842.4  4849.3  4889.8  4903.1    4955    4955
    5045    5045  5056.9  5061.5  5076.3  5086.9  5101.8  5121.5  5131.6  5151.7
  5227.2  5266.2  5356.2  5371.3    5379  5446.6  5455.1  5476.2
  765.28  764.82  764.55  764.07  763.67  763.49  762.96  763.02  762.92  762.74
  762.39  762.34  761.85  761.85  761.72   761.8  761.64  761.58  761.11  760.71
  760.15  760.04   759.7   759.7  759.54  759.45  759.07  759.09  758.86   758.9
  758.69  758.85  758.75  759.08  759.17  759.32  759.71     760     760     760
     760     760     760  760.07  759.94  760.01  760.36  760.66  760.65  760.95
  761.31  761.78  762.01  762.26  762.22  762.42  762.57   762.7
     717     717     717     717     717     717     717     717     717     717
     717     717     717     717     717     717     717     717     717     717
     717     717     717     717     717     717     717     717     717     717
     717     717     717     717     717     717     717     717     717     758
     758     717     717     717     717     717     717     717     717     717
     717     717     717     717     717     717     717     717
Pier Skew, UpSta & Num, DnSta & Num=  ,5000, 2 ,5000, 2 , 0 , 0 , 0 ,0,0
       2       2
     737     758
       2       2
  736.75     758
Abutment Skew #Up #Dn= , 2 , 2
    4955    4960
     758  742.64
    4955    4960
     758  748.05
Abutment Skew #Up #Dn= , 2 , 2
    5040    5045
  752.83     758
    5040    5045
  746.84     758
BR Coef= 1 , 1 , 0 ,1.25, 0 ,,,0.8,0,2,0,
WSPro=,,,, 1 ,,,, 0 ,,,, 0 ,,,,-1 ,-1 ,-1 , 0 , 0 , 0 , 0 , 0
BC Design=,, 0 ,, 0 ,,,,,,
BC HTab HWMax=798.11

Type RM Length L Ch R = 1 ,1163    ,527,527,527
BEGIN DESCRIPTION:
Dan George Rd. SR-1484 - DS
END DESCRIPTION:
XS GIS Cut Line= 6
      1619127.31       977671.09      1619217.86       977383.47
      1619241.83       977229.01      1619228.51       977098.51
      1619227.25       976640.16      1619178.24       976590.19
#Sta/Elev= 30
    4354  764.16    4394  762.71  4509.7  762.46  4537.4  760.57  4556.4  761.16
  4694.6  759.38  4722.8  755.99  4769.4  752.71  4911.1  751.47  4942.8  750.08
  4952.1  747.96  4963.6  748.09  4982.6  745.69    4990  739.75  4992.5  736.75
  5007.5  736.75    5010  739.75  5034.2  746.01  5040.2  746.87  5046.4  746.23
  5061.8   748.8  5188.5  754.95  5232.5  752.68  5307.5  754.22  5363.8  752.78
  5405.6  751.63  5424.2     754  5433.1  757.32  5454.6  762.74    5472  762.72
#Mann= 5 ,-1 , 0
    4354    .035       0  4911.1     .09       0    4990     .05       0
    5010     .09       0  5363.8    .035       0
#XS Ineff= 2 , 0
       0    4913  760.02    5087       0  760.01
Permanent Ineff=
       F       F
Bank Sta=4990,5010
Exp/Cntr=0.5,0.3

Type RM Length L Ch R = 1 ,636     ,0,0,0
BEGIN DESCRIPTION:
South Double Creek 2.0
END DESCRIPTION:
XS GIS Cut Line= 4
      1619973.85       976643.45      1619624.32       976626.81
      1619411.27       976600.18      1618858.67        976556.9
#Sta/Elev= 30
  4497.4  782.92  4582.3  765.26  4619.4   750.4  4715.2  737.84    4785  737.41
  4822.8  750.28  4826.6  751.74  4866.8  752.44  4947.4  751.46  4954.5  750.86
  4971.2  741.31  4985.8   737.4  4987.3   734.4  5012.7   734.4  5014.2   737.4
  5035.5   748.5  5079.6  749.59  5251.8  750.16  5266.6  754.09  5284.6  762.83
  5313.9  762.33  5326.5  764.12    5378  777.07  5438.5     780  5462.8  784.36
    5469  793.22  5474.2  803.11  5515.2  819.86  5559.3  831.74  5616.4  841.73
#Mann= 8 ,-1 , 0
  4497.4     .09       0  4715.2     .05       0    4785     .09       0
  4822.8     .04       0  4947.4     .09       0  4985.8     .05       0
  5014.2     .09       0  5079.6    .035       0
#XS Ineff= 2 , 0
       0  4824.7     783               0
Permanent Ineff=
       F       F
Bank Sta=4985.8,5014.2
Exp/Cntr=0.3,0.1

Chan Stop Cuts=-1
Use User Specified Reach Order=0
User Specified Reach Order=South Double Cre,Reach-1