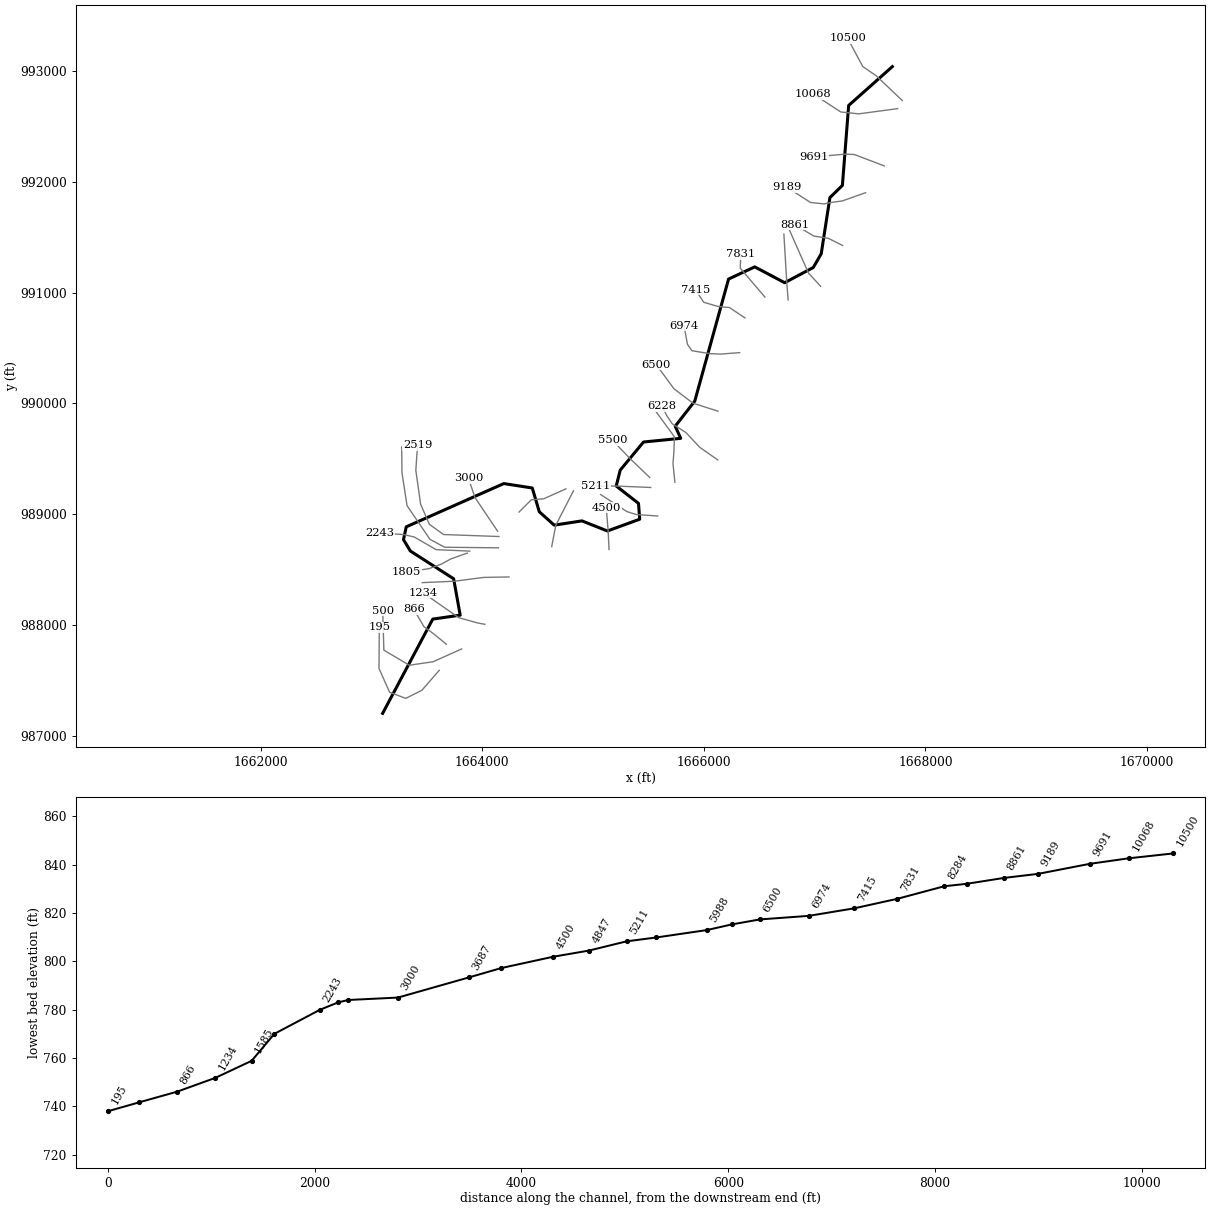
--- lds_mill_crk_hawkins_mill_crk.prj (project) ---

Proj Title=Mill Crk (hawkins mill crk) Limited Detail Study
Current Plan=p01
Default Exp/Contr=0.3,0.1
English Units
Geom File=g01
Flow File=f01
Plan File=p01
Y Axis Title=Elevation
X Axis Title(PF)=Main Channel Distance
X Axis Title(XS)=Station
BEGIN DESCRIPTION:
Mill Crk (hawkins mill crk)
END DESCRIPTION:
DSS Export Rating Curves= 0
DSS Export Rating Curve Sorted= 0
DSS Export Volume Flow Curves= 0
DXF OffsetX= 0
DXF OffsetY= 0
DXF ScaleX= 1
DXF ScaleY= 10

--- lds_mill_crk_hawkins_mill_crk.p01 (plan) ---

Plan Title=Floodway Run
Program Version=3.12
Short Identifier=Floodway
Geom File=g01
Flow File=f01
Subcritical Flow
K Sum by GR= 0
Std Step Tol= 0.01
Critical Tol= 0.01
Num of Std Step Trials= 20
Max Error Tol= 0.3
Flow Tol Ratio= 0.001
Split Flow NTrial= 30
Split Flow Tol= 0.02
Split Flow Ratio= 0.02
Log Output Level= 0
Friction Slope Method= 1
Unsteady Friction Slope Method= 2
Unsteady Bridges Friction Slope Method= 1
Parabolic Critical Depth
Global Vel Dist= 0 , 0 , 0
Global Log Level= 0
CheckData=True
Encroach Param=-1 ,3,3, 2
Encroach River=Mill Crk (hawkin
Encroach Reach=Reach-1
Encroach Node=10500
       4      .7
Encroach Node=10068
       4      .7
Encroach Node=9691
       4      .7
Encroach Node=9189
       4      .7
Encroach Node=8861
       1 4976.47  5009.7
Encroach Node=8500
       4      .7
Encroach Node=8284
       4      .7
Encroach Node=7831
       1  4989.4 5009.82
Encroach Node=7415
       4      .7
Encroach Node=6974
       4      .7
Encroach Node=6500
       4      .7
Encroach Node=6228
       4      .7
Encroach Node=5988
       4      .7
Encroach Node=5500
       4      .7
Encroach Node=5211
       4      .7
Encroach Node=4847
       4      .7
Encroach Node=4500
       4      .7
Encroach Node=4000
       4      .7
Encroach Node=3687
       4      .7
Encroach Node=3000
       1    4960    5035
Encroach Node=2519
       1    4960    5039
Encroach Node=2421
       1    4965    5035
Encroach Node=2243
       4      .7
Encroach Node=1805
       4      .7
Encroach Node=1585
       4      .7
Encroach Node=1234
       4      .5
Encroach Node=866
       4      .3
Encroach Node=500
       4      .3
Encroach Node=195
       4      .5
BEGIN DESCRIPTION:
Floodway Run
END DESCRIPTION:
Computation Interval=1HOUR
Output Interval=1HOUR
Run HTab= 0
Run UNet= 0
Run PostProcess= 0
UNET Theta= 1
UNET Theta Warmup= 1
UNET ZTol= 0.02
UNET ZSATol= 0.05
UNET MxIter= 20
UNET MaxInSteps= 0
UNET DtIC= 0
UNET DtMin= 0
UNET MaxCRTS= 20
UNET WFStab= 2
UNET SFStab= 1
UNET WFX= 1
UNET SFX= 1
UNET DSS MLevel= 4
UNET DZMax Abort= 100
UNET Convert EG Bridges=-1
UNET Use Existing IB Tables=-1
UNET Froude Reduction=False
UNET Froude Limit= 1
UNET Froude Power= 10
Instantaneous Interval=1HOUR
Write IC File= 0
Echo Input=False
Echo Output=False
Write Detailed= 0
Detailed Automatic Start=False, 10

--- lds_mill_crk_hawkins_mill_crk.f01 (steady flow) ---

Flow Title=Floodway
Number of Profiles=2
Profile Names=100-year,100-FW
River Rch & RM= Mill Crk (hawkin,Reach-1,10500
    1692    1692
River Rch & RM= Mill Crk (hawkin,Reach-1,10068
    1769    1769
River Rch & RM= Mill Crk (hawkin,Reach-1,5988
    1904    1904
River Rch & RM= Mill Crk (hawkin,Reach-1,3000
    1945    1945
Boundary for River Rch & Prof#=Mill Crk (hawkin,Reach-1,1
Up Type=0
Dn Type=3
Dn Slope=0.012
Boundary for River Rch & Prof#=Mill Crk (hawkin,Reach-1,2
Up Type=0
Dn Type=3
Dn Slope=0.012

--- lds_mill_crk_hawkins_mill_crk.g01 (geometry) ---

Geom Title=Existing Conditions
Program Version=3.11

River Reach=Mill Crk (hawkin,Reach-1
Reach XY= 30
      1667701.13       993042.38      1667306.88       992691.56
      1667250.38       991969.38      1667137.63       991859.31
      1667059.25       991351.75      1666987.63       991227.94
      1666729.13       991090.38       1666459.5       991233.44
      1666222.88       991123.38       1665917.5       990020.13
      1665741.38       989794.56      1665790.88        989684.5
      1665455.25        989651.5      1665244.75         989397.
        1665209.       989253.94      1665409.88       989097.13
      1665420.88       988954.06      1665129.04       988847.63
       1664899.5       988938.94      1664649.13       988900.38
      1664514.38       989021.44      1664451.13       989236.06
      1664193.88       989275.94       1663313.5       988885.25
      1663288.63       988769.69      1663350.63       988666.56
      1663741.25       988416.19      1663800.38       988087.44
      1663552.75       988051.63      1663100.25       987200.13

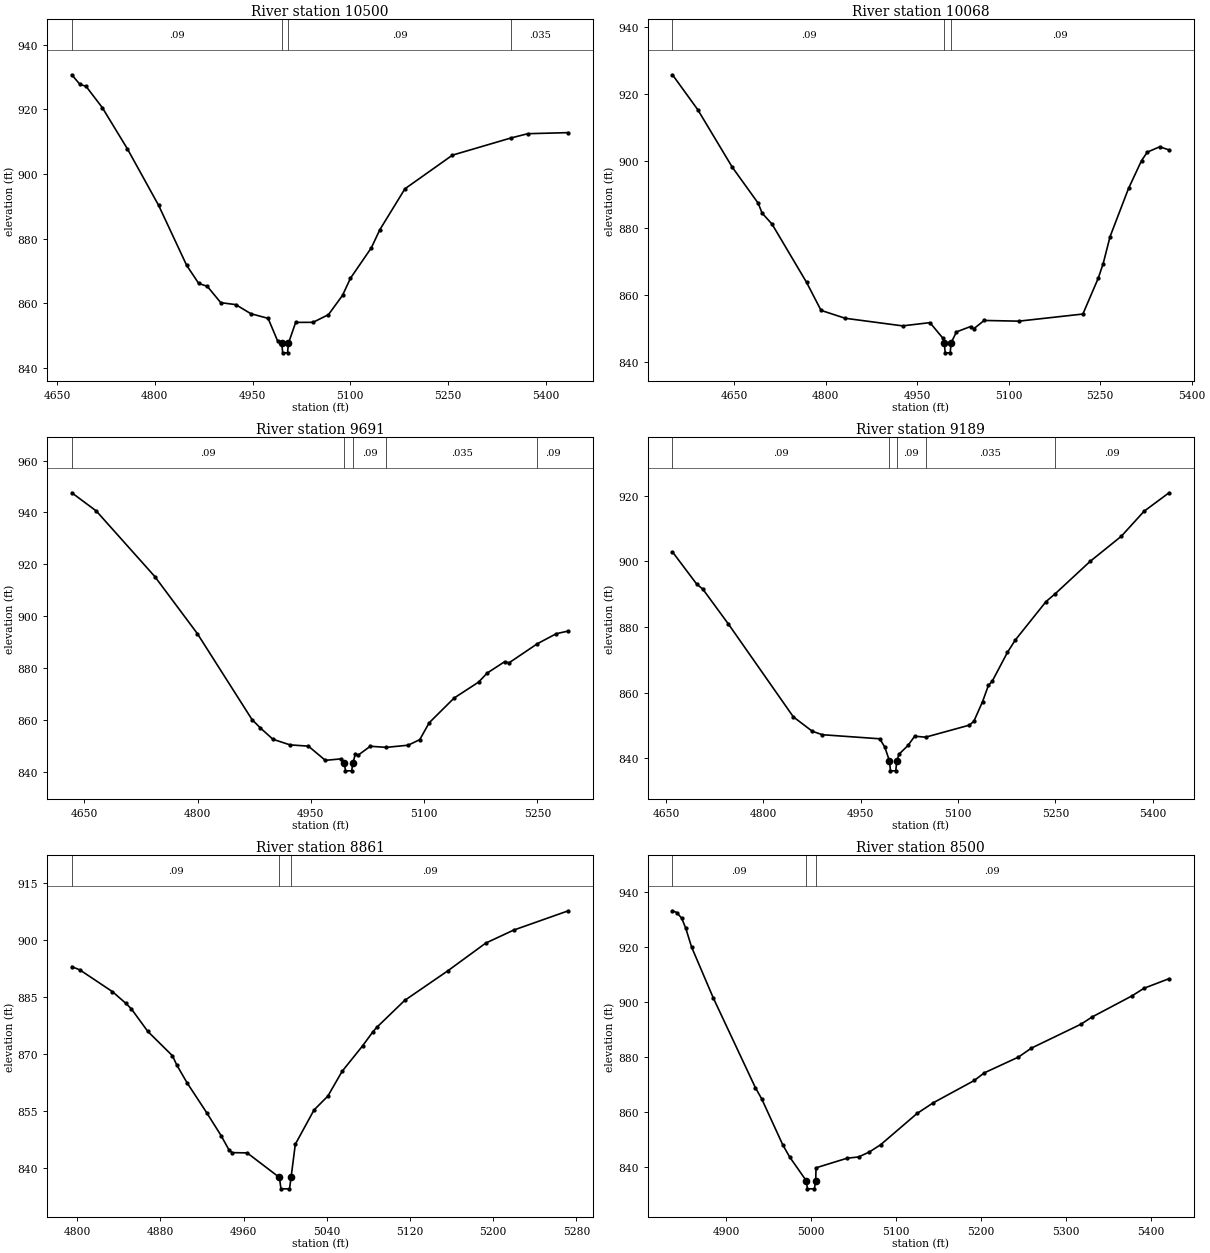
Type RM Length L Ch R = 1 ,10500   ,432,432,432
BEGIN DESCRIPTION:
Mill Crk (hawkins mill crk) 22.0
END DESCRIPTION:
XS GIS Cut Line= 4
      1667791.55       992735.51       1667554.1       992960.69
      1667434.45       993043.13      1667297.64       993297.87
#Sta/Elev= 30
  4672.8  930.69  4685.1  927.75  4694.7   927.1  4719.5  920.55  4757.9  907.82
    4806  890.26    4849  871.69  4867.5  866.09  4880.6  865.21  4901.3  860.14
  4924.3  859.54  4947.5  856.72  4973.9  855.29  4988.5   848.3  4994.8  847.61
  4996.3  844.61  5003.7  844.61  5005.2  847.61  5016.2  854.03  5042.9  854.06
  5066.5  856.43  5088.1  862.41  5100.3  867.71  5132.3  877.13  5145.3  882.72
  5183.8  895.39  5256.7  905.81  5346.5  911.13  5372.4  912.45  5434.5  912.78
#Mann= 4 ,-1 , 0
  4672.8     .09       0  4994.8     .05       0  5005.2     .09       0
  5346.5    .035       0
Bank Sta=4994.8,5005.2
XS Rating Curve= 0
Exp/Cntr=0.3,0.1

Type RM Length L Ch R = 1 ,10068   ,377,377,377
BEGIN DESCRIPTION:
Mill Crk (hawkins mill crk) 21.0
END DESCRIPTION:
XS GIS Cut Line= 4
      1667748.78       992662.79      1667398.04       992615.74
       1667235.5       992632.85      1666987.41       992795.39
#Sta/Elev= 30
  4548.9  925.71  4590.3  915.28  4646.9  898.08  4689.4  887.31  4695.7  884.39
  4712.2  881.03  4768.7  863.64  4792.4  855.28  4832.1  852.92  4926.1  850.65
  4970.9  851.62  4991.9  847.02  4994.4  845.59  4995.9  842.59  5004.1  842.59
  5005.6  845.59  5014.4  848.85  5037.4  850.45  5042.5  849.76  5059.8  852.27
  5116.5  852.06  5221.6  854.19  5246.7  864.87  5254.8  869.23  5266.2  877.36
  5296.4  891.73  5317.7  900.04  5327.2  902.59  5347.6  904.19  5362.8  903.24
#Mann= 3 ,-1 , 0
  4548.9     .09       0  4994.4     .05       0  5005.6     .09       0
Bank Sta=4994.4,5005.6
XS Rating Curve= 0
Exp/Cntr=0.3,0.1

Type RM Length L Ch R = 1 ,9691    ,502,502,502
BEGIN DESCRIPTION:
Mill Crk (hawkins mill crk) 20.0
END DESCRIPTION:
XS GIS Cut Line= 4
      1667629.01       992145.23      1667359.54       992247.89
      1667278.27       992252.16      1666991.69        992226.5
#Sta/Elev= 30
  4633.5  947.59  4665.9  940.57  4743.5  915.24  4799.7  893.27  4872.1   860.1
  4882.9  856.92  4899.8  852.49  4922.4  850.32  4946.8  849.83  4969.2  844.35
  4990.6  844.93  4994.4   843.3  4995.9   840.3  5004.1   840.3  5005.6   843.3
  5009.1  846.81  5012.4  846.28  5028.7  849.78    5050  849.36  5078.9  850.19
  5094.3  852.35  5106.7  858.84  5139.7  868.38  5172.2  874.55  5183.5  878.02
  5206.5  882.38  5212.6     882    5250  889.35  5275.1  893.22    5291  894.25
#Mann= 5 ,-1 , 0
  4633.5     .09       0  4994.4     .05       0  5005.6     .09       0
    5050    .035       0    5250     .09       0
Bank Sta=4994.4,5005.6
XS Rating Curve= 0
Exp/Cntr=0.3,0.1

Type RM Length L Ch R = 1 ,9189    ,328,328,328
BEGIN DESCRIPTION:
Mill Creek (hawkins mill crk) 19.5
END DESCRIPTION:
XS GIS Cut Line= 6
      1667459.79       991903.52      1667248.36       991828.63
      1667147.04       991815.42      1667085.38        991802.2
      1666962.04       991815.42       1666750.6       991951.97
#Sta/Elev= 30
    4660  902.88  4697.2   893.1  4706.8  891.52    4746  880.94  4846.3  852.58
  4875.4  848.21  4890.9  847.15  4979.4  845.91  4987.2  843.38  4994.4  839.14
  4995.9  836.14  5004.1  836.14  5005.6  839.14  5009.1  841.23  5022.9  843.87
  5033.2   846.7    5050   846.4  5117.5  850.07  5124.5  851.28  5137.8  857.22
  5146.9  862.21  5152.6  863.42  5176.2  872.26  5188.2     876  5235.7  887.75
    5250  890.16  5303.4  899.96  5351.7  907.66  5386.7  915.27  5425.2  920.91
#Mann= 5 ,-1 , 0
    4660     .09       0  4994.4     .05       0  5005.6     .09       0
    5050    .035       0    5250     .09       0
Bank Sta=4994.4,5005.6
XS Rating Curve= 0
Exp/Cntr=0.3,0.1

Type RM Length L Ch R = 1 ,8861    ,361,361,361
BEGIN DESCRIPTION:
Mill Crk (hawkins mill crk) 19.0
END DESCRIPTION:
XS GIS Cut Line= 4
      1667252.61       991426.63      1667124.29       991490.79
      1666991.69       991512.18      1666820.59       991614.84
#Sta/Elev= 30
  4794.8     893  4802.5  892.15  4833.9  886.41  4846.7  883.35    4852   881.9
  4867.9  875.93  4891.6  869.52  4895.7   867.1  4905.6  862.41  4924.6  854.48
  4938.3  848.51  4945.9  844.73    4949  844.01  4963.4  843.94  4994.4  837.47
  4995.9  834.47  5004.1  834.47  5005.6  837.47  5009.7  846.22  5027.7  855.25
    5041  858.91  5054.7  865.43  5074.3  872.11  5084.4  875.88    5088  877.01
  5114.8   884.1  5156.1  891.86  5192.8  899.21  5219.7  902.64  5272.2  907.72
#Mann= 3 ,-1 , 0
  4794.8     .09       0  4994.4     .05       0  5005.6     .09       0
Bank Sta=4994.4,5005.6
XS Rating Curve= 0
Exp/Cntr=0.3,0.1

Type RM Length L Ch R = 1 ,8500    ,216,216,216
BEGIN DESCRIPTION:
Mill Crk (hawkins mill crk) 18.0
END DESCRIPTION:
XS GIS Cut Line= 3
      1667054.12       991057.68      1666944.02       991177.91
      1666773.54       991563.51
#Sta/Elev= 30
    4837  933.26    4842  932.63  4847.9  930.52  4852.7  926.83  4859.4  920.12
    4885  901.55  4934.6  868.86    4942  864.81  4966.8  848.08    4975  843.61
  4994.4  835.04  4995.9  832.04  5004.1  832.04  5005.6  835.04    5006   839.7
  5042.8  843.21    5056  843.64  5068.8  845.46  5082.1  848.11    5125  859.49
  5143.9  863.34  5192.3  871.48  5204.2  874.28  5244.3     880  5259.6  883.27
  5318.1     892  5330.8  894.56  5378.2  902.32  5392.1  905.05  5421.6  908.54
#Mann= 3 ,-1 , 0
    4837     .09       0  4994.4     .05       0  5005.6     .09       0
Bank Sta=4994.4,5005.6
XS Rating Curve= 0
Exp/Cntr=0.3,0.1

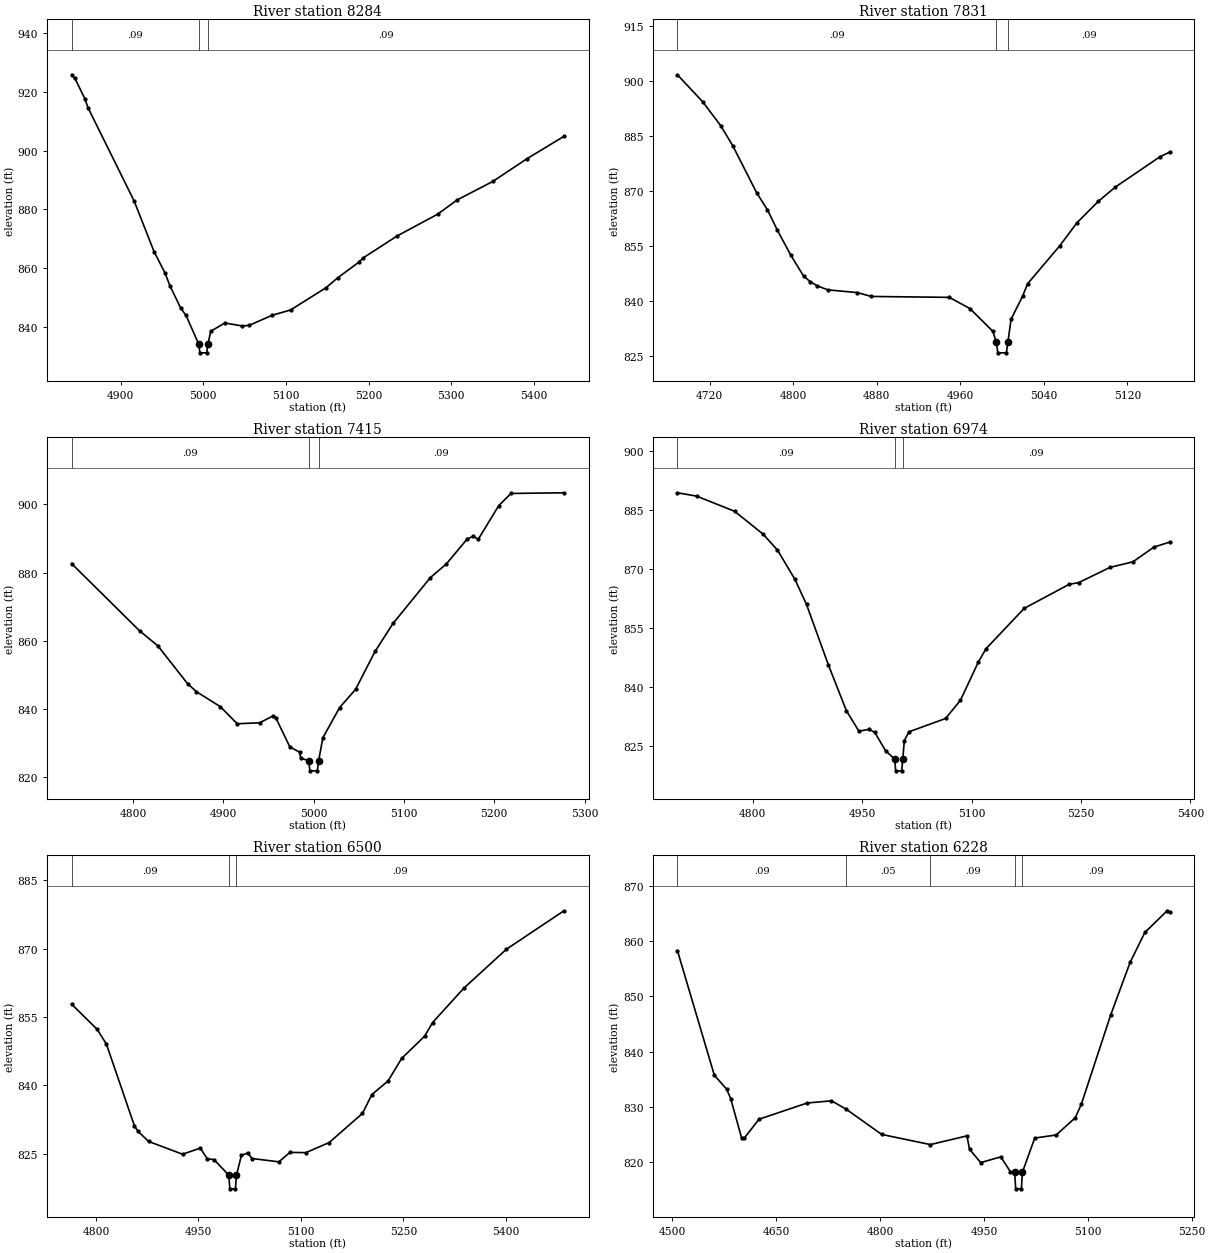
Type RM Length L Ch R = 1 ,8284    ,453,453,453
BEGIN DESCRIPTION:
Mill Crk (hawkins mill crk) 17.0
END DESCRIPTION:
XS GIS Cut Line= 3
      1666760.71       990934.74      1666747.88       991097.28
      1666722.21       991529.29
#Sta/Elev= 30
  4840.6  925.91  4844.6  924.71  4856.7   917.7  4860.5  914.66  4916.3  882.83
  4940.4  865.56  4953.7  858.24  4959.7  853.84  4972.7  846.26  4979.1  843.79
  4994.4  834.03  4995.9  831.03  5004.1  831.03  5005.6  834.03    5009   838.4
    5026  841.21  5047.4  840.19  5055.5  840.41  5083.6  843.88  5105.5  845.64
  5148.4  853.24  5162.5  856.61  5188.2  861.96  5193.2  863.38  5234.6  870.93
  5283.4  878.31  5307.2  883.21  5350.3  889.51  5391.8  897.29  5436.4   904.9
#Mann= 3 ,-1 , 0
  4840.6     .09       0  4994.4     .05       0  5005.6     .09       0
Bank Sta=4994.4,5005.6
XS Rating Curve= 0
Exp/Cntr=0.3,0.1

Type RM Length L Ch R = 1 ,7831    ,416,416,416
BEGIN DESCRIPTION:
Mill Crk (hawkins mill crk) 16.0
END DESCRIPTION:
XS GIS Cut Line= 3
      1666551.12        990960.4       1666328.7       991221.32
      1666332.97       991349.64
#Sta/Elev= 30
  4689.2  901.64  4713.4  894.28  4730.6  887.79  4742.2   882.3    4765  869.51
  4775.3  864.87  4784.7  859.38  4797.6  852.54    4810  846.76  4816.1  845.29
  4823.2  844.09  4833.2  843.02  4861.4  842.27  4874.8  841.22  4949.5  840.97
  4969.2  837.92  4991.1  831.73  4994.4  828.85  4995.9  825.85  5004.1  825.85
  5005.6  828.85  5008.6  835.01  5019.8   841.4  5024.4  844.67  5055.4   855.1
  5071.6  861.28  5092.2  867.17  5108.2  870.99  5151.2  879.31  5160.5  880.57
#Mann= 3 ,-1 , 0
  4689.2     .09       0  4994.4     .05       0  5005.6     .09       0
Bank Sta=4994.4,5005.6
XS Rating Curve= 0
Exp/Cntr=0.3,0.1

Type RM Length L Ch R = 1 ,7415    ,441,441,441
BEGIN DESCRIPTION:
Mill Crk (hawkins mill crk) 15.0
END DESCRIPTION:
XS GIS Cut Line= 5
      1666371.47        990772.2      1666230.32        990866.3
      1666131.94       990874.85      1665999.34       990913.35
      1665922.35       991028.84
#Sta/Elev= 30
    4732  882.65  4807.2  862.98  4827.6  858.53  4860.4  847.47  4870.2  845.12
  4896.8  840.71  4915.4  835.72  4940.2     836    4955  838.01  4958.1  837.49
  4973.7  828.92  4984.5  827.39  4985.7  825.62  4994.4  824.92  4995.9  821.92
  5004.1  821.92  5005.6  824.92  5010.2   831.6  5028.8  840.46  5046.4  845.77
    5068   856.9    5088  865.14  5129.3  878.55  5147.1  882.59  5170.1  889.89
    5177  890.68  5182.2  889.74  5204.9  899.61  5218.5  903.21  5277.2  903.41
#Mann= 3 ,-1 , 0
    4732     .09       0  4994.4     .05       0  5005.6     .09       0
Bank Sta=4994.4,5005.6
XS Rating Curve= 0
Exp/Cntr=0.3,0.1

Type RM Length L Ch R = 1 ,6974    ,474,474,474
BEGIN DESCRIPTION:
Mill Creek (hawkins mill crk) 14.5
END DESCRIPTION:
XS GIS Cut Line= 6
      1666323.33        990458.7      1666147.13       990445.49
      1666050.22       990449.89      1665891.64       990476.32
        1665852.       990533.59      1665821.17       990700.97
#Sta/Elev= 30
  4696.6  889.42    4723  888.57  4775.1  884.71  4814.2  878.89  4833.8  874.87
  4857.7  867.43  4873.6  861.05  4903.6  845.69  4928.2   834.1  4945.4  828.86
  4959.1  829.33  4967.2  828.56    4982  823.89  4994.4  821.79  4995.9  818.79
  5004.1  818.79  5005.6  821.79  5007.7  826.48    5014   828.7  5064.3  832.09
  5084.7  836.73  5109.2  846.44  5119.8  849.83  5172.1  860.06  5233.8  866.18
  5246.7  866.59  5289.4  870.45  5321.2  871.89  5349.8  875.61  5371.6   876.9
#Mann= 3 ,-1 , 0
  4696.6     .09       0  4994.4     .05       0  5005.6     .09       0
Bank Sta=4994.4,5005.6
XS Rating Curve= 0
Exp/Cntr=0.3,0.1

Type RM Length L Ch R = 1 ,6500    ,272,272,272
BEGIN DESCRIPTION:
Mill Crk (hawkins mill crk) 14.0
END DESCRIPTION:
XS GIS Cut Line= 4
      1666127.66       989929.56      1665903.08       990001.59
      1665729.83       990132.48       1665571.6       990348.74
#Sta/Elev= 30
  4764.2  857.82  4801.6  852.29  4815.1  849.08  4856.3  831.08  4861.4  829.93
  4876.9  827.71  4926.7   824.9  4952.6  826.24  4962.9  823.91  4972.7  823.71
  4994.4  820.31  4995.9  817.31  5004.1  817.31  5005.6  820.31  5012.9  824.67
  5021.9  825.17 5028.56  823.96  5067.7  823.23  5083.9   825.3  5107.3  825.25
  5141.3  827.46    5190  833.84  5203.9  837.99  5227.5  840.96  5247.6  845.94
  5281.2  850.79  5292.7  853.77  5338.5  861.32  5400.8  869.85  5485.1  878.29
#Mann= 3 ,-1 , 0
  4764.2     .09       0  4994.4    .045       0  5005.6     .09       0
Bank Sta=4994.4,5005.6
XS Rating Curve= 0
Exp/Cntr=0.3,0.1

Type RM Length L Ch R = 1 ,6228    ,240,240,240
BEGIN DESCRIPTION:
Mill Creek (hawkins mill crk) 13.5
END DESCRIPTION:
XS GIS Cut Line= 6
      1666125.11       989489.62      1665962.12       989604.15
      1665838.79        989736.3      1665715.45       989815.59
      1665666.99       989886.07      1665622.95       989974.16
#Sta/Elev= 30
  4507.6  858.26  4560.9  835.75  4578.7  833.23  4584.5  831.53  4600.3  824.39
  4603.8  824.34  4625.3   827.8    4695  830.74    4730  831.13    4751  829.64
  4802.5  825.06  4872.7  823.23  4925.5   824.8  4929.3  822.37  4945.4  819.98
  4974.4  821.01  4988.4  818.31  4994.4  818.24  4995.9  815.24  5004.1  815.24
  5005.6  818.24  5023.4  824.41  5054.3  824.96  5081.9  828.07  5090.7  830.54
  5133.2   846.7  5161.1  856.13  5182.3  861.52  5214.5  865.44  5218.3  865.25
#Mann= 5 ,-1 , 0
  4507.6     .09       0    4751     .05       0  4872.7     .09       0
  4994.4    .045       0  5005.6     .09       0
Bank Sta=4994.4,5005.6
XS Rating Curve= 0
Exp/Cntr=0.3,0.1

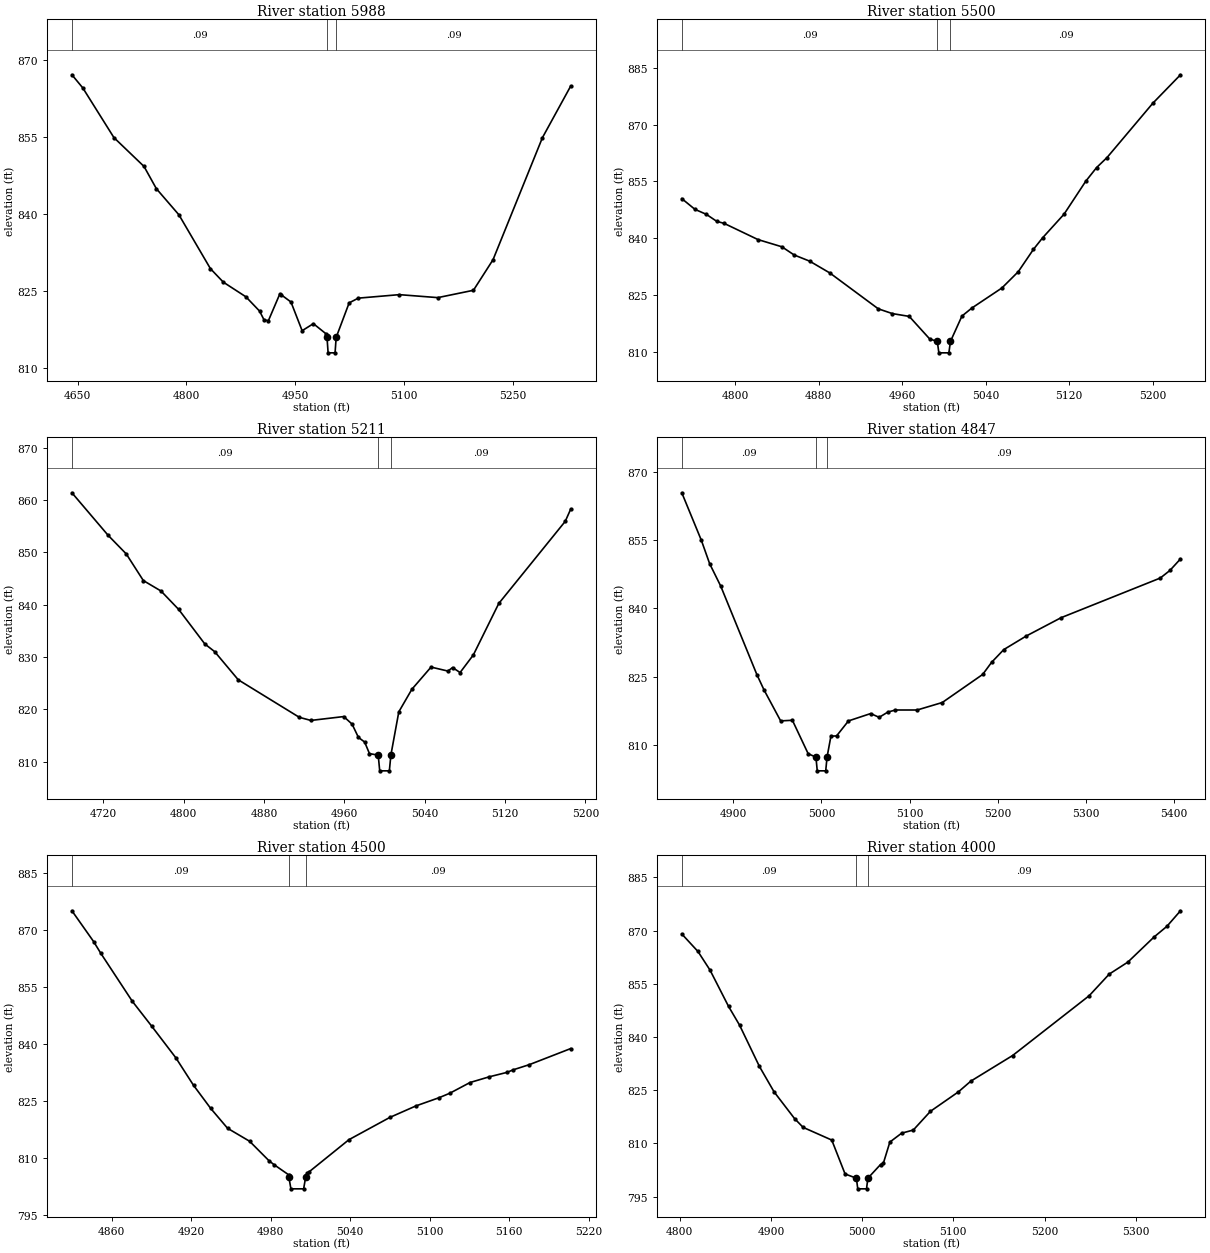
Type RM Length L Ch R = 1 ,5988    ,488,488,488
BEGIN DESCRIPTION:
Mill Crk (hawkins mill crk) 13.0
END DESCRIPTION:
XS GIS Cut Line= 5
      1665738.42       989287.95      1665721.31       989454.77
      1665729.87       989570.26      1665734.14       989698.58
       1665571.6         989921.
#Sta/Elev= 30
  4642.1  867.05  4657.1  864.49    4700  854.82  4741.5   849.2  4758.5  844.87
  4789.6  839.78    4833   829.3  4850.8  826.67  4881.9  823.82  4900.8  821.03
  4906.9  819.32  4912.9  819.17  4928.5  824.33  4930.2  824.25    4944  822.81
  4959.4  817.22  4974.9  818.59  4992.2  816.63  4993.7  815.91  4995.2  812.91
  5004.8  812.91  5006.3  815.91  5024.2  822.64  5036.8  823.56  5093.3  824.24
  5146.4  823.66  5195.5  825.09  5222.5  831.04  5290.6  854.81  5329.4  864.81
#Mann= 3 ,-1 , 0
  4642.1     .09       0  4993.7     .05       0  5006.3     .09       0
Bank Sta=4993.7,5006.3
XS Rating Curve= 0
Exp/Cntr=0.3,0.1

Type RM Length L Ch R = 1 ,5500    ,289,289,289
BEGIN DESCRIPTION:
Mill Crk (hawkins mill crk) 12.0
END DESCRIPTION:
XS GIS Cut Line= 3
      1665511.72       989330.73      1665330.44       989504.62
      1665173.81       989668.64
#Sta/Elev= 30
  4748.8  850.48  4761.4  847.66  4772.3  846.35  4782.3   844.5  4789.4  843.96
  4821.8   839.7  4844.7   837.8  4856.5  835.64  4871.3  834.02  4890.7   830.9
  4937.1  821.46  4950.6   820.2  4966.8  819.46  4986.4  813.52  4993.7  812.86
  4995.2  809.86  5004.8  809.86  5006.3  812.86  5017.3  819.54  5026.7  821.64
  5055.6  826.94  5071.3  831.23  5085.8   837.1  5094.6  840.15  5115.2  846.39
    5136  855.07  5146.4  858.67  5156.4  861.31  5200.3  875.62  5226.8  883.11
#Mann= 3 ,-1 , 0
  4748.8     .09       0  4993.7     .05       0  5006.3     .09       0
Bank Sta=4993.7,5006.3
XS Rating Curve= 0
Exp/Cntr=0.3,0.1

Type RM Length L Ch R = 1 ,5211    ,364,364,364
BEGIN DESCRIPTION:
Mill Crk (hawkins mill crk) 11.0
END DESCRIPTION:
XS GIS Cut Line= 3
      1665520.28        989240.9      1665203.75       989253.74
       1665024.1       989253.74
#Sta/Elev= 30
  4688.8  861.37  4724.9  853.23  4742.9  849.69  4759.9   844.6  4777.5   842.6
  4795.1  839.08  4821.1  832.49  4830.9  831.02  4854.4  825.64  4915.2  818.47
  4926.7  817.88  4959.4  818.62  4967.7  817.17    4974  814.64  4980.2  813.75
    4985  811.54  4993.7  811.25  4995.2  808.25  5004.8  808.25  5006.3  811.25
  5014.2  819.52  5027.2  823.83  5046.3  828.07  5063.1  827.31  5067.7  827.98
  5075.2  827.03  5088.4  830.39  5113.7  840.22  5179.9  855.92  5185.2   858.2
#Mann= 3 ,-1 , 0
  4688.8     .09       0  4993.7     .05       0  5006.3     .09       0
Bank Sta=4993.7,5006.3
XS Rating Curve= 0
Exp/Cntr=0.3,0.1

Type RM Length L Ch R = 1 ,4847    ,347,347,347
BEGIN DESCRIPTION:
Mill Creek (hawkins mill crk) 10.5
END DESCRIPTION:
XS GIS Cut Line= 4
       1665583.3       988983.06      1665389.48       988996.27
      1665305.79        989022.7      1665067.93       989176.88
#Sta/Elev= 30
  4841.6  865.35  4863.8  854.92  4873.2   849.8  4885.7  844.92  4926.7  825.53
  4934.8  822.17  4953.7  815.37    4967  815.51  4984.9  808.18  4993.7  807.43
  4995.2  804.43  5004.8  804.43  5006.3  807.43  5010.7  812.03  5017.1  812.08
  5030.6  815.37  5055.8  816.98  5065.4  816.15  5075.3  817.31  5083.9  817.76
  5108.5  817.76    5137   819.4  5182.8  825.55  5192.9   828.2  5206.7  830.99
  5232.2  833.97  5271.7  837.98  5384.2  846.67  5395.1  848.33  5407.1  850.86
#Mann= 3 ,-1 , 0
  4841.6     .09       0  4993.7     .05       0  5006.3     .09       0
Bank Sta=4993.7,5006.3
XS Rating Curve= 0
Exp/Cntr=0.3,0.1

Type RM Length L Ch R = 1 ,4500    ,500,500,500
BEGIN DESCRIPTION:
Mill Crk (hawkins mill crk) 10.0
END DESCRIPTION:
XS GIS Cut Line= 3
      1665143.87       988680.57      1665135.92       988850.46
      1665118.79       989056.04
#Sta/Elev= 30
  4829.9  875.12  4846.3     867  4851.7  863.92  4875.5  851.27  4890.3  844.64
  4908.3  836.41  4921.7  829.14  4934.6  823.08  4947.4  817.82    4964  814.41
  4978.7  809.26  4982.5  808.23  4993.4  805.59  4993.7  804.87  4995.2  801.87
  5004.8  801.87  5006.3  804.87  5007.4  806.03  5008.5  806.23    5039  814.82
  5069.9  820.69  5089.6  823.72  5106.9  825.86  5115.1  827.05  5130.4  829.88
    5145  831.39  5158.3  832.55  5163.1  833.24  5175.2  834.59  5206.3  838.81
#Mann= 3 ,-1 , 0
  4829.9     .09       0  4993.7     .05       0  5006.3     .09       0
Bank Sta=4993.7,5006.3
XS Rating Curve= 0
Exp/Cntr=0.3,0.1

Type RM Length L Ch R = 1 ,4000    ,313,313,313
BEGIN DESCRIPTION:
Mill Crk (hawkins mill crk) 9.0
END DESCRIPTION:
XS GIS Cut Line= 3
      1664626.31       988706.23      1664663.79       988900.38
      1664823.07       989210.96
#Sta/Elev= 30
  4802.3  869.06    4820  864.13  4833.2  858.89  4853.6  848.62  4865.6  843.37
  4887.4  831.71  4903.4  824.57  4925.9  817.02  4935.3  814.54  4966.7  810.96
  4981.3   801.4  4993.7  800.21  4995.2  797.21  5004.8  797.21  5006.3  800.21
  5020.2  804.07  5023.3  804.46  5030.4   810.4  5043.3   812.9  5056.1  813.79
  5074.9  819.07  5105.4  824.52  5119.2  827.58    5165   834.8  5248.9  851.65
  5270.9  857.75  5291.3  861.13    5320   868.2  5334.1  871.21    5349   875.6
#Mann= 3 ,-1 , 0
  4802.3     .09       0  4993.7     .05       0  5006.3     .09       0
Bank Sta=4993.7,5006.3
XS Rating Curve= 0
Exp/Cntr=0.3,0.1

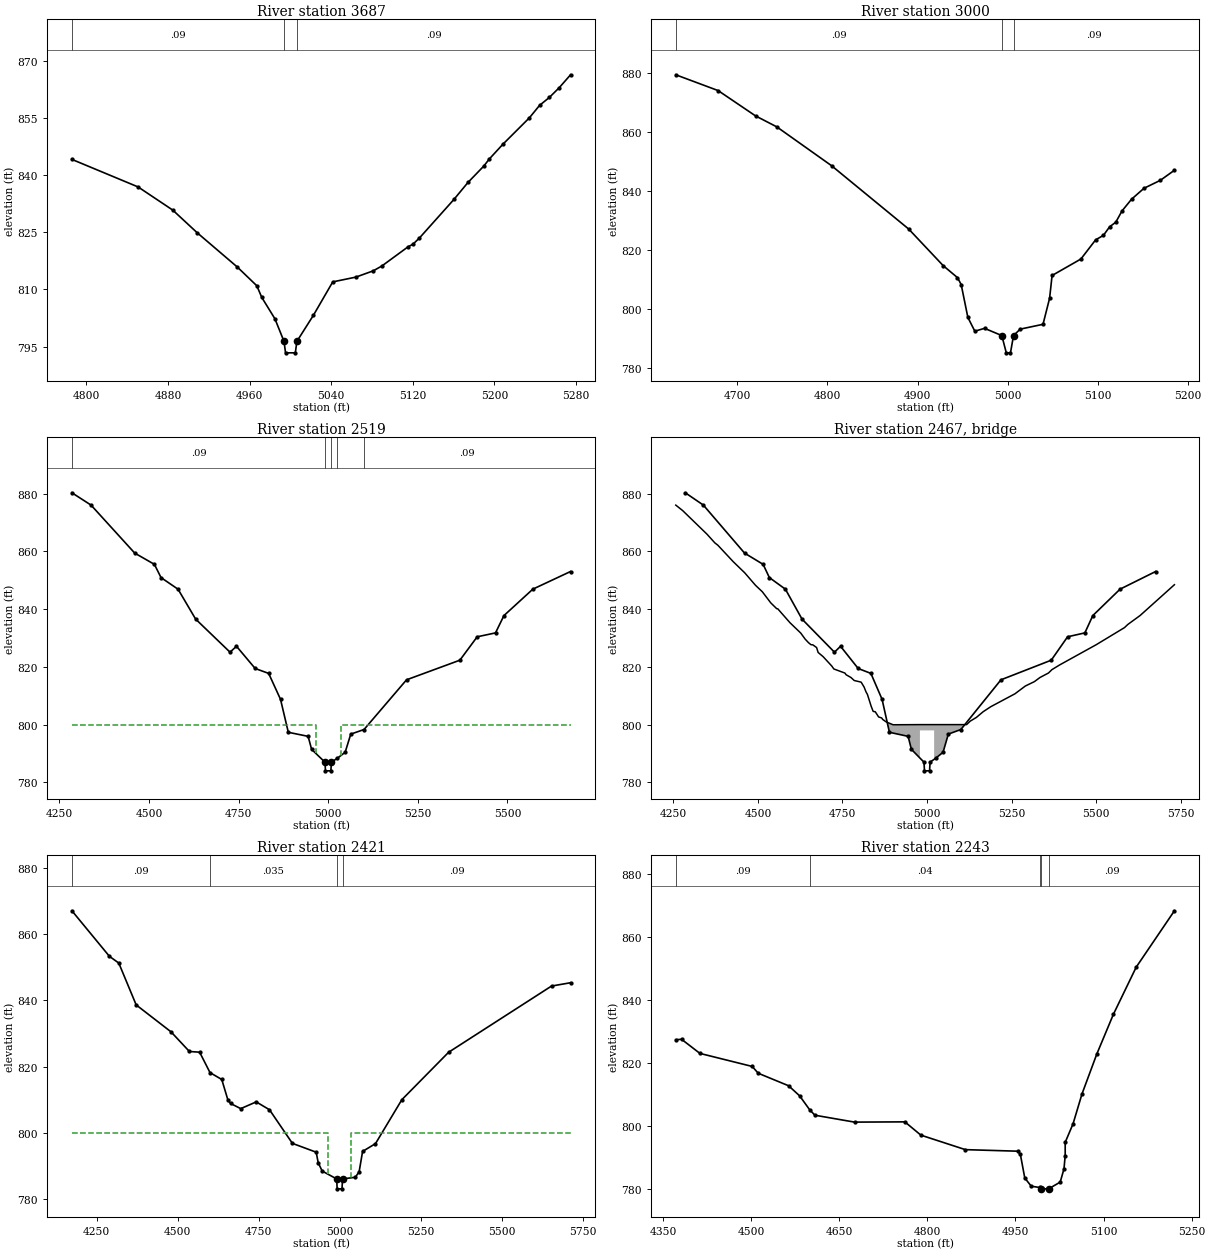
Type RM Length L Ch R = 1 ,3687    ,687,687,687
BEGIN DESCRIPTION:
Mill Crk (hawkins mill crk) 8.0
END DESCRIPTION:
XS GIS Cut Line= 4
      1664331.17       989018.48      1664442.38       989129.69
      1664553.59       989138.25      1664754.63       989228.07
#Sta/Elev= 30
  4785.7  844.13  4850.6   836.9  4884.6  830.82  4908.6  824.86  4947.9  815.87
    4967  810.96  4971.9  807.89  4984.8  802.27  4993.7  796.34  4995.2  793.34
  5004.8  793.34  5006.3  796.34  5022.5  803.19  5041.5  811.97  5064.1  813.22
  5081.2  814.87  5089.7  816.15  5115.5  821.21    5120  821.83  5126.5  823.49
  5160.3  833.61  5174.1  838.08  5189.6  842.37    5195  844.23  5208.2  848.07
  5234.4  855.07  5244.3  858.31  5253.9   860.4  5263.6  862.96  5274.7  866.35
#Mann= 3 ,-1 , 0
  4785.7     .09       0  4993.7     .05       0  5006.3     .09       0
Bank Sta=4993.7,5006.3
XS Rating Curve= 0
Exp/Cntr=0.3,0.1

Type RM Length L Ch R = 1 ,3000    ,481,481,481
BEGIN DESCRIPTION:
Mill Crk (hawkins mill crk) 7.0
END DESCRIPTION:
XS GIS Cut Line= 3
      1664138.34       988845.53      1663932.87       989151.29
      1663874.06       989326.76
#Sta/Elev= 30
  4631.6  879.33  4678.6  873.97  4720.1  865.39  4743.8  861.65  4804.5  848.49
  4890.1  827.01  4928.4  814.59  4944.3  810.51  4948.4  808.17 4955.81  797.03
 4963.54  792.34 4974.33  793.31  4993.5  790.86 4998.48     785 5003.12     785
  5006.5  790.86  5013.9  793.04 5039.24  794.68 5046.56  803.55  5049.3  811.24
  5081.3  816.83  5097.6  823.32  5106.3  824.86  5113.2  827.77    5120  829.31
  5126.9  833.13  5137.5  837.11  5151.3  840.82  5169.5  843.53  5185.1  846.94
#Mann= 3 ,-1 , 0
  4631.6     .09       0  4993.5     .05       0  5006.5     .09       0
Bank Sta=4993.5,5006.5
XS Rating Curve= 0
Exp/Cntr=0.5,0.3

Type RM Length L Ch R = 1 ,2519    ,98,98,98
BEGIN DESCRIPTION:
Tom Shelton Rd. SR-1647 - US
END DESCRIPTION:
XS GIS Cut Line= 6
      1664150.68       988797.75      1663650.21       988815.62
      1663522.54       988907.54      1663443.39       989088.83
      1663399.98       989395.24       1663415.3       989619.94
#Sta/Elev= 30
  4285.3  880.25  4338.7  875.98  4460.4  859.38  4515.4  855.47  4533.8   850.9
  4581.3  846.87  4630.4  836.52  4726.3  825.07  4744.3  827.12  4796.4  819.43
    4834  817.73  4867.1  808.75  4888.8  797.34  4944.1  795.94 4953.76  791.44
    4991     787  4992.5     784  5007.5     784    5009     787 5025.41  788.35
 5047.33  790.41    5063  796.71    5100   798.3  5218.6  815.51  5367.3   822.3
  5415.6   830.4  5466.7  831.75  5490.2  837.74  5570.8  846.89    5676     853
#Mann= 5 ,-1 , 0
  4285.3     .09       0    4991    .055       0    5009     .09       0
 5025.41    .035       0    5100     .09       0
#XS Ineff= 2 , 0
       0    4965     800    5035       0     800
Permanent Ineff=
       F       F
Bank Sta=4991,5009
XS Rating Curve= 0
Exp/Cntr=0.5,0.3

Type RM Length L Ch R = 3 ,2467    ,,,
BEGIN DESCRIPTION:
Tom Shelton Rd. SR-1647
Structure ID: Tom Shelton Rd
Approximate Survey Structure
END DESCRIPTION:
Bridge Culvert--1,0,-1,-1, 0
Deck Dist Width WeirC Skew NumUp NumDn MinLoCord MaxHiCord MaxSubmerge Is_Ogee
34,36,3,0, 60, 60, , , , 0, 1,1,,
  4257.1  4277.4  4349.3  4372.6  4381.4  4426.8  4461.1    4493    4513    4538
  4555.6  4558.5  4594.7  4626.6  4639.4  4649.4  4656.7  4662.4  4673.5    4678
  4692.8  4718.4  4724.5  4757.1    4761  4775.2  4784.7  4805.2    4814  4819.6
  4823.8  4834.7  4840.7    4847  4856.8  4866.1  4868.8  4879.5  4899.8    4979
    4979    5021    5021    5117  5127.6  5145.8  5165.8  5188.6    5260  5290.8
  5317.3  5334.1  5359.2  5369.4  5392.3  5500.7    5584  5593.6  5630.1  5731.5
  875.98  874.09  865.93  862.91  862.11  856.42  852.53   848.2  845.99  842.14
  840.12  840.11  835.28  831.69  829.63  828.38  827.67  827.61  826.68  824.98
  823.52  820.27  819.26  817.85  817.24   816.3  815.27   814.7  812.99  811.33
  810.44  806.41  804.58  804.44  802.66  802.29   801.8  800.92  799.95     800
     800     800     800     800   801.2  802.48  804.45  806.21  810.67  813.37
  814.87  816.32  817.87  819.04  820.67  827.69  833.59  834.66  837.77  848.43
     764     764     764     764     764     764     764     764     764     764
     764     764     764     764     764     764     764     764     764     764
     764     764     764     764     764     764     764     764     764     764
     764     764     764     764     764     764     764     764     764     764
     798     798     764     764     764     764     764     764     764     764
     764     764     764     764     764     764     764     764     764     764
  4257.1  4277.4  4349.3  4372.6  4381.4  4426.8  4461.1    4493    4513    4538
  4555.6  4558.5  4594.7  4626.6  4639.4  4649.4  4656.7  4662.4  4673.5    4678
  4692.8  4718.4  4724.5  4757.1    4761  4775.2  4784.7  4805.2    4814  4819.6
  4823.8  4834.7  4840.7    4847  4856.8  4866.1  4868.8  4879.5  4899.8    4979
    4979    5021    5021    5117  5127.6  5145.8  5165.8  5188.6    5260  5290.8
  5317.3  5334.1  5359.2  5369.4  5392.3  5500.7    5584  5593.6  5630.1  5731.5
  875.98  874.09  865.93  862.91  862.11  856.42  852.53   848.2  845.99  842.14
  840.12  840.11  835.28  831.69  829.63  828.38  827.67  827.61  826.68  824.98
  823.52  820.27  819.26  817.85  817.24   816.3  815.27   814.7  812.99  811.33
  810.44  806.41  804.58  804.44  802.66  802.29   801.8  800.92  799.95     800
     800     800     800     800   801.2  802.48  804.45  806.21  810.67  813.37
  814.87  816.32  817.87  819.04  820.67  827.69  833.59  834.66  837.77  848.43
     764     764     764     764     764     764     764     764     764     764
     764     764     764     764     764     764     764     764     764     764
     764     764     764     764     764     764     764     764     764     764
     764     764     764     764     764     764     764     764     764     764
     798     798     764     764     764     764     764     764     764     764
     764     764     764     764     764     764     764     764     764     764
Abutment Skew #Up #Dn= , 2 , 2
    4979  4982.5
     798   789.7
    4979  4982.5
     798  790.43
Abutment Skew #Up #Dn= , 2 , 2
  5017.5    5021
  793.49     798
  5017.5    5021
  785.71     798
BR Coef= 1 , 1 , 0 ,1.25, 0 ,,,0.8,0,2,0,
WSPro=,,,, 1 ,,,, 0 ,,,, 0 ,,,,-1 ,-1 ,-1 , 0 , 0 , 0 , 0 , 0
BC Design=,, 0 ,, 0 ,,,,,,
BC HTab HWMax=880.25

Type RM Length L Ch R = 1 ,2421    ,178,178,178
BEGIN DESCRIPTION:
Tom Shelton Rd. SR-1647 - DS
END DESCRIPTION:
XS GIS Cut Line= 6
      1664145.57       988695.61      1663660.43       988700.72
      1663527.65       988772.21      1663320.83       989076.07
      1663274.86       989374.82      1663272.31       989607.17
#Sta/Elev= 30
  4173.7   867.1  4289.4  853.33  4318.4  851.29  4372.1  838.63  4479.6  830.49
  4536.4  824.54    4568  824.33    4600  818.15  4636.3  816.08  4654.9  809.99
  4663.4  808.82  4694.9  807.26  4742.7   809.3  4783.6  806.92  4854.4  796.75
  4927.8  794.08 4934.03  790.87 4946.36  788.37    4991     786  4992.5     783
  5007.5     783    5009     786 5048.54   786.5 5060.37  788.17    5071  794.32
  5110.8  796.67  5192.2  809.96  5336.6  824.31  5654.2  844.33    5713  845.34
#Mann= 4 ,-1 , 0
  4173.7     .09       0    4600    .035       0    4991    .055       0
    5009     .09       0
#XS Ineff= 2 , 0
       0    4965     800    5035       0     800
Permanent Ineff=
       F       F
Bank Sta=4991,5009
XS Rating Curve= 0
Exp/Cntr=0.5,0.3

Type RM Length L Ch R = 1 ,2243    ,438,438,438
BEGIN DESCRIPTION:
Mill Creek (hawkins mill crk) 6.0
END DESCRIPTION:
XS GIS Cut Line= 5
      1663887.41       988665.91      1663583.47       988679.12
      1663385.25       988793.65      1663288.34       988815.67
       1663072.5       988828.89
#Sta/Elev= 30
  4371.9  827.33  4381.7  827.49    4413  822.99    4502  818.84  4512.3  816.67
  4563.9   812.7  4582.7  809.49    4600     805  4608.8  803.32  4676.1  801.13
  4761.8  801.21    4789  796.99  4864.8  792.37  4953.6  791.88  4958.4  790.87
 4965.89  783.36 4976.94  780.73    4991  780.34  4993.5   779.9  5006.5   779.9
 5026.22  782.05 5032.66  786.29  5034.7  790.49  5034.7   794.7  5048.1   800.6
  5063.2  810.05  5088.6  822.84  5116.8  835.46  5155.6  850.45  5220.6  868.37
#Mann= 5 ,-1 , 0
  4371.9     .09       0    4600     .04       0    4991     .09       0
  4993.5    .055       0  5006.5     .09       0
Bank Sta=4993.5,5006.5
XS Rating Curve= 0
Exp/Cntr=0.3,0.1

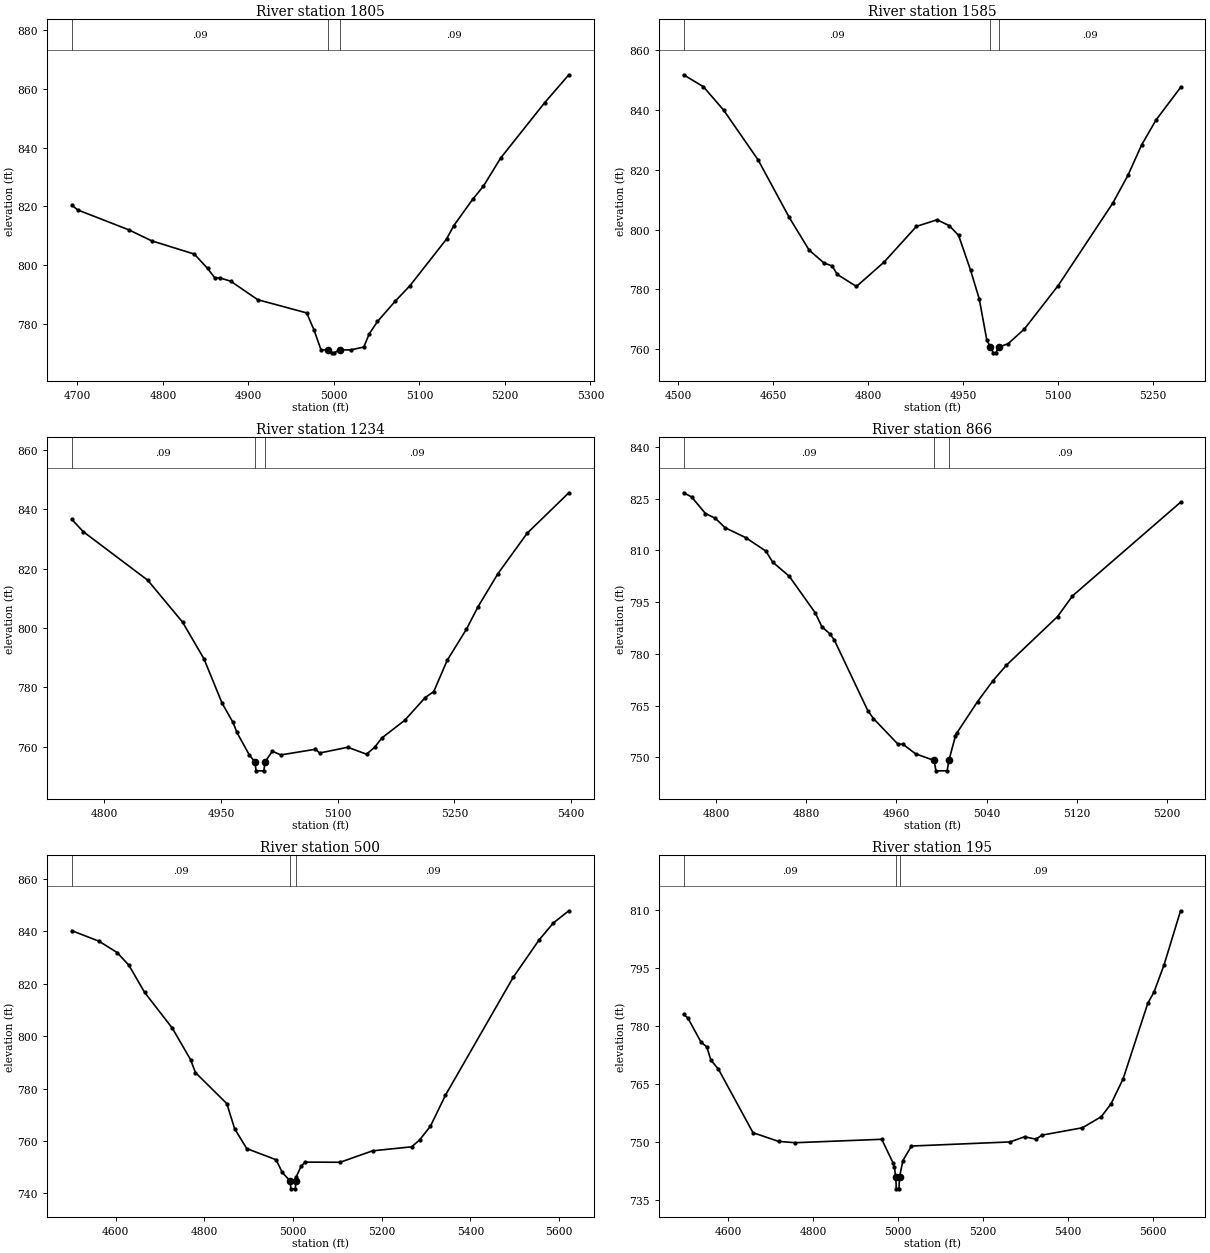
Type RM Length L Ch R = 1 ,1805    ,220,220,220
BEGIN DESCRIPTION:
Mill Creek (hawkins mill crk) 5.0
END DESCRIPTION:
XS GIS Cut Line= 5
      1663865.39       988648.29      1663715.62       988595.43
      1663627.52       988546.97       1663517.4       988507.33
      1663314.77       988476.49
#Sta/Elev= 30
  4693.4   820.4  4700.3  818.75  4760.4  811.92  4786.7  808.22  4836.7  803.69
  4852.2  798.78  4860.5  795.64  4866.8  795.55  4879.3  794.42  4910.9  788.12
  4968.1  783.62  4976.7  777.77 4984.85     771  4993.5     771 4997.52     770
  5000.2     770  5006.5     771 5019.62     771 5034.96  771.99  5041.2  776.46
  5050.9   780.7  5071.6   787.6  5088.8  792.88  5131.7  808.83    5140  813.33
  5162.2  822.37  5174.8  826.86  5194.9  836.43  5246.3  855.29  5274.7  864.86
#Mann= 3 ,-1 , 0
  4693.4     .09       0  4993.5     .05       0  5006.5     .09       0
Bank Sta=4993.5,5006.5
XS Rating Curve= 0
Exp/Cntr=0.3,0.1

Type RM Length L Ch R = 1 ,1585    ,351,351,351
BEGIN DESCRIPTION:
Mill Crk (hawkins mill crk) 4.0
END DESCRIPTION:
XS GIS Cut Line= 4
      1664241.35       988432.48      1664010.37       988428.21
      1663749.45       988393.99      1663458.59       988381.15
#Sta/Elev= 30
  4508.6  851.67    4540  847.68  4572.1  839.82  4626.4  823.24  4675.6  804.04
  4706.9  793.17  4730.4  788.85  4743.4  787.85  4751.4  785.03  4781.8     781
  4825.6  789.17  4876.6  801.06  4909.3  803.26  4928.7  801.26  4943.2  798.03
    4962  786.49  4975.8  776.83 4987.73  763.14  4993.5  760.75 4998.21  758.84
 5002.07  758.84  5006.5  760.75  5021.5   761.9  5047.1  766.79  5100.5   781.3
  5186.8  808.82  5210.7  818.08  5232.3  828.22    5255  836.54  5293.9  847.45
#Mann= 3 ,-1 , 0
  4508.6     .09       0  4993.5     .05       0  5006.5     .09       0
Bank Sta=4993.5,5006.5
XS Rating Curve= 0
Exp/Cntr=0.3,0.1

Type RM Length L Ch R = 1 ,1234    ,368,368,368
BEGIN DESCRIPTION:
Mill Crk (hawkins mill crk) 3.0
END DESCRIPTION:
XS GIS Cut Line= 4
       1664023.2       988004.75      1663954.76       988017.58
      1663787.95       988064.63      1663462.87       988291.33
#Sta/Elev= 30
    4758  836.59  4772.5  832.49  4855.7  816.06  4900.4  801.95  4927.9   789.6
  4951.3  774.61  4965.3  768.13  4970.3  764.79  4986.2  757.19  4993.5   754.8
    4995   751.8    5005   751.8  5006.5   754.8  5015.9  758.41 5026.85  757.17
 5071.38  759.08 5076.78  757.81  5112.9  759.75  5137.1  757.41  5147.7   759.8
  5156.8  762.88  5186.3  768.86  5212.5  776.49  5223.6  778.54  5240.9   789.1
  5265.4  799.47  5280.6  807.18  5306.1  818.28  5343.7  831.93  5397.3  845.56
#Mann= 3 ,-1 , 0
    4758     .09       0  4993.5     .05       0  5006.5     .09       0
#XS Ineff= 2 , 0
       0                    5100       0
Permanent Ineff=
       F       F
Bank Sta=4993.5,5006.5
XS Rating Curve= 0
Exp/Cntr=0.3,0.1

Type RM Length L Ch R = 1 ,866     ,366,366,366
BEGIN DESCRIPTION:
Mill Creek (hawkins mill crk) 2.5
END DESCRIPTION:
XS GIS Cut Line= 4
      1663675.97       987824.57      1663557.04       987921.48
      1663473.35       987983.14      1663380.85       988141.72
#Sta/Elev= 30
  4771.1   826.7  4778.2  825.51  4790.5  820.69  4799.3  819.31    4808  816.56
  4826.1  813.73  4844.2  809.79  4850.1  806.63  4864.9  802.49    4888  791.88
  4893.8  787.88  4900.9  785.83  4904.8  784.07  4934.6  763.55  4939.6  761.27
  4961.3  753.85  4965.6  753.85    4977  751.04  4993.5  749.11    4995  746.11
    5005  746.11  5006.5  749.11  5012.3  756.15  5013.4  756.98    5032   766.2
  5045.6  772.21  5057.4  776.67    5103  790.84  5116.2  796.81  5212.1  823.96
#Mann= 3 ,-1 , 0
  4771.1     .09       0  4993.5     .05       0  5006.5     .09       0
Bank Sta=4993.5,5006.5
XS Rating Curve= 0
Exp/Cntr=0.3,0.1

Type RM Length L Ch R = 1 ,500     ,305,305,305
BEGIN DESCRIPTION:
Mill Crk (hawkins mill crk) 2.0
END DESCRIPTION:
XS GIS Cut Line= 5
      1663813.61       987782.32      1663556.97       987666.84
       1663341.5       987634.98      1663111.41       987771.58
       1663101.1       988126.09
#Sta/Elev= 30
  4500.8  840.24    4562  836.24  4603.1  831.89  4629.4  827.09  4665.1  816.67
  4727.7     803  4768.7  791.01  4779.8  786.07  4850.6  774.22  4868.1  764.67
  4895.4  757.08  4961.7  752.81  4975.7  747.95  4993.5  744.71    4995  741.71
    5005  741.71  5006.5  744.71    5007  746.23    5018  750.32  5027.1  751.91
  5106.2  751.85  5179.4  756.22  5267.6  757.75  5285.7  760.41  5309.9   765.6
  5343.9  777.48  5496.5  822.39    5555   836.7  5587.3  843.19  5622.2  847.84
#Mann= 3 ,-1 , 0
  4500.8     .09       0  4993.5     .05       0  5006.5     .09       0
Bank Sta=4993.5,5006.5
XS Rating Curve= 0
Exp/Cntr=0.3,0.1

Type RM Length L Ch R = 1 ,195     ,0,0,0
BEGIN DESCRIPTION:
Mill Crk (hawkins mill crk) 1.0
END DESCRIPTION:
XS GIS Cut Line= 6
      1663611.36       987588.74      1663454.27       987408.38
      1663308.82       987335.66      1663163.37       987390.93
      1663067.38        987606.2      1663070.28       987978.54
#Sta/Elev= 30
  4494.3  783.02  4504.4  782.06  4535.9  775.76    4549  774.64  4558.7  771.21
  4576.5  768.87    4658  752.48  4718.5  750.23  4757.8   749.9  4961.5  750.78
    4988  744.74 4991.31  743.55  4994.6     741  4995.9     738  5002.1     738
  5003.4     741 5011.26  745.26  5031.5  749.04  5264.1   750.1  5298.3  751.44
  5325.1   750.8  5339.1  751.85  5434.5  753.75  5479.3  756.62  5502.4  759.99
  5530.7   766.4  5588.8  785.88  5603.2   788.7  5627.1  795.78    5666  809.72
#Mann= 3 ,-1 , 0
  4494.3     .09       0  4994.6     .05       0  5003.4     .09       0
#XS Ineff= 2 , 0
       0    4930            5100       0
Permanent Ineff=
       F       F
Bank Sta=4994.6,5003.4
XS Rating Curve= 0
Exp/Cntr=0.3,0.1

Chan Stop Cuts=-1