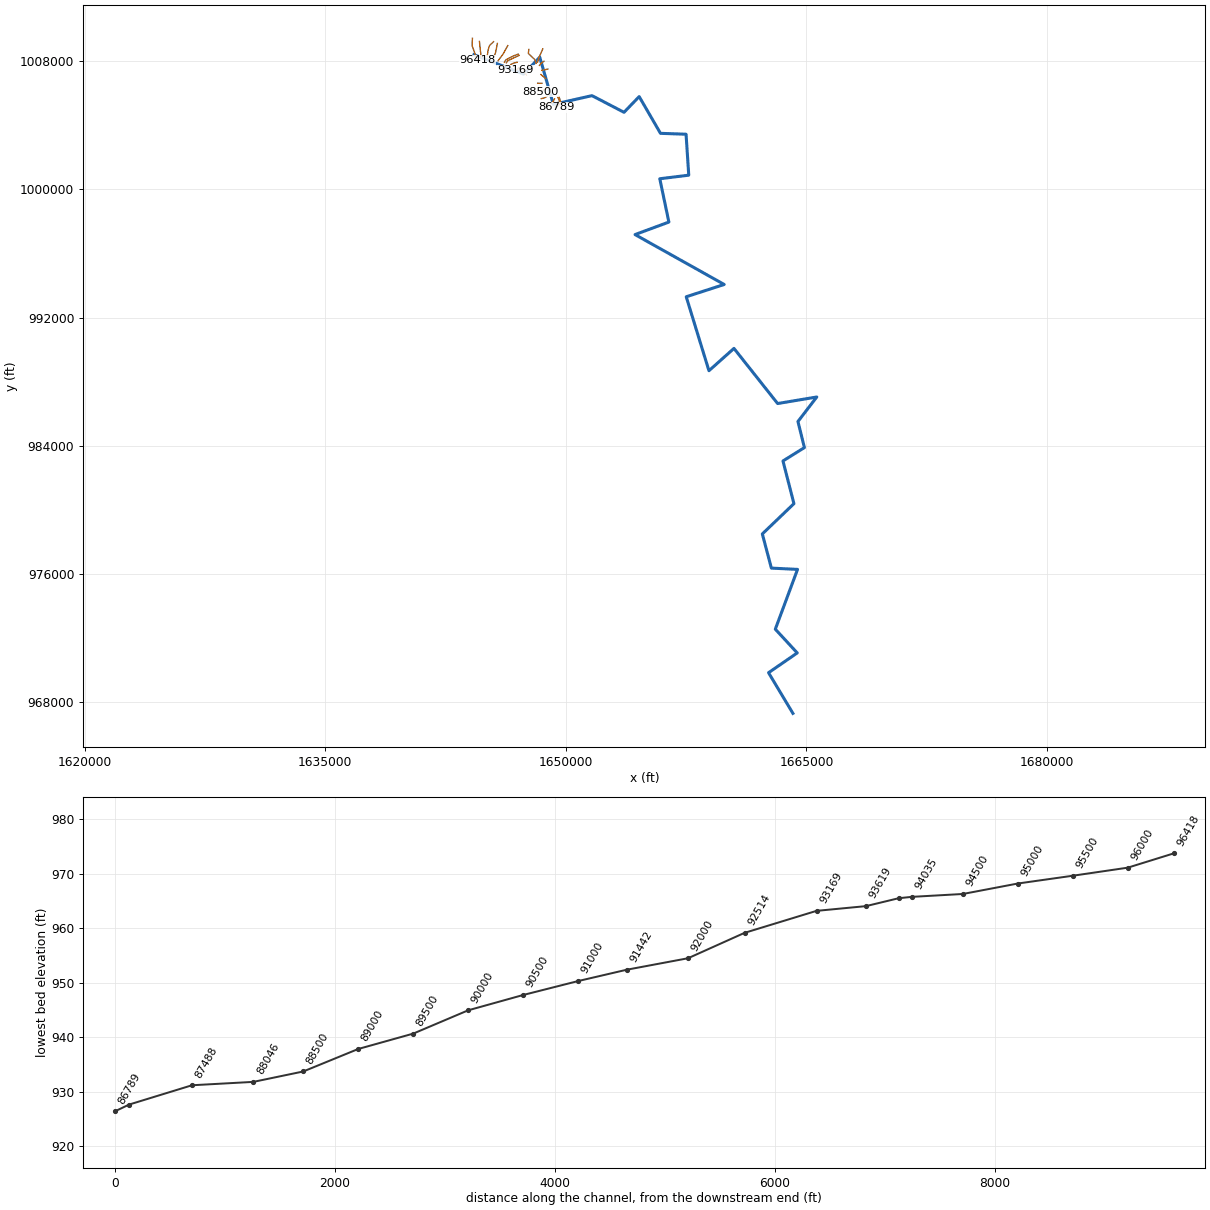
--- lds_snow_crk.prj (project) ---

Proj Title=Snow Creek Limited Detail Study
Current Plan=p02
Default Exp/Contr=0.3,0.1
English Units
Geom File=g02
Flow File=f01
Plan File=p02
Y Axis Title=Elevation
X Axis Title(PF)=Main Channel Distance
X Axis Title(XS)=Station
BEGIN DESCRIPTION:
now Creek
END DESCRIPTION:
DSS Export Rating Curves= 0
DSS Export Rating Curve Sorted= 0
DSS Export Volume Flow Curves= 0
DXF OffsetX= 0
DXF OffsetY= 0
DXF ScaleX= 1
DXF ScaleY= 10

--- lds_snow_crk.p02 (plan) ---

Plan Title=Floodway Run
Program Version=3.12
Short Identifier=Floodway
Geom File=g02
Flow File=f01
Subcritical Flow
K Sum by GR= 0
Std Step Tol= 0.01
Critical Tol= 0.01
Num of Std Step Trials= 20
Max Error Tol= 0.3
Flow Tol Ratio= 0.001
Split Flow NTrial= 30
Split Flow Tol= 0.02
Split Flow Ratio= 0.02
Log Output Level= 0
Friction Slope Method= 1
Unsteady Friction Slope Method= 2
Unsteady Bridges Friction Slope Method= 1
Parabolic Critical Depth
Global Vel Dist= 0 , 0 , 0
Global Log Level= 0
CheckData=True
Encroach Param=-1 ,5,5, 2
Encroach River=Snow Creek
Encroach Reach=Reach-1
Encroach Node=96418
       4      .7
Encroach Node=96000
       4      .7
Encroach Node=95500
       4      .7
Encroach Node=95000
       4      .7
Encroach Node=94500
       4      .7
Encroach Node=94035
       1  4945.1  5054.2
Encroach Node=93916
       1    4955    5046
Encroach Node=93619
       4      .7
Encroach Node=93169
       4      .7
Encroach Node=92514
       4      .7
Encroach Node=92000
       4      .7
Encroach Node=91442
       4      .7
Encroach Node=91000
       4      .7
Encroach Node=90500
       4      .7
Encroach Node=90000
       4      .7
Encroach Node=89500
       4      .7
Encroach Node=89000
       4      .7
Encroach Node=88500
       4      .4
Encroach Node=88046
       4      .5
Encroach Node=87488
       4      .2
Encroach Node=86915
       1    4830    5068
Encroach Node=86789
       1    4880    5061
Encroach Node=86500
       1  4852.6    5064
Encroach Node=86062
       4      .7
Encroach Node=85427
       4      .7
Encroach Node=85012
       4      .7
Encroach Node=84489
       4      .7
Encroach Node=84000
       4      .7
Encroach Node=83500
       4      .7
Encroach Node=83000
       4      .4
Encroach Node=82500
       4      .5
Encroach Node=81941
       4      .7
Encroach Node=81485
       4      .7
Encroach Node=81000
       4      .2
Encroach Node=80736
       4      .4
Encroach Node=80500
       4      .5
Encroach Node=79998
       4      .7
Encroach Node=79621
       4      .7
Encroach Node=79018
       4      .7
Encroach Node=78500
       4      .7
Encroach Node=78016
       4      .7
Encroach Node=77489
       4      .7
Encroach Node=77000
       4      .7
Encroach Node=76500
       4      .7
Encroach Node=76000
       4      .7
Encroach Node=75500
       4      .7
Encroach Node=75000
       4      .7
Encroach Node=74542
       4      .8
Encroach Node=73901
       4      .8
Encroach Node=73451
       1  4972.5  5023.5
Encroach Node=73305
       1  4981.5  5027.5
Encroach Node=73000
       4      .7
Encroach Node=72500
       4      .7
Encroach Node=72000
       4      .7
Encroach Node=71518
       4      .7
Encroach Node=71109
       4      .7
Encroach Node=70500
       4      .7
Encroach Node=70000
       4      .7
Encroach Node=69500
       4      .7
Encroach Node=69025
       4      .7
Encroach Node=68500
       4      .7
Encroach Node=68000
       4      .7
Encroach Node=67500
       4      .4
Encroach Node=67000
       4      .4
Encroach Node=66517
       4      .7
Encroach Node=65972
       4      .7
Encroach Node=65183
       4      .7
Encroach Node=64794
       4      .7
Encroach Node=64558
       4      .7
Encroach Node=64059
       4      .7
Encroach Node=63500
       4      .7
Encroach Node=63000
       4      .7
Encroach Node=62500
       4      .7
Encroach Node=61985
       1  4918.4  5077.1
Encroach Node=61775
       1  4914.1  5078.4
Encroach Node=61286
       4      .7
Encroach Node=60802
       4      .7
Encroach Node=60500
       4      .7
Encroach Node=60000
       4      .7
Encroach Node=59481
       4      .7
Encroach Node=59009
       4      .7
Encroach Node=58496
       4      .7
Encroach Node=58000
       4      .7
Encroach Node=57488
       4      .7
Encroach Node=57000
       4      .7
Encroach Node=56507
       4      .7
Encroach Node=56000
       4      .7
Encroach Node=55721
       4      .7
Encroach Node=55500
       4      .2
Encroach Node=55000
       1 4683.31 5022.48
Encroach Node=54438
       1 4836.14  5020.6
Encroach Node=54000
       4      .7
Encroach Node=53500
       4      .7
Encroach Node=53000
       4      .7
Encroach Node=52500
       4      .7
Encroach Node=52005
       4      .7
Encroach Node=51500
       1 4945.59    5019
Encroach Node=51037
       1 4965.14 5022.11
Encroach Node=50500
       4      .7
Encroach Node=50000
       4      .7
Encroach Node=49500
       4      .7
Encroach Node=49000
       4      .7
Encroach Node=48587
       4      .7
Encroach Node=48000
       4      .7
Encroach Node=47415
       4      .7
Encroach Node=46577
       4      .7
Encroach Node=46058
       4      .7
Encroach Node=45384
       4      .7
Encroach Node=45000
       4      .7
Encroach Node=44442
       4      .7
Encroach Node=43843
       4      .7
Encroach Node=43342
       4      .7
Encroach Node=42464
       4      .7
Encroach Node=42000
       4      .7
Encroach Node=41500
       4      .7
Encroach Node=41000
       4      .7
Encroach Node=40500
       4      .7
Encroach Node=40000
       4      .7
Encroach Node=39500
       4      .7
Encroach Node=39000
       4      .7
Encroach Node=38594
       4      .2
Encroach Node=38084
       1    4899    5101
Encroach Node=37990
       1  4902.5    5100
Encroach Node=37506
       1  4973.2    5186
Encroach Node=37000
       1    4883    5129
Encroach Node=36500
       1    4937    5150
Encroach Node=36000
       1    4900    5100
Encroach Node=34590
       4      .9
Encroach Node=34000
       4      .7
Encroach Node=33168
       4      .7
Encroach Node=32500
       4      .7
Encroach Node=31938
       4      .7
Encroach Node=31500
       4      .7
Encroach Node=31000
       4      .7
Encroach Node=30500
       4      .7
Encroach Node=30000
       4      .7
Encroach Node=29369
       4      .7
Encroach Node=29000
       4      .7
Encroach Node=28520
       4      .7
Encroach Node=27927
       4      .7
Encroach Node=27500
       4      .7
Encroach Node=26875
       4      .7
Encroach Node=26594
       4      .7
Encroach Node=26053
       4      .7
Encroach Node=25500
       4      .7
Encroach Node=25321
       4      .7
Encroach Node=25276
       4      .7
Encroach Node=25000
       4      .7
Encroach Node=24320
       1  4913.5  5058.6
Encroach Node=24216
       1 4913.25  5062.7
Encroach Node=23539
       4      .7
Encroach Node=23000
       4      .7
Encroach Node=22500
       4      .7
Encroach Node=22000
       4      .7
Encroach Node=21559
       4      .7
Encroach Node=21000
       4      .7
Encroach Node=20500
       4      .7
Encroach Node=20100
       1    4908 5044.43
Encroach Node=19939
       1    4902  5094.1
Encroach Node=19500
       4      .7
Encroach Node=18946
       4      .7
Encroach Node=18536
       4      .7
Encroach Node=18000
       4      .7
Encroach Node=17500
       4      .7
Encroach Node=16500
       4      .7
Encroach Node=16000
       4      .7
Encroach Node=15350
       4      .7
Encroach Node=14936
       4      .7
Encroach Node=14423
       4      .7
Encroach Node=14000
       4      .7
Encroach Node=13500
       4      .7
Encroach Node=12966
       4      .7
Encroach Node=12542
       4      .7
Encroach Node=12000
       4      .7
Encroach Node=11548
       4      .7
Encroach Node=11000
       4      .7
Encroach Node=10500
       4      .7
Encroach Node=10000
       4      .7
Encroach Node=9456
       4      .7
Encroach Node=9000
       4      .7
Encroach Node=8500
       4      .7
Encroach Node=8000
       4      .7
Encroach Node=7500
       4      .7
Encroach Node=7000
       4      .7
Encroach Node=6500
       4      .7
Encroach Node=5974
       4      .7
Encroach Node=5500
       4      .7
Encroach Node=5008
       4      .7
Encroach Node=4431
       4      .7
Encroach Node=4000
       4      .7
Encroach Node=3534
       4      .7
Encroach Node=3000
       4      .5
Encroach Node=2500
       4      .7
Encroach Node=2000
       1    4962    5048
Encroach Node=1500
       1    4944    5051
Encroach Node=1091
       4      .8
Encroach Node=441
       1  4946.6    5054
Encroach Node=326
       1    4950    5049
Encroach Node=21
       4      .8
BEGIN DESCRIPTION:
Floodway Run
END DESCRIPTION:
Computation Interval=1HOUR
Output Interval=1HOUR
Run HTab= 0
Run UNet= 0
Run PostProcess= 0
UNET Theta= 1
UNET Theta Warmup= 1
UNET ZTol= 0.02
UNET ZSATol= 0.05
UNET MxIter= 20
UNET MaxInSteps= 0
UNET DtIC= 0
UNET DtMin= 0
UNET MaxCRTS= 20
UNET WFStab= 2
UNET SFStab= 1
UNET WFX= 1
UNET SFX= 1
UNET DSS MLevel= 4
UNET DZMax Abort= 100
UNET Convert EG Bridges=-1
UNET Use Existing IB Tables=-1
UNET Froude Reduction=False
UNET Froude Limit= 1
UNET Froude Power= 10
Instantaneous Interval=1HOUR
Write IC File= 0
Echo Input=False
Echo Output=False
Write Detailed= 0
Detailed Automatic Start=False, 10

--- lds_snow_crk.f01 (steady flow) ---

Flow Title=Floodway
Program Version=3.12
Number of Profiles= 2
Profile Names=100-year,100-FW
River Rch & RM=Snow Creek,Reach-1         ,96418
    1388    1388
River Rch & RM=Snow Creek,Reach-1         ,95500
    1806    1806
River Rch & RM=Snow Creek,Reach-1         ,94035
    1922    1922
River Rch & RM=Snow Creek,Reach-1         ,90500
    2073    2073
River Rch & RM=Snow Creek,Reach-1         ,86915
    2587    2587
River Rch & RM=Snow Creek,Reach-1         ,83000
    2632    2632
River Rch & RM=Snow Creek,Reach-1         ,80500
    2939    2939
River Rch & RM=Snow Creek,Reach-1         ,77000
    2991    2991
River Rch & RM=Snow Creek,Reach-1         ,74542
    3280    3280
River Rch & RM=Snow Creek,Reach-1         ,68500
    3306    3306
River Rch & RM=Snow Creek,Reach-1         ,67000
    3650    3650
River Rch & RM=Snow Creek,Reach-1         ,64059
    3736    3736
River Rch & RM=Snow Creek,Reach-1         ,62500
    3746    3746
River Rch & RM=Snow Creek,Reach-1         ,61286
    4078    4078
River Rch & RM=Snow Creek,Reach-1         ,57488
    4161    4161
River Rch & RM=Snow Creek,Reach-1         ,52500
    4219    4219
River Rch & RM=Snow Creek,Reach-1         ,45384
    5121    5121
River Rch & RM=Snow Creek,Reach-1         ,44442
    5269    5269
River Rch & RM=Snow Creek,Reach-1         ,37506
    5591    5591
River Rch & RM=Snow Creek,Reach-1         ,34590
    6385    6385
River Rch & RM=Snow Creek,Reach-1         ,29000
    6448    6448
River Rch & RM=Snow Creek,Reach-1         ,26053
    6468    6468
River Rch & RM=Snow Creek,Reach-1         ,23539
    6882    6882
River Rch & RM=Snow Creek,Reach-1         ,19500
    6924    6924
River Rch & RM=Snow Creek,Reach-1         ,18946
    7150    7150
River Rch & RM=Snow Creek,Reach-1         ,12966
    7209    7209
River Rch & RM=Snow Creek,Reach-1         ,12000
    7229    7229
River Rch & RM=Snow Creek,Reach-1         ,9000
    7645    7645
River Rch & RM=Snow Creek,Reach-1         ,4431
    7668    7668
River Rch & RM=Snow Creek,Reach-1         ,1091
    7910    7910
Boundary for River Rch & Prof#=Snow Creek,Reach-1         , 1
Up Type= 0
Dn Type= 3
Dn Slope=0.002
Boundary for River Rch & Prof#=Snow Creek,Reach-1         , 2
Up Type= 0
Dn Type= 3
Dn Slope=0.002
DSS Import GetInterval= 0
DSS Import GetPeak= 0
DSS Import FillOption= 0

--- lds_snow_crk.g02 (geometry) ---

Geom Title=Existing Conditions
Program Version=3.12

River Reach=Snow Creek      ,Reach-1
Reach XY= 30
      1644273.25      1008406.06        1647370.      1007193.75
      1648374.88      1008247.38      1649224.52      1005304.19
      1651632.25        1005850.      1653629.25       1004809.5
      1654574.75      1005790.38       1655903.5      1003497.31
       1657498.5      1003442.06      1657666.38      1000886.19
      1655860.38      1000663.06        1656427.       997959.81
      1654315.13       997179.88       1659876.5       994065.69
      1657509.38       993298.94      1658925.25       988683.44
        1660486.       990076.44      1663208.75       986635.81
       1665649.5       987044.94      1664474.88       985513.88
      1664879.38       983886.75      1663541.25       983052.88
       1664225.5       980388.69      1662254.13       978498.75
      1662819.13       976366.44      1664450.25       976286.69
        1663064.       972555.19        1664432.       971074.44
       1662642.5       969839.69        1664162.       967301.88

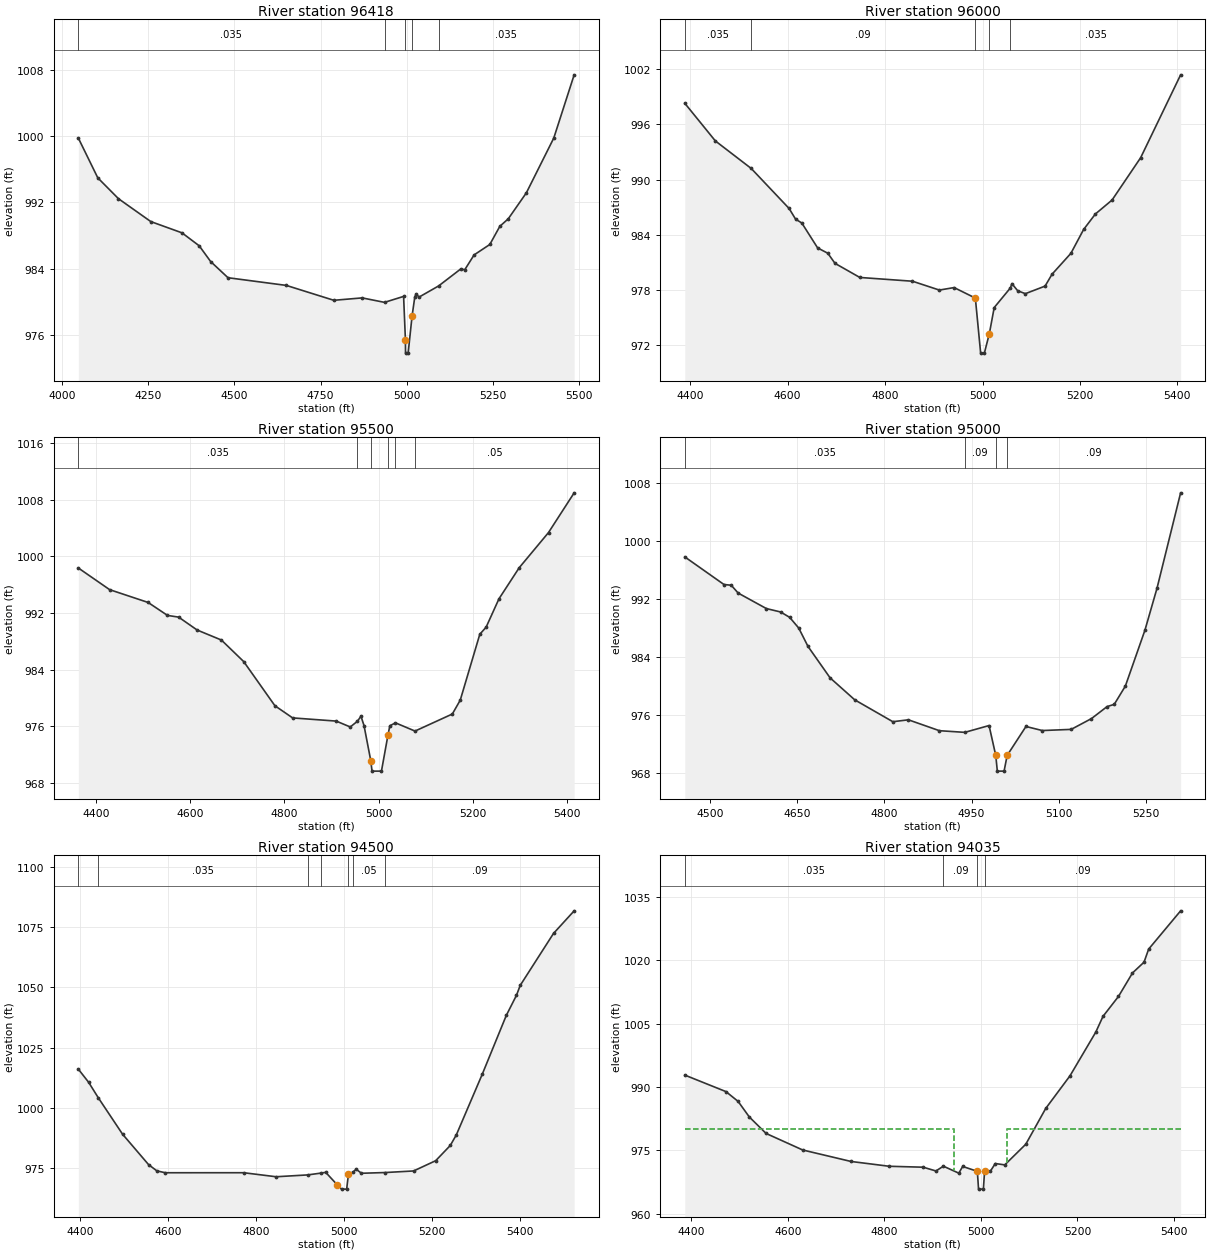
Type RM Length L Ch R = 1 ,96418   ,418,418,418
BEGIN DESCRIPTION:
Snow Creek 194.0
END DESCRIPTION:
XS GIS Cut Line= 4
      1644176.27      1009425.42      1644153.44      1008968.92
      1644323.83      1008508.82       1644478.7      1008044.51
#Sta/Elev= 30
  4047.8  999.78  4104.2  994.97  4164.1  992.45  4257.9  989.68  4348.2  988.32
  4398.2  986.75  4431.3  984.85  4481.6  982.89  4650.7  981.96  4788.4  980.16
  4870.6  980.45  4935.3  979.91 4990.64  980.63 4995.97   975.3  4996.2  973.77
  5003.8  973.77  5015.2  978.26  5023.1  980.57  5027.3  980.95  5035.1  980.54
  5091.9  981.89  5156.6  983.96  5167.8  983.85    5195  985.65  5240.5  986.91
  5269.6  989.11  5293.9  990.01  5346.5  993.16    5426  999.79    5485 1007.43
#Mann= 5 ,-1 , 0
  4047.8    .035       0  4935.3     .09       0 4995.97     .05       0
  5015.2     .08       0  5091.9    .035       0
Bank Sta=4995.97,5015.2
Exp/Cntr=0.3,0.1

Type RM Length L Ch R = 1 ,96000   ,500,500,500
BEGIN DESCRIPTION:
Snow Creek 193.0
END DESCRIPTION:
XS GIS Cut Line= 3
      1644612.95      1009234.87      1644675.94      1008627.09
      1644733.94       1008224.6
#Sta/Elev= 30
    4389  998.29  4451.7   994.2  4525.3  991.21  4603.1  986.86  4616.3  985.71
  4629.2  985.28  4661.6  982.58  4682.5     982  4697.3   980.9  4748.2  979.37
  4856.3  978.96  4911.4     978  4941.7  978.27  4985.3  977.13  4996.2  971.15
  5003.8  971.15  5014.1  973.28    5024   976.1  5057.2  978.23  5060.3   978.7
  5072.3  977.92    5088  977.61  5128.4  978.43  5142.7  979.72  5181.4  981.99
  5207.5  984.58  5231.6  986.26  5265.9  987.78  5324.6  992.38  5406.6 1001.38
#Mann= 5 ,-1 , 0
    4389    .035       0  4525.3     .09       0  4985.3     .05       0
  5014.1     .09       0  5057.2    .035       0
Bank Sta=4985.3,5014.1
Exp/Cntr=0.3,0.1

Type RM Length L Ch R = 1 ,95500   ,500,500,500
BEGIN DESCRIPTION:
Snow Creek 192.0
END DESCRIPTION:
XS GIS Cut Line= 4
      1645496.17      1009216.72      1645241.69      1008974.86
      1645156.16      1008701.56      1645096.91      1008291.15
#Sta/Elev= 30
  4362.6  998.37    4429  995.31  4510.7   993.5  4551.8  991.67  4575.4  991.43
  4614.6  989.61  4666.2  988.19  4713.6  985.14  4779.7  978.91  4817.3  977.19
  4909.8  976.74  4939.6  975.91  4954.9  976.72  4962.3  977.43  4968.8  976.11
  4983.1  971.16  4985.8  969.67  5005.8  969.67  5019.7  974.79  5023.6  976.08
  5035.6  976.49    5077  975.33  5156.2  977.74    5173   979.7  5214.5  989.01
  5227.9  990.01  5255.1  994.01    5298   998.4  5360.3 1003.38  5414.7 1008.99
#Mann= 6 ,-1 , 0
  4362.6    .035       0  4954.9     .09       0  4983.1     .05       0
  5019.7     .09       0  5035.6    .035       0    5077     .05       0
Bank Sta=4983.1,5019.7
Exp/Cntr=0.3,0.1

Type RM Length L Ch R = 1 ,95000   ,500,500,500
BEGIN DESCRIPTION:
Snow Creek 191.0
END DESCRIPTION:
XS GIS Cut Line= 3
       1645732.1      1009107.83      1645627.74      1008575.07
      1645538.52      1008279.05
#Sta/Elev= 30
  4457.1   997.8  4524.4  993.99  4536.9  993.89  4548.8  992.81  4597.3  990.67
  4621.7   990.2  4637.3  989.46  4652.9  987.98  4668.8  985.45  4706.8  981.11
  4749.1  978.08  4814.6  975.06  4841.4  975.32  4894.6  973.82  4938.3  973.59
    4980  974.53  4991.5   970.4  4994.2  968.24  5005.8  968.24  5011.1  970.41
  5043.4   974.4  5071.5  973.84  5121.1     974    5156  975.49  5182.9  977.15
  5195.1  977.45  5214.2  979.97  5247.8  987.67  5268.6  993.47  5309.2 1006.64
#Mann= 4 ,-1 , 0
  4457.1    .035       0  4938.3     .09       0  4991.5     .05       0
  5011.1     .09       0
Bank Sta=4991.5,5011.1
Exp/Cntr=0.3,0.1

Type RM Length L Ch R = 1 ,94500   ,465,465,465
BEGIN DESCRIPTION:
Snow Creek 190.0
END DESCRIPTION:
XS GIS Cut Line= 3
       1646379.4      1008974.74      1646088.86      1008444.13
        1645775.        1008025.
#Sta/Elev= 30
  4395.1 1016.05  4418.5 1010.61  4440.5 1004.19  4495.8  989.08  4554.9  976.49
  4573.8  973.89    4593  973.11  4771.4  973.12  4845.2  971.45  4917.1  972.21
  4948.4  972.99  4958.1  973.28  4984.3  968.12  4994.2  966.32  5005.8  966.32
  5009.8  972.43  5020.6  973.46  5027.6  974.56  5039.5  972.89  5093.9   973.2
  5158.2  973.85  5208.5  978.11  5241.7  984.42  5255.5  988.83  5314.6 1014.01
  5369.2 1038.33  5392.3 1046.65  5400.9 1050.78  5476.6 1072.29  5523.6 1081.66
#Mann= 7 ,-1 , 0
  4395.1     .09       0  4440.5    .035       0  4917.1     .09       0
  4948.4     .05       0  5009.8     .09       0  5020.6     .05       0
  5093.9     .09       0
Bank Sta=4984.3,5009.8
Exp/Cntr=0.5,0.3

Type RM Length L Ch R = 1 ,94035   ,119,119,119
BEGIN DESCRIPTION:
Moore Rd. SR-1602 - US
END DESCRIPTION:
XS GIS Cut Line= 4
      1647035.48      1008443.49      1646722.77      1008323.22
      1646275.36       1008094.7      1646167.11      1007938.34
#Sta/Elev= 30
  4386.2  992.79  4471.5  988.88  4496.7  986.56    4520  982.86  4554.7  978.97
  4630.5  975.06  4730.7  972.34  4809.9   971.2  4880.3  970.98  4906.7  970.09
  4922.1  971.22  4954.1  969.57  4962.1  971.16  4992.5     970    4995  965.79
    5005  965.79  5007.5     970  5019.1  969.97  5029.7  971.85  5049.3  971.53
  5092.9  976.42  5134.2  984.89  5184.6  992.63    5238 1002.97  5252.9 1006.69
    5285 1011.41    5314 1016.96    5338 1019.53  5347.5 1022.61  5413.8 1031.68
#Mann= 4 ,-1 , 0
  4386.2    .035       0  4922.1     .09       0  4992.5     .05       0
  5007.5     .09       0
#XS Ineff= 2 , 0
       0  4945.1     980  5054.2       0  980.01
Permanent Ineff=
       F       F
Bank Sta=4992.5,5007.5
Exp/Cntr=0.5,0.3

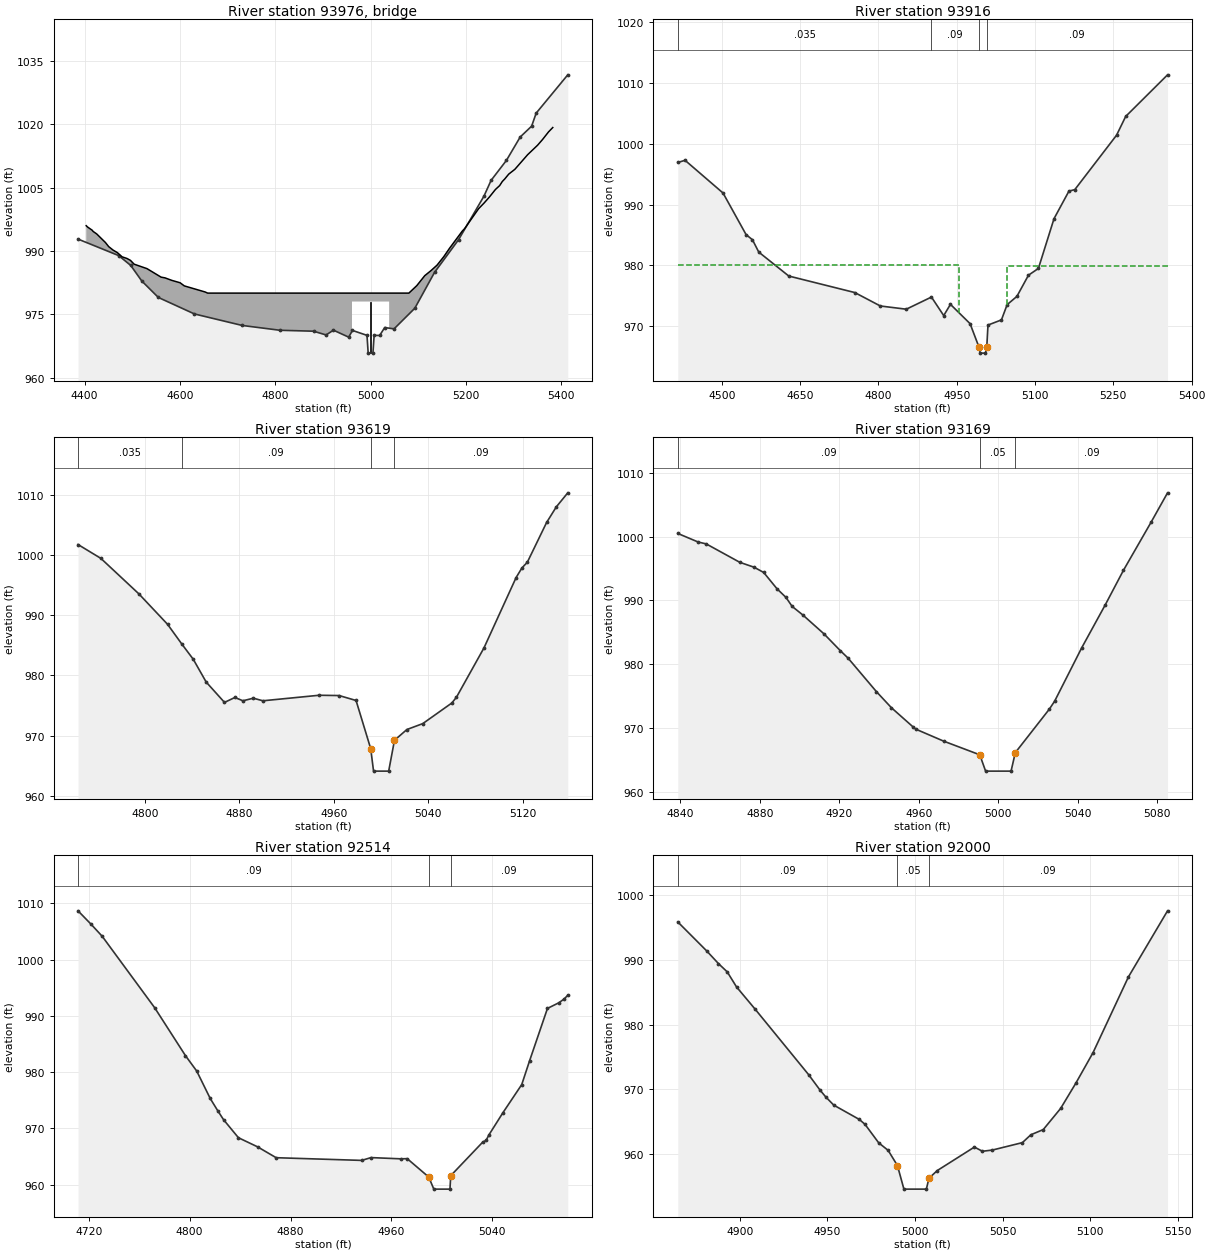
Type RM Length L Ch R = 3 ,93976   ,,,
BEGIN DESCRIPTION:
Moore Rd. SR-1602
Structure ID: Moore Rd. SR-1602
Approximate Survey Structure
END DESCRIPTION:
Bridge Culvert--1,0,-1,-1, 0
Deck Dist Width WeirC Skew NumUp NumDn MinLoCord MaxHiCord MaxSubmerge Is_Ogee
43,32,3,0, 48, 48, , , , 0, 1,1,,
  4403.4  4406.2    4416  4417.9  4425.3  4443.7  4450.5  4459.9  4468.6  4478.6
  4488.9  4496.2  4503.9  4530.8  4560.5  4568.7  4582.9  4600.4  4609.2  4653.1
  4658.1    4961    4961    5039    5039  5080.4    5097  5113.7  5126.6  5139.5
  5153.6  5165.3  5192.5  5197.3  5226.8  5238.3  5249.5    5262  5270.9  5276.4
  5281.6  5289.9  5302.8  5329.6  5350.5  5360.9  5373.3  5382.3
  995.96  995.65  994.88   994.6  994.02  991.98  991.01  990.17   989.6  988.59
   988.2  987.75  986.85   985.8  983.78  983.61  983.02  982.45  981.71  980.26
     980     980     980     980     980     980  981.77  984.13  985.31  986.62
  988.62  990.55  994.69  995.26    1000 1001.34 1002.77 1004.53 1005.46 1006.42
 1007.03 1008.17 1009.31 1012.77 1015.02 1016.37 1018.15  1019.2
  945.79  945.79  945.79  945.79  945.79  945.79  945.79  945.79  945.79  945.79
  945.79  945.79  945.79  945.79  945.79  945.79  945.79  945.79  945.79  945.79
  945.79  945.79     978     978  945.79  945.79  945.79  945.79  945.79  945.79
  945.79  945.79  945.79  945.79  945.79  945.79  945.79  945.79  945.79  945.79
  945.79  945.79  945.79  945.79  945.79  945.79  945.79  945.79
  4403.4  4406.2    4416  4417.9  4425.3  4443.7  4450.5  4459.9  4468.6  4478.6
  4488.9  4496.2  4503.9  4530.8  4560.5  4568.7  4582.9  4600.4  4609.2  4653.1
  4658.1    4961    4961    5039    5039  5080.4    5097  5113.7  5126.6  5139.5
  5153.6  5165.3  5192.5  5197.3  5226.8  5238.3  5249.5    5262  5270.9  5276.4
  5281.6  5289.9  5302.8  5329.6  5350.5  5360.9  5373.3  5382.3
  995.96  995.65  994.88   994.6  994.02  991.98  991.01  990.17   989.6  988.59
   988.2  987.75  986.85   985.8  983.78  983.61  983.02  982.45  981.71  980.26
     980     980     980     980     980     980  981.77  984.13  985.31  986.62
  988.62  990.55  994.69  995.26    1000 1001.34 1002.77 1004.53 1005.46 1006.42
 1007.03 1008.17 1009.31 1012.77 1015.02 1016.37 1018.15  1019.2
  945.79  945.79  945.79  945.79  945.79  945.79  945.79  945.79  945.79  945.79
  945.79  945.79  945.79  945.79  945.79  945.79  945.79  945.79  945.79  945.79
  945.79  945.79     978     978  945.79  945.79  945.79  945.79  945.79  945.79
  945.79  945.79  945.79  945.79  945.79  945.79  945.79  945.79  945.79  945.79
  945.79  945.79  945.79  945.79  945.79  945.79  945.79  945.79
Pier Skew, UpSta & Num, DnSta & Num=  ,5000, 2 ,5000, 2 , 0 , 0 , 0 ,0,0
       2       2
     969     978
       2       2
   965.5     978
Abutment Skew #Up #Dn= , 2 , 2
    4961  4962.5
     978  971.12
    4961  4962.5
     978  975.92
Abutment Skew #Up #Dn= , 2 , 2
  5037.5    5039
  971.66     978
  5037.5    5039
  971.45     978
BR Coef= 1 , 1 , 0 ,1.25, 0 ,,,0.8,0,2,0,
WSPro=,,,, 1 ,,,, 0 ,,,, 0 ,,,,-1 ,-1 ,-1 , 0 , 0 , 0 , 0 , 0
BC Design=,, 0 ,, 0 ,,,,,,
BC HTab HWMax=1031.68

Type RM Length L Ch R = 1 ,93916   ,297,297,297
BEGIN DESCRIPTION:
Moore Rd. SR-1602 - DS
END DESCRIPTION:
XS GIS Cut Line= 3
       1647088.4       1008361.7      1646373.98      1008024.94
      1646289.79      1007899.86
#Sta/Elev= 30
  4415.6  996.92  4429.5  997.28  4502.3  991.89  4546.4  985.05  4558.6   984.2
  4570.7  982.17  4628.2  978.23  4754.7  975.51  4803.6   973.3  4853.3  972.77
  4901.5  974.77    4925  971.72  4937.9  973.57  4975.5  970.39  4992.5  966.54
    4995  965.54    5005  965.54  5007.5  966.54  5009.8  970.16  5035.6  971.01
  5046.5  973.52  5065.2  974.88  5087.4  978.37  5106.4  979.48  5136.3  987.67
  5164.9  992.21  5176.1  992.45  5256.1 1001.41  5273.6  1004.5  5353.8 1011.35
#Mann= 4 ,-1 , 0
  4415.6    .035       0  4901.5     .09       0  4992.5     .05       0
  5007.5     .09       0
#XS Ineff= 2 , 0
       0    4955     980    5046       0  979.94
Permanent Ineff=
       F       F
Bank Sta=4992.5,5007.5
Exp/Cntr=0.5,0.3

Type RM Length L Ch R = 1 ,93619   ,450,450,450
BEGIN DESCRIPTION:
Snow Creek 188.0
END DESCRIPTION:
XS GIS Cut Line= 3
      1646963.32      1007935.94      1646705.93      1007861.37
      1646573.63      1007798.83
#Sta/Elev= 30
  4743.6 1001.78  4762.9  999.48  4795.1  993.57  4819.3  988.52  4831.4  985.23
  4841.1  982.69    4852  978.91  4867.5  975.52  4876.3  976.34  4883.1  975.79
  4891.9  976.22    4900  975.79  4947.6  976.71  4964.5  976.66  4978.8  975.84
  4991.2  967.82  4993.6  964.09  5006.4  964.09  5011.3  969.22  5021.8  971.01
  5035.2  971.99  5059.8  975.42  5063.7  976.37    5087  984.58  5114.2  996.29
  5119.1  997.88  5123.7  998.84    5140 1005.45  5148.2 1008.04  5157.9 1010.38
#Mann= 4 ,-1 , 0
  4743.6    .035       0  4831.4     .09       0  4991.2     .05       0
  5011.3     .09       0
Bank Sta=4991.2,5011.3
Exp/Cntr=0.3,0.1

Type RM Length L Ch R = 1 ,93169   ,655,655,655
BEGIN DESCRIPTION:
Snow Creek 187.0
END DESCRIPTION:
XS GIS Cut Line= 3
      1647083.59      1007582.33       1646953.7      1007486.12
      1646883.94      1007438.01
#Sta/Elev= 29
  4838.8 1000.49    4849  999.15  4853.1  998.85    4870  995.96  4877.2  995.19
    4882  994.37  4888.7  991.81  4893.2  990.46  4896.3  989.05  4901.7   987.7
  4912.3  984.75  4920.5  982.12  4924.4  980.95  4938.7  975.68  4946.2  973.17
  4957.3   970.1  4958.5   969.8  4972.6  967.91 4990.67  965.78  4993.6  963.22
  5006.4  963.22 5008.54  966.12  5025.6  972.92  5028.3  974.18  5041.9  982.54
  5053.8  989.31  5062.9   994.7  5076.8 1002.24  5085.1 1006.86
#Mann= 3 ,-1 , 0
  4838.8     .09       0 4990.67     .05       0 5008.54     .09       0
Bank Sta=4990.67,5008.54
Exp/Cntr=0.3,0.1

Type RM Length L Ch R = 1 ,92514   ,514,514,514
BEGIN DESCRIPTION:
Snow Creek 186.0
END DESCRIPTION:
XS GIS Cut Line= 3
      1647360.22      1007483.71      1647481.39      1007226.57
      1647545.44      1007144.54
#Sta/Elev= 30
  4711.5 1008.69  4721.9 1006.29  4730.7 1004.15  4772.3  991.44  4796.7  982.92
  4805.6  980.19  4816.3  975.31  4822.3  973.12  4826.9  971.53  4838.7  968.32
  4853.8  966.71  4868.6  964.77  4936.4  964.29  4943.8  964.79  4967.4  964.57
  4972.5   964.6 4989.57  961.33  4993.6  959.18  5006.4  959.18    5007  961.57
  5032.4  967.55    5035  967.84  5037.4  968.87  5048.4  972.78  5063.3  977.78
  5069.5     982  5083.7  991.33  5092.7  992.33  5096.9     993  5099.8  993.67
#Mann= 3 ,-1 , 0
  4711.5     .09       0 4989.57     .05       0    5007     .09       0
Bank Sta=4989.57,5007
Exp/Cntr=0.3,0.1

Type RM Length L Ch R = 1 ,92000   ,558,558,558
BEGIN DESCRIPTION:
Snow Creek 185.0
END DESCRIPTION:
XS GIS Cut Line= 3
      1647665.71      1007721.85      1647771.91      1007637.93
      1647891.83      1007558.28
#Sta/Elev= 30
  4864.6  995.88  4881.1  991.39  4887.8  989.43  4892.8  988.15  4898.1  985.82
  4908.8  982.35  4939.2  972.25  4945.8  969.83  4949.1  968.76  4953.6  967.52
  4968.2   965.3  4971.4  964.55  4979.2  961.69  4984.6  960.52  4989.9  958.17
  4993.6  954.52  5006.4  954.52 5007.89  956.21 5012.66   957.4  5033.8  961.03
  5038.4  960.38  5044.1  960.57  5061.2  961.72    5066  962.93  5073.1  963.74
    5083  967.01  5091.7  970.93  5101.5  975.65  5121.7  987.38    5144   997.6
#Mann= 3 ,-1 , 0
  4864.6     .09       0  4989.9     .05       0 5007.89     .09       0
Bank Sta=4989.9,5007.89
Exp/Cntr=0.3,0.1

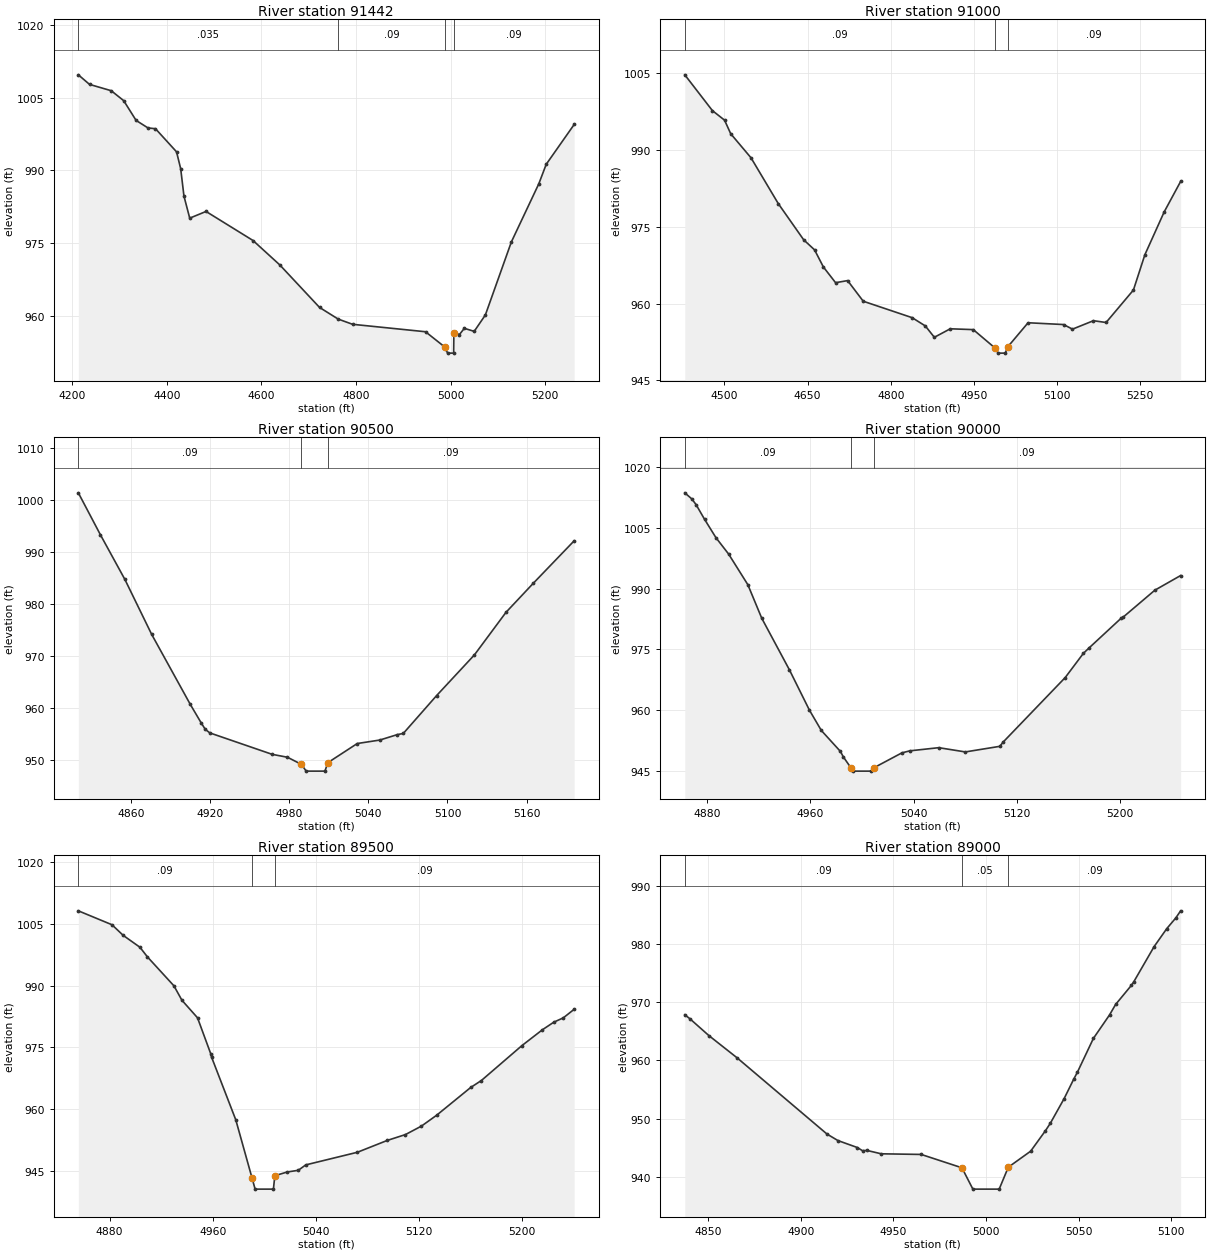
Type RM Length L Ch R = 1 ,91442   ,442,442,442
BEGIN DESCRIPTION:
Snow Creek 184.0
END DESCRIPTION:
XS GIS Cut Line= 5
      1647692.17      1008729.74      1647665.71      1008479.57
      1647939.94      1008217.38      1648060.21      1008106.72
      1648149.21      1007868.58
#Sta/Elev= 30
  4212.6 1009.67  4236.3  1007.7  4282.2  1006.4  4308.6 1004.35  4334.8 1000.29
    4360  998.74  4375.8  998.58  4420.3  993.83  4429.1  990.35    4436  984.72
  4448.2  980.18  4482.7  981.56  4582.1  975.58  4638.8  970.55  4722.8  961.81
  4762.3  959.41  4792.7  958.34  4946.9  956.81    4988  953.64  4993.6  952.41
  5006.4  952.41  5006.9   956.6  5018.7  956.24    5029  957.51  5049.9  956.89
  5073.5  960.26  5128.5  975.29  5186.5  987.24  5202.2  991.26  5261.3  999.45
#Mann= 4 ,-1 , 0
  4212.6    .035       0  4762.3     .09       0    4988     .05       0
  5006.9     .09       0
Bank Sta=4988,5006.9
Exp/Cntr=0.3,0.1

Type RM Length L Ch R = 1 ,91000   ,500,500,500
BEGIN DESCRIPTION:
Snow Creek 183.0
END DESCRIPTION:
XS GIS Cut Line= 3
      1648566.26      1008766.72      1648331.12      1008245.83
      1648238.51      1007936.84
#Sta/Elev= 30
  4428.5 1004.66  4478.3  997.67  4500.2  995.81  4511.3  993.16  4547.9  988.46
    4597  979.53  4642.9  972.45  4662.5  970.49  4678.4  967.15  4700.4  964.08
  4722.1  964.49  4750.3  960.46  4838.5  957.25  4862.2  955.64  4878.5  953.42
  4907.2  955.08  4948.7  954.92 4987.88  951.33  4993.6  950.33  5006.4  950.33
 5010.73  951.53  5047.5  956.26  5111.5  955.91  5127.6  955.01  5165.4  956.66
  5188.2  956.31  5237.5  962.65  5258.1  969.53    5293  977.91  5322.6  983.84
#Mann= 3 ,-1 , 0
  4428.5     .09       0 4987.88     .05       0 5010.73     .09       0
Bank Sta=4987.88,5010.73
Exp/Cntr=0.3,0.1

Type RM Length L Ch R = 1 ,90500   ,500,500,500
BEGIN DESCRIPTION:
Snow Creek 182.0
END DESCRIPTION:
XS GIS Cut Line= 3
      1648635.41      1007990.96      1648486.55      1007890.06
      1648358.79       1007741.4
#Sta/Elev= 23
  4820.2 1001.31    4837  993.21  4855.5  984.64  4875.8  974.07  4905.1  960.59
  4913.3  957.06  4916.4  955.81  4919.9  955.12  4967.1     951  4978.7  950.44
  4989.3  949.07  4992.9  947.77  5007.1  947.77 5009.33   949.4  5031.6  953.08
  5048.7  953.75  5061.9  954.79  5066.5  955.02  5091.7  962.29  5120.4  970.13
  5144.3  978.31  5165.1  983.93    5196  992.08
#Mann= 3 ,-1 , 0
  4820.2     .09       0  4989.3     .05       0 5009.33     .09       0
Bank Sta=4989.3,5009.33
Exp/Cntr=0.3,0.1

Type RM Length L Ch R = 1 ,90000   ,500,500,500
BEGIN DESCRIPTION:
Snow Creek 181.0
END DESCRIPTION:
XS GIS Cut Line= 3
      1648878.97      1007509.87      1648745.69      1007476.45
      1648503.11      1007428.69
#Sta/Elev= 30
  4862.6 1013.67  4868.1 1012.15  4871.4 1010.73    4878 1007.09  4886.8 1002.58
  4896.6  998.55  4911.5  990.99  4922.3   982.7  4943.7     970  4959.3     960
  4968.5     955  4983.3  949.83  4985.6  948.46 4991.79  945.63  4992.9  944.96
  5007.1  944.96 5009.04  945.75    5031  949.47  5037.2  949.97  5059.6  950.75
  5080.2   949.7  5106.9  951.08  5109.8  952.22  5157.7  968.07  5171.8  974.05
  5176.3  975.41  5201.2  982.75  5202.8  983.03  5227.2  989.63  5247.2  993.25
#Mann= 3 ,-1 , 0
  4862.6     .09       0 4991.79     .05       0 5009.04     .09       0
Bank Sta=4991.79,5009.04
Exp/Cntr=0.3,0.1

Type RM Length L Ch R = 1 ,89500   ,500,500,500
BEGIN DESCRIPTION:
Snow Creek 180.0
END DESCRIPTION:
XS GIS Cut Line= 3
      1648746.67      1006920.53      1648631.96        1007008.
      1648448.99      1007164.08
#Sta/Elev= 30
  4855.7 1008.09  4881.8 1004.72  4890.5 1002.15  4903.5  999.27  4909.3  996.94
  4929.9  989.92  4936.1  986.43  4948.2  982.18  4958.4  973.52  4959.1  972.65
  4977.9  957.46  4990.4  943.49  4992.9  940.68  5007.1  940.68  5008.2  943.93
  5017.8  944.83  5026.4  945.24  5032.2  946.55  5072.3  949.61  5095.4  952.47
  5109.6   953.9    5122  955.95  5133.7  958.56  5160.2   965.3  5168.5  966.99
  5199.9  975.43  5215.9  979.29  5224.7  981.12  5232.1  982.17  5240.5  984.24
#Mann= 3 ,-1 , 0
  4855.7     .09       0  4990.4     .05       0  5008.2     .09       0
Bank Sta=4990.4,5008.2
Exp/Cntr=0.3,0.1

Type RM Length L Ch R = 1 ,89000   ,500,500,500
BEGIN DESCRIPTION:
Snow Creek 179.0
END DESCRIPTION:
XS GIS Cut Line= 3
      1648512.14      1006619.85       1648349.4       1006618.6
      1648244.53      1006625.86
#Sta/Elev= 30
  4837.3  967.87    4840   967.2  4850.3  964.29  4865.5  960.47  4914.1  947.34
    4920  946.22  4930.5  945.02  4933.3  944.47  4935.7  944.52  4943.4  943.94
    4965  943.83 4986.99  941.53  4992.9  937.86  5007.1  937.86 5012.02  941.63
  5024.1  944.39  5032.1  947.92  5034.7  949.18  5042.2  953.45  5047.3  956.75
  5049.3  957.95    5058  963.81  5066.7  967.84    5070  969.65  5078.5  972.93
  5079.8  973.55  5090.8  979.61  5097.6  982.69  5102.5  984.54  5105.1  985.76
#Mann= 3 ,-1 , 0
  4837.3     .09       0 4986.99     .05       0 5012.02     .09       0
Bank Sta=4986.99,5012.02
Exp/Cntr=0.3,0.1

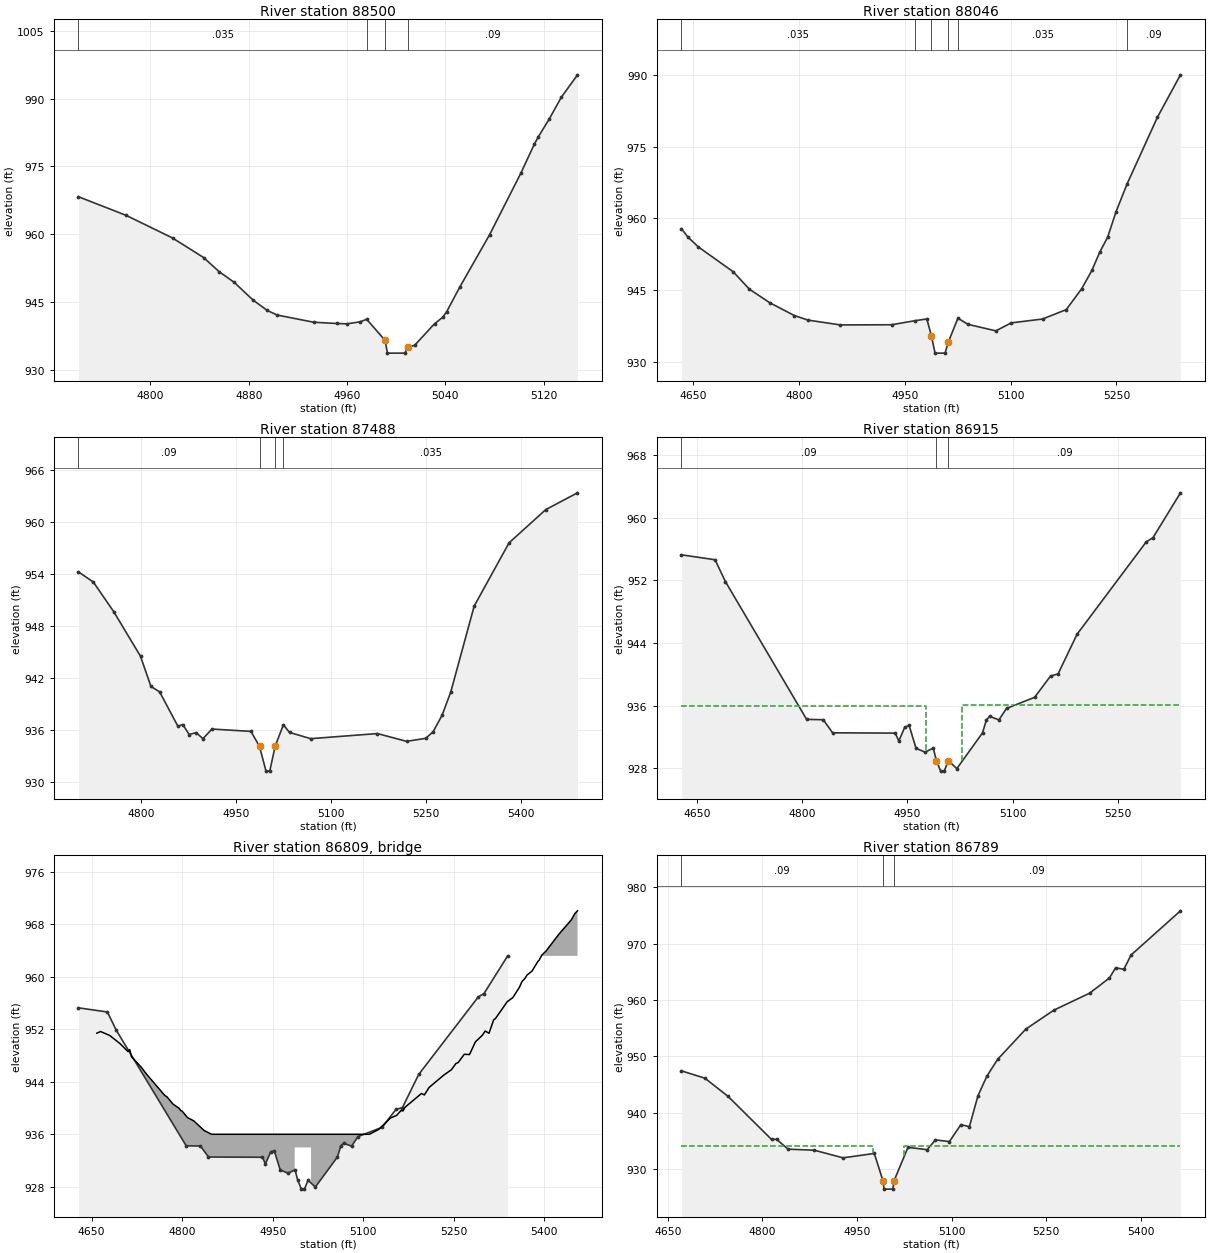
Type RM Length L Ch R = 1 ,88500   ,454,454,454
BEGIN DESCRIPTION:
Snow Creek 178.0
END DESCRIPTION:
XS GIS Cut Line= 3
      1648770.72      1006271.06      1648536.69      1006161.09
      1648403.89      1006096.66
#Sta/Elev= 30
  4741.4   968.3  4780.4  964.16  4818.1  959.16  4843.3  954.85  4855.8  951.75
  4868.1  949.39  4883.4  945.48  4894.9  943.19  4903.1  942.15  4932.9  940.56
  4951.5  940.28    4960  940.21  4970.5  940.64    4976  941.21 4990.96  936.55
  4992.9  933.73  5007.1  933.73 5009.33     935    5015  935.45  5031.2  940.22
  5037.8  941.64  5041.1  942.88  5051.8  948.35    5076  959.88  5101.5  973.52
  5112.5  979.94  5115.8  981.59  5124.5  985.44  5134.4  990.28  5147.6  995.25
#Mann= 4 ,-1 , 0
  4741.4    .035       0    4976     .09       0 4990.96     .05       0
 5009.33     .09       0
Bank Sta=4990.96,5009.33
Exp/Cntr=0.3,0.1

Type RM Length L Ch R = 1 ,88046   ,558,558,558
BEGIN DESCRIPTION:
Snow Creek 177.0
END DESCRIPTION:
XS GIS Cut Line= 4
      1649020.29      1006060.58      1648815.82        1005805.
      1648707.58      1005726.82      1648470.04      1005660.67
#Sta/Elev= 30
  4633.4  957.86  4642.6  956.11  4657.5  954.03  4706.8  948.85  4729.7   945.2
  4758.8  942.35  4793.4  939.69  4812.9  938.73  4858.7  937.72  4931.4  937.76
  4964.4  938.61  4981.2  938.97 4987.69  935.48  4992.9  931.82  5007.1  931.82
  5011.6  934.08  5025.3  939.13  5039.4  937.85  5079.1  936.48  5100.9  938.15
  5145.4  938.96  5178.9  940.93  5200.7  945.28  5215.3  949.15  5226.4  952.96
  5237.5  956.07  5249.6  961.46  5265.2  967.26  5308.1  981.18  5340.8  990.07
#Mann= 6 ,-1 , 0
  4633.4    .035       0  4964.4     .09       0 4987.69     .05       0
  5011.6     .09       0  5025.3    .035       0  5265.2     .09       0
Bank Sta=4987.69,5011.6
Exp/Cntr=0.3,0.1

Type RM Length L Ch R = 1 ,87488   ,573,573,573
BEGIN DESCRIPTION:
Snow Creek 176.0
END DESCRIPTION:
XS GIS Cut Line= 4
      1649296.92      1005645.64      1649170.63      1005429.15
      1649053.36      1005393.06      1648644.44       1005320.9
#Sta/Elev= 30
  4700.7  954.22  4724.3  953.03  4756.4  949.62  4798.7  944.47  4815.2  940.98
  4828.9  940.36  4857.7   936.4  4865.6  936.57  4875.7  935.43  4886.6  935.65
  4897.4  934.95  4911.6  936.06  4973.3  935.79  4986.8  934.05 4997.04   931.2
 5002.96   931.2  5011.5  934.08  5024.5  936.55  5034.2  935.67  5067.6  934.95
  5173.2  935.54  5219.1  934.64  5249.6  934.99  5261.2  935.76  5275.4  937.67
    5289  940.34    5326  950.26  5381.1  957.57  5439.1  961.41  5489.3  963.35
#Mann= 4 ,-1 , 0
  4700.7     .09       0  4986.8     .05       0  5011.5     .09       0
  5024.5    .035       0
Bank Sta=4986.8,5011.5
Exp/Cntr=0.5,0.3

Type RM Length L Ch R = 1 ,86915   ,126,126,126
BEGIN DESCRIPTION:
Doss Rd. SR-1653 - US
END DESCRIPTION:
XS GIS Cut Line= 6
      1649492.42      1005763.25      1649599.54      1005529.54
      1649599.54      1005479.23      1649558.96      1005396.46
      1649455.09      1005263.37      1649346.35      1005170.86
#Sta/Elev= 30
  4628.2  955.25  4676.1  954.62  4690.8  951.84  4806.6  934.25  4830.3  934.21
  4843.6  932.54    4933   932.5  4937.9  931.49  4946.4  933.25  4952.6  933.49
  4962.5  930.56  4975.5  930.07    4987  930.59  4991.5     929  4997.5  927.65
  5002.6  927.65  5008.5     929  5020.6  927.97  5057.2  932.53  5062.8   934.2
  5067.5  934.63  5080.6  934.19  5091.4  935.65  5131.5  937.07  5154.1  939.78
  5164.9  940.06  5191.9  945.11  5290.6  956.91  5300.1  957.43  5339.3  963.16
#Mann= 3 ,-1 , 0
  4628.2     .09       0  4991.5     .05       0  5008.5     .09       0
#XS Ineff= 2 , 0
       0  4976.2     936  5028.3       0  936.11
Permanent Ineff=
       F       F
Bank Sta=4991.5,5008.5
Exp/Cntr=0.5,0.3

Type RM Length L Ch R = 3 ,86809   ,,,
BEGIN DESCRIPTION:
Doss Rd. SR-1653
Structure ID: Doss Rd
Approximate Survey Structure
END DESCRIPTION:
Bridge Culvert--1,0,-1,-1, 0
Deck Dist Width WeirC Skew NumUp NumDn MinLoCord MaxHiCord MaxSubmerge Is_Ogee
70,17,3,0, 60, 60, , , , 0, 1,1,,
  4658.6  4664.7    4680  4697.1    4710  4713.1    4716  4732.9  4740.2    4771
  4774.7  4784.9  4795.1  4797.6  4799.8    4809  4819.1  4836.1  4848.7  4986.5
  4986.5  5013.5  5013.5  5110.1  5125.6  5145.1  5155.3  5162.8  5165.6  5169.2
  5196.5  5201.3  5209.1  5233.3  5246.1  5253.4  5257.3  5267.4  5276.1  5285.8
  5297.4    5302  5308.4  5316.1  5318.9  5338.7  5347.9  5358.6  5362.9  5368.2
  5371.2  5379.5  5389.4  5391.4  5395.8  5402.7  5424.1  5444.8  5450.5    5455
  951.39  951.65  951.04   949.8  948.61   948.9   947.8  946.14  945.23  941.93
  941.71  940.59  939.94   939.6  939.54  938.53  938.05  936.59     936     936
     936     936     936     936  936.74  938.48  938.87  939.64  939.54  940.11
  942.21  941.99  943.13     945  945.83  946.76  946.92  948.18  948.14  950.07
  951.08  951.72  951.38  953.43   953.6   956.2  956.81  958.36  959.24  959.76
  960.23  960.83  962.32  962.49  963.27  963.88  966.45  968.65  969.59  970.02
  906.68  906.68  906.68  906.68  906.68  906.68  906.68  906.68  906.68  906.68
  906.68  906.68  906.68  906.68  906.68  906.68  906.68  906.68  906.68  906.68
     934     934  906.68  906.68  906.68  906.68  906.68  906.68  906.68  906.68
  906.68  906.68  906.68  906.68  906.68  906.68  906.68  906.68  906.68  906.68
  906.68  906.68  906.68  906.68  906.68  906.68  906.68  906.68  906.68  906.68
  906.68  906.68  906.68  906.68  906.68  906.68  906.68  906.68  906.68  906.68
  4658.6  4664.7    4680  4697.1    4710  4713.1    4716  4732.9  4740.2    4771
  4774.7  4784.9  4795.1  4797.6  4799.8    4809  4819.1  4836.1  4848.7  4986.5
  4986.5  5013.5  5013.5  5110.1  5125.6  5145.1  5155.3  5162.8  5165.6  5169.2
  5196.5  5201.3  5209.1  5233.3  5246.1  5253.4  5257.3  5267.4  5276.1  5285.8
  5297.4    5302  5308.4  5316.1  5318.9  5338.7  5347.9  5358.6  5362.9  5368.2
  5371.2  5379.5  5389.4  5391.4  5395.8  5402.7  5424.1  5444.8  5450.5    5455
  951.39  951.65  951.04   949.8  948.61   948.9   947.8  946.14  945.23  941.93
  941.71  940.59  939.94   939.6  939.54  938.53  938.05  936.59     936     936
     936     936     936     936  936.74  938.48  938.87  939.64  939.54  940.11
  942.21  941.99  943.13     945  945.83  946.76  946.92  948.18  948.14  950.07
  951.08  951.72  951.38  953.43   953.6   956.2  956.81  958.36  959.24  959.76
  960.23  960.83  962.32  962.49  963.27  963.88  966.45  968.65  969.59  970.02
  906.68  906.68  906.68  906.68  906.68  906.68  906.68  906.68  906.68  906.68
  906.68  906.68  906.68  906.68  906.68  906.68  906.68  906.68  906.68  906.68
     934     934  906.68  906.68  906.68  906.68  906.68  906.68  906.68  906.68
  906.68  906.68  906.68  906.68  906.68  906.68  906.68  906.68  906.68  906.68
  906.68  906.68  906.68  906.68  906.68  906.68  906.68  906.68  906.68  906.68
  906.68  906.68  906.68  906.68  906.68  906.68  906.68  906.68  906.68  906.68
Abutment Skew #Up #Dn= , 2 , 2
  4986.5  4987.5
     934  930.41
  4986.5  4987.5
     934  928.12
Abutment Skew #Up #Dn= , 2 , 2
  5012.5  5013.5
  928.66     934
  5012.5  5013.5
   928.9     934
BR Coef= 1 , 1 , 0 ,1.25, 0 ,,,0.8,0,2,0,
WSPro=,,,, 1 ,,,, 0 ,,,, 0 ,,,,-1 ,-1 ,-1 , 0 , 0 , 0 , 0 , 0
BC Design=,, 0 ,, 0 ,,,,,,
BC HTab HWMax=963.16

Type RM Length L Ch R = 1 ,86789   ,289,289,289
BEGIN DESCRIPTION:
Doss Rd. SR-1653 - DS
END DESCRIPTION:
XS GIS Cut Line= 6
      1649539.49       1005802.2      1649606.03      1005691.84
      1649657.96       1005540.9      1649677.44      1005451.64
      1649562.21      1005274.73      1649417.76      1005135.16
#Sta/Elev= 30
  4671.5  947.41  4708.7  946.11  4745.6  942.87  4814.4  935.25  4822.4  935.27
  4840.8  933.52  4882.5  933.33  4927.9  931.98  4977.5  932.76  4991.5  927.82
    4993  926.43    5007  926.43  5008.5  927.82  5030.9  933.84  5061.4  933.43
  5074.5  935.16  5096.7  934.87  5114.8  937.86  5128.4  937.52  5141.9  942.97
  5156.2  946.49  5173.4  949.48  5217.8  954.81  5262.4  958.18  5319.1  961.19
  5350.6  963.89  5360.3  965.68  5373.5  965.44  5384.9  967.96  5463.3   975.8
#Mann= 3 ,-1 , 0
  4671.5     .09       0  4991.5     .05       0  5008.5     .09       0
#XS Ineff= 2 , 0
       0    4975     934    5025       0     934
Permanent Ineff=
       F       F
Bank Sta=4991.5,5008.5
Exp/Cntr=0.5,0.3