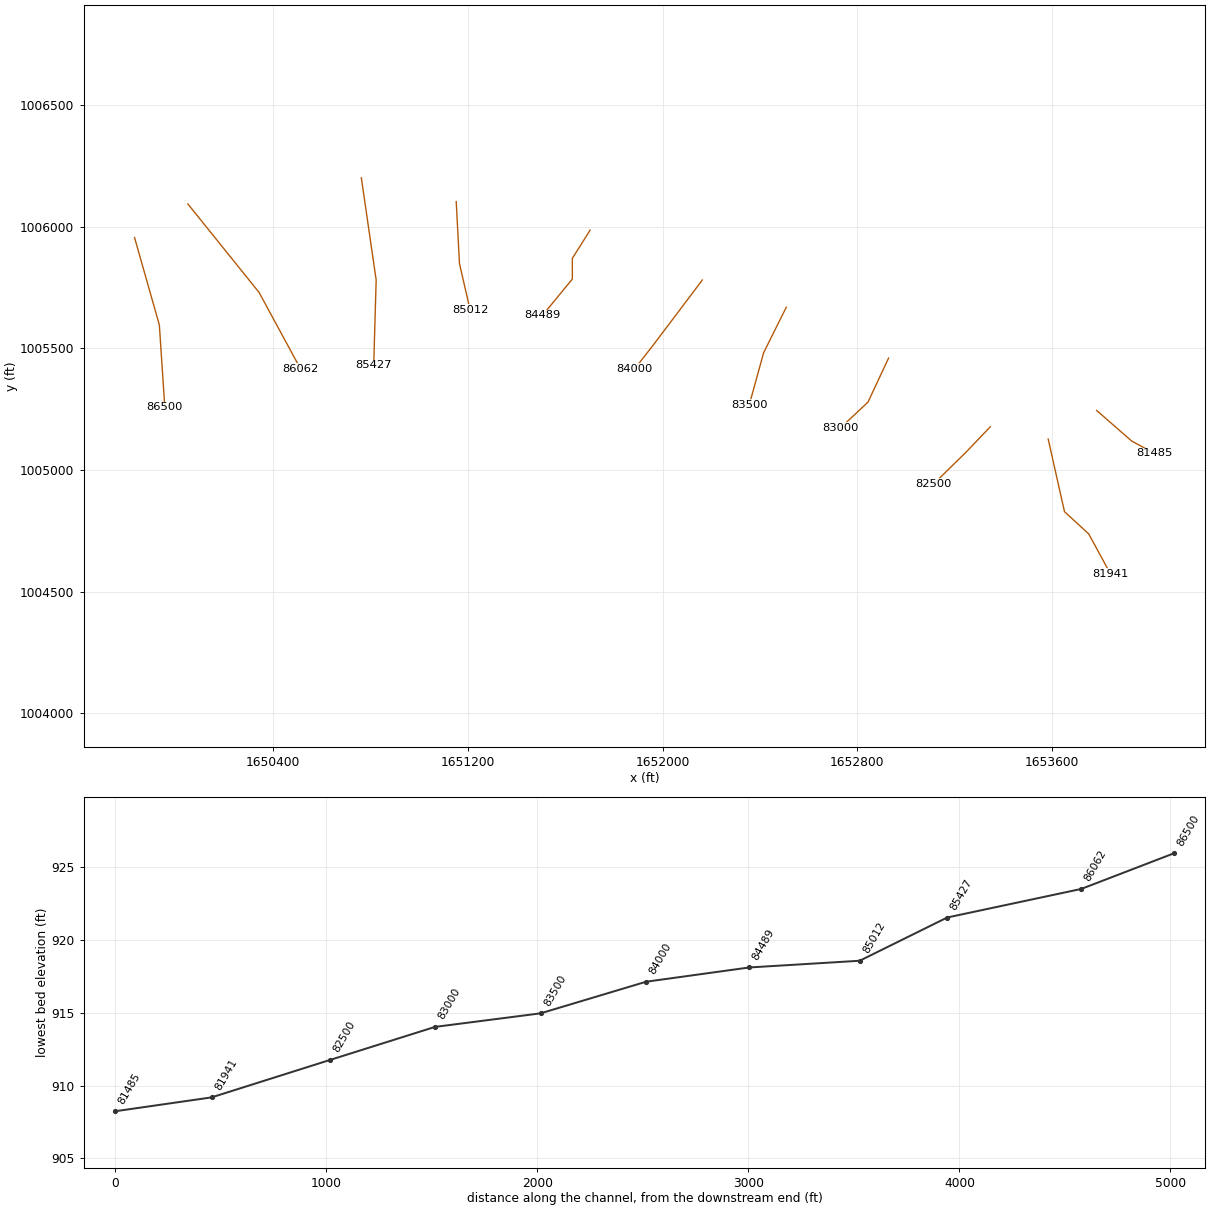
HEC-RAS study lds_snow_crk.prj: Snow Creek Limited Detail Study

--- lds_snow_crk.g02 (geometry) --- (continued)

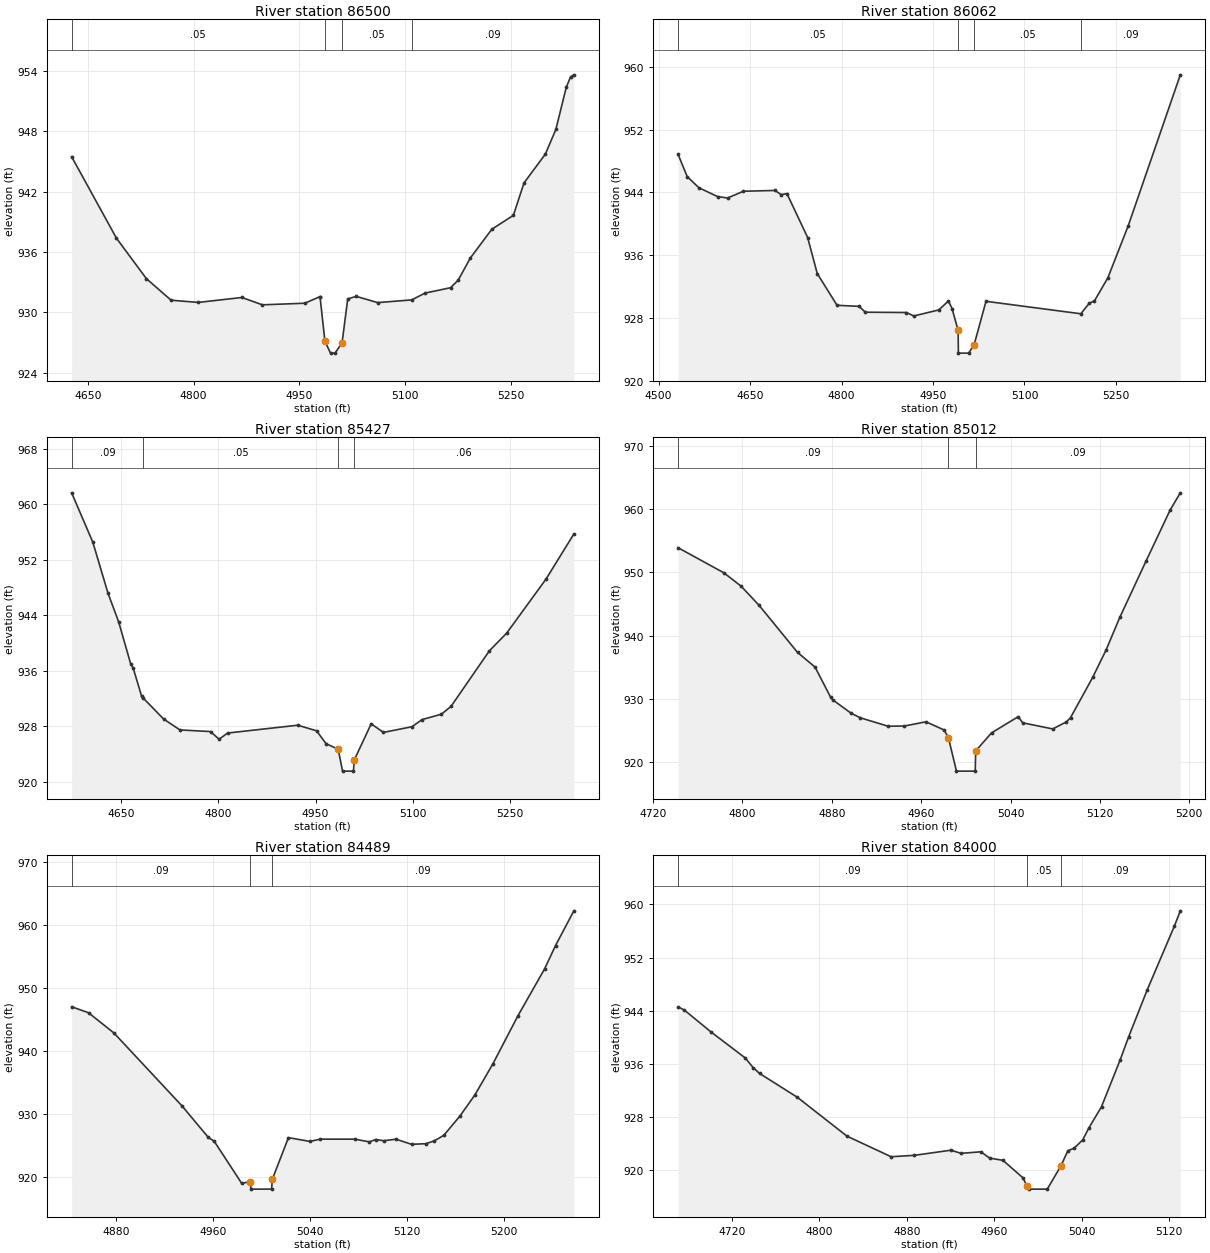
Type RM Length L Ch R = 1 ,86500   ,438,438,438
BEGIN DESCRIPTION:
Snow Creek 174.0
END DESCRIPTION:
XS GIS Cut Line= 3
      1649832.23      1005954.56      1649934.08      1005595.76
      1649956.59      1005256.88
#Sta/Elev= 30
    4627  945.46  4690.6  937.36  4733.1  933.34  4768.1   931.2  4806.5  930.98
  4868.6  931.47  4897.7  930.74  4957.9   930.9  4978.8  931.54  4979.5  931.51
  4986.4  927.12 4994.33  925.94 5000.69  925.94 5010.73  926.96 5018.74  931.33
 5030.84  931.58  5061.2  930.96  5109.5  931.23  5128.6  931.91  5164.6  932.44
  5175.5  933.19  5192.7  935.39  5223.3  938.26  5253.8  939.63  5268.9  942.86
  5299.1  945.71  5314.1  948.17  5328.8  952.35  5334.9  953.39  5339.6   953.6
#Mann= 4 ,-1 , 0
    4627     .05       0  4986.4    .045       0 5010.73     .05       0
  5109.5     .09       0
Bank Sta=4986.4,5010.73
Exp/Cntr=0.3,0.1

Type RM Length L Ch R = 1 ,86062   ,635,635,635
BEGIN DESCRIPTION:
Snow Creek 173.0
END DESCRIPTION:
XS GIS Cut Line= 3
      1650051.33      1006092.51      1650343.47      1005729.37
      1650513.88      1005414.92
#Sta/Elev= 30
  4531.9  948.84  4546.8  946.02  4565.9   944.6  4596.6  943.47    4613  943.29
    4639  944.15  4690.7  944.25    4701  943.72  4710.4  943.85  4744.4  938.24
  4760.1  933.65  4792.6   929.6  4828.5  929.47  4839.1  928.72  4906.4  928.68
  4918.5  928.24  4959.4  929.01  4975.3  930.15  4981.2  929.19  4991.2  926.39
  4991.6   923.5  5008.4   923.5  5017.5  924.59  5036.9  930.11  5192.5  928.52
  5206.2  929.86  5214.8  930.17  5236.8  933.11  5270.2  939.75  5355.6     959
#Mann= 4 ,-1 , 0
  4531.9     .05       0  4991.2    .045       0  5017.5     .05       0
  5192.5     .09       0
Bank Sta=4991.2,5017.5
Exp/Cntr=0.3,0.1

Type RM Length L Ch R = 1 ,85427   ,415,415,415
BEGIN DESCRIPTION:
Snow Creek 172.0
END DESCRIPTION:
XS GIS Cut Line= 3
      1650763.41      1006200.03      1650824.27      1005780.09
      1650814.13      1005429.12
#Sta/Elev= 30
  4573.3  961.65    4606  954.53  4629.5  947.16    4646  943.02  4664.5  936.98
  4668.4  936.36  4681.4  932.31  4683.7  932.08  4715.3  929.05  4740.5  927.48
  4787.7  927.24  4800.9  926.14  4814.2  927.03  4922.5  928.16  4951.5  927.35
  4966.1   925.5  4984.8   924.7  4991.6  921.54  5008.4  921.54  5009.7  923.15
  5035.8  928.36  5054.7  927.12  5098.8  927.94  5114.4  928.97  5144.1  929.74
    5159  930.86  5218.2  938.87  5245.2  941.45  5305.9  949.24  5348.7  955.71
#Mann= 4 ,-1 , 0
  4573.3     .09       0  4683.7     .05       0  4984.8    .045       0
  5009.7     .06       0
Bank Sta=4984.8,5009.7
Exp/Cntr=0.3,0.1

Type RM Length L Ch R = 1 ,85012   ,523,523,523
BEGIN DESCRIPTION:
Snow Creek 171.0
END DESCRIPTION:
XS GIS Cut Line= 3
      1651152.93      1006102.65      1651166.31      1005848.04
      1651209.73      1005658.36
#Sta/Elev= 30
  4742.4  953.89  4783.4  949.92  4798.8  947.81  4814.9  944.78  4849.3  937.34
    4865  935.02    4879  930.23  4881.1  929.81    4897  927.76  4905.4  927.01
  4930.3  925.67  4944.9   925.7  4964.3  926.37  4980.6  925.07  4984.4  923.85
  4991.6  918.57  5008.4  918.57  5008.8  921.76    5023  924.62  5046.9  927.18
  5050.9  926.21  5077.8  925.24  5090.1  926.36  5093.7  927.02  5113.6  933.41
  5125.6  937.74  5137.8  942.87  5161.5  951.85  5182.9  959.85    5192  962.57
#Mann= 3 ,-1 , 0
  4742.4     .09       0  4984.4     .05       0  5008.8     .09       0
Bank Sta=4984.4,5008.8
Exp/Cntr=0.3,0.1

Type RM Length L Ch R = 1 ,84489   ,489,489,489
BEGIN DESCRIPTION:
Snow Creek 170.0
END DESCRIPTION:
XS GIS Cut Line= 4
      1651702.71      1005984.99      1651629.68      1005869.35
      1651629.68      1005784.15      1651507.95      1005636.05
#Sta/Elev= 30
  4843.7  947.01  4857.6  946.06  4878.6  942.84  4934.6   931.3  4956.3   926.3
  4961.2  925.68  4983.8  919.02  4990.7   919.3  4991.6  918.11  5008.4  918.11
 5009.04  919.69  5022.3  926.27  5039.9  925.67  5048.6  926.03  5076.8  926.03
  5088.9   925.6  5094.3  925.97  5100.6  925.78    5111  926.02  5123.7  925.21
  5135.5  925.31  5142.4  925.75  5150.3  926.64  5163.4  929.65  5175.9  933.04
  5190.8  937.99  5211.2  945.53  5233.3  953.01  5242.3   956.7  5257.4  962.21
#Mann= 3 ,-1 , 0
  4843.7     .09       0  4990.7     .05       0 5009.04     .09       0
Bank Sta=4990.7,5009.04
Exp/Cntr=0.3,0.1

Type RM Length L Ch R = 1 ,84000   ,500,500,500
BEGIN DESCRIPTION:
Snow Creek 169.0
END DESCRIPTION:
XS GIS Cut Line= 3
      1652163.23      1005780.09      1651965.25      1005517.44
      1651885.29      1005414.92
#Sta/Elev= 30
  4671.1  944.58  4676.9  944.08  4701.3  940.78  4732.4  936.89  4739.6  935.44
  4745.5  934.55  4779.9  930.98  4825.4  925.11  4865.7  922.01  4887.1  922.22
  4920.2  922.99  4929.8  922.52  4947.8  922.75  4955.8   921.8  4967.9  921.47
  4986.3  918.82  4989.9  917.59  4991.6  917.13  5008.4  917.13  5020.8  920.59
  5027.2   922.9  5033.1  923.31  5040.8  924.54  5046.3   926.3    5058  929.55
  5074.9  936.53  5082.9  940.11  5099.8  947.15  5124.6  956.75    5130  959.04
#Mann= 3 ,-1 , 0
  4671.1     .09       0  4989.9     .05       0  5020.8     .09       0
Bank Sta=4989.9,5020.8
Exp/Cntr=0.3,0.1

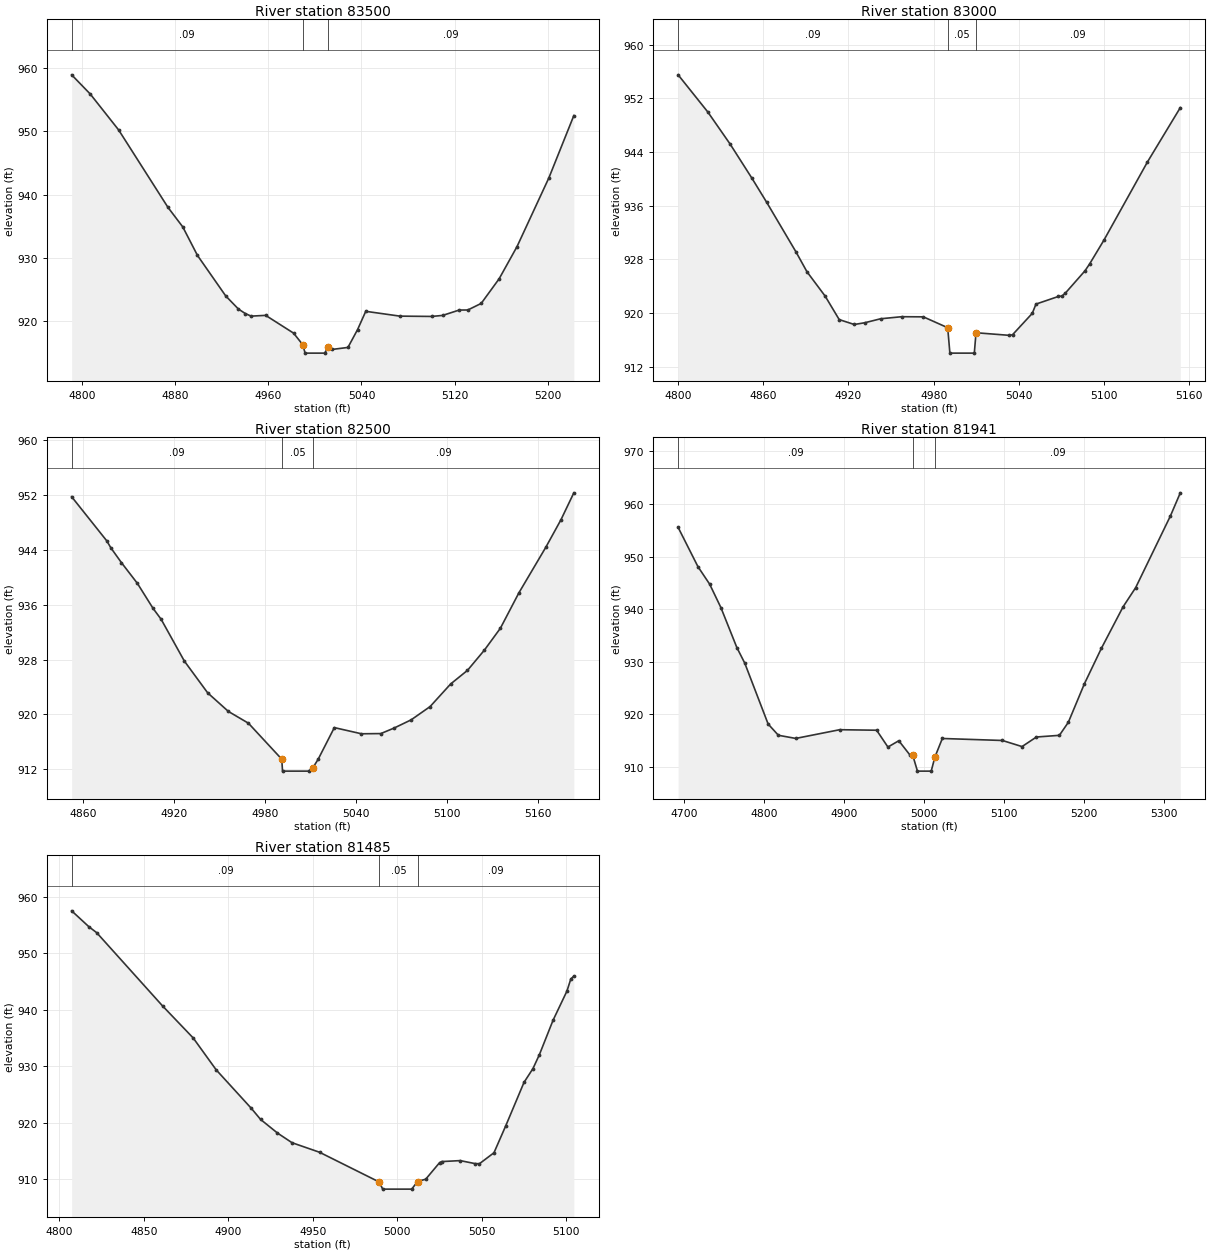
Type RM Length L Ch R = 1 ,83500   ,500,500,500
BEGIN DESCRIPTION:
Snow Creek 168.0
END DESCRIPTION:
XS GIS Cut Line= 3
      1652508.11      1005668.51      1652414.97       1005481.4
      1652355.96      1005266.82
#Sta/Elev= 30
    4791  958.96    4807  955.92  4831.4  950.24  4873.7  938.02  4886.5  934.91
  4899.1  930.41  4923.4     924  4934.3  921.93  4940.2  921.22  4945.2  920.81
  4957.7  920.93  4981.7  918.12 4989.57  916.29  4991.6  914.96  5008.4  914.96
 5011.62  915.95  5015.1  915.55  5028.4  915.86  5036.7  918.69  5043.7  921.57
    5073  920.81  5100.3  920.76  5109.7  920.92    5124  921.77  5131.4  921.78
  5142.9  922.82  5158.3  926.71  5173.7  931.81  5201.1  942.69  5222.5  952.52
#Mann= 3 ,-1 , 0
    4791     .09       0 4989.57     .05       0 5011.62     .09       0
Bank Sta=4989.57,5011.62
Exp/Cntr=0.3,0.1

Type RM Length L Ch R = 1 ,83000   ,500,500,500
BEGIN DESCRIPTION:
Snow Creek 167.0
END DESCRIPTION:
XS GIS Cut Line= 3
      1652928.05      1005459.55      1652843.45      1005278.48
      1652731.27       1005173.5
#Sta/Elev= 30
  4800.1  955.52    4821  949.98  4836.7   945.2  4852.1  940.09  4862.4  936.53
  4883.1  929.11  4890.8  926.16  4903.6  922.53  4913.5  919.03  4924.1   918.3
  4931.5  918.56  4942.6  919.15  4957.5  919.46  4972.7  919.44 4989.87  917.82
  4991.4  914.03  5008.6  914.03  5009.8  917.07  5033.3  916.68  5035.5  916.77
  5049.4  919.96    5052  921.34  5067.8  922.48  5070.3  922.54  5072.7  922.98
  5086.5   926.3  5089.8  927.34  5099.8  930.86  5130.5  942.54  5153.6  950.63
#Mann= 3 ,-1 , 0
  4800.1     .09       0 4989.87     .05       0  5009.8     .09       0
Bank Sta=4989.87,5009.8
Exp/Cntr=0.3,0.1

Type RM Length L Ch R = 1 ,82500   ,559,559,559
BEGIN DESCRIPTION:
Snow Creek 166.0
END DESCRIPTION:
XS GIS Cut Line= 3
      1653345.97      1005177.56      1653243.87      1005070.74
      1653112.67      1004942.23
#Sta/Elev= 30
  4852.2  951.72  4875.4  945.29  4878.1  944.27  4885.1  942.11  4895.6   939.1
  4905.9  935.47  4911.3  933.86  4926.6  927.78    4942  923.15  4955.7  920.44
  4968.9  918.73  4990.9  913.49  4991.4  911.75  5008.6  911.75  5011.5  912.26
  5014.9  913.47  5025.6  918.09  5043.5  917.19  5056.3  917.22    5065  918.02
  5076.3  919.22  5088.8  921.15  5102.4  924.45  5113.5  926.43  5124.7  929.39
  5135.2  932.56  5147.4  937.71  5165.2  944.36  5175.2  948.37  5183.7  952.29
#Mann= 3 ,-1 , 0
  4852.2     .09       0  4990.9     .05       0  5011.5     .09       0
Bank Sta=4990.9,5011.5
Exp/Cntr=0.3,0.1

Type RM Length L Ch R = 1 ,81941   ,456,456,456
BEGIN DESCRIPTION:
Snow Creek 165.0
END DESCRIPTION:
XS GIS Cut Line= 4
      1653583.33      1005126.84      1653650.28      1004828.62
      1653749.69      1004737.33      1653838.95        1004573.
#Sta/Elev= 30
  4692.3  955.56  4717.1  948.08  4731.7  944.76  4745.8  940.29  4765.7   932.7
  4775.6  929.73  4804.8  918.15  4817.6  916.01  4839.3  915.41  4894.3  917.07
  4940.4  916.97  4954.5  913.77  4968.1  914.97  4982.2  912.22  4985.5  912.22
  4991.4  909.19  5008.6  909.19  5013.2  911.86  5022.5   915.4  5097.6  915.02
  5122.1  913.86  5140.1  915.68  5168.8     916    5180  918.49    5200  925.79
  5221.3  932.56  5248.4  940.45  5264.1  944.09  5307.5  957.72  5319.9  962.13
#Mann= 3 ,-1 , 0
  4692.3     .09       0  4985.5     .05       0  5013.2     .09       0
Bank Sta=4985.5,5013.2
Exp/Cntr=0.3,0.1

Type RM Length L Ch R = 1 ,81485   ,485,485,485
BEGIN DESCRIPTION:
Snow Creek 164.0
END DESCRIPTION:
XS GIS Cut Line= 3
      1653782.14      1005244.51      1653926.18      1005118.73
       1654019.5      1005068.01
#Sta/Elev= 30
  4807.2  957.52  4817.5  954.68    4822  953.66  4861.1  940.66  4879.2     935
  4892.8  929.36  4913.5  922.58  4919.1  920.58  4929.1  918.17  4937.7  916.46
    4954  914.77 4989.42  909.49  4991.4  908.24  5008.6  908.24 5012.02  909.59
 5016.88     910  5025.1  912.93  5026.4  913.12  5037.3  913.29  5046.1  912.76
  5048.7  912.74  5057.3  914.68  5064.3  919.47  5075.1  927.15  5080.4  929.59
  5084.2  932.05  5092.3  938.15  5100.5   943.3  5102.8  945.44  5104.6  945.96
#Mann= 3 ,-1 , 0
  4807.2     .09       0 4989.42     .05       0 5012.02     .09       0
Bank Sta=4989.42,5012.02
Exp/Cntr=0.3,0.1