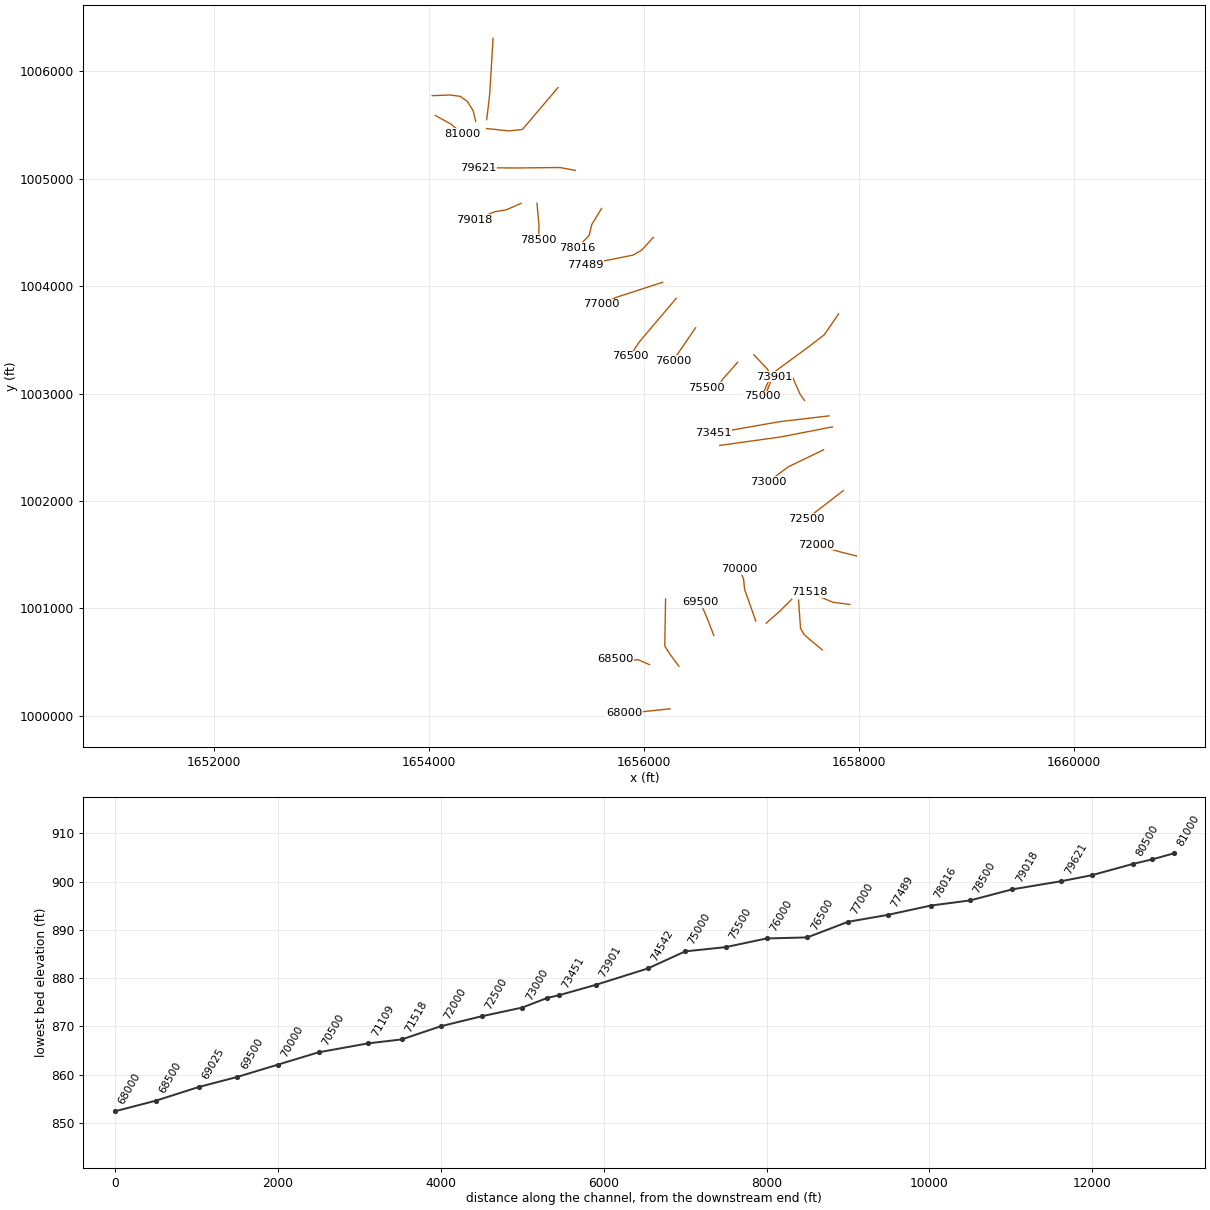
HEC-RAS study lds_snow_crk.prj: Snow Creek Limited Detail Study

--- lds_snow_crk.g02 (geometry) --- (continued)

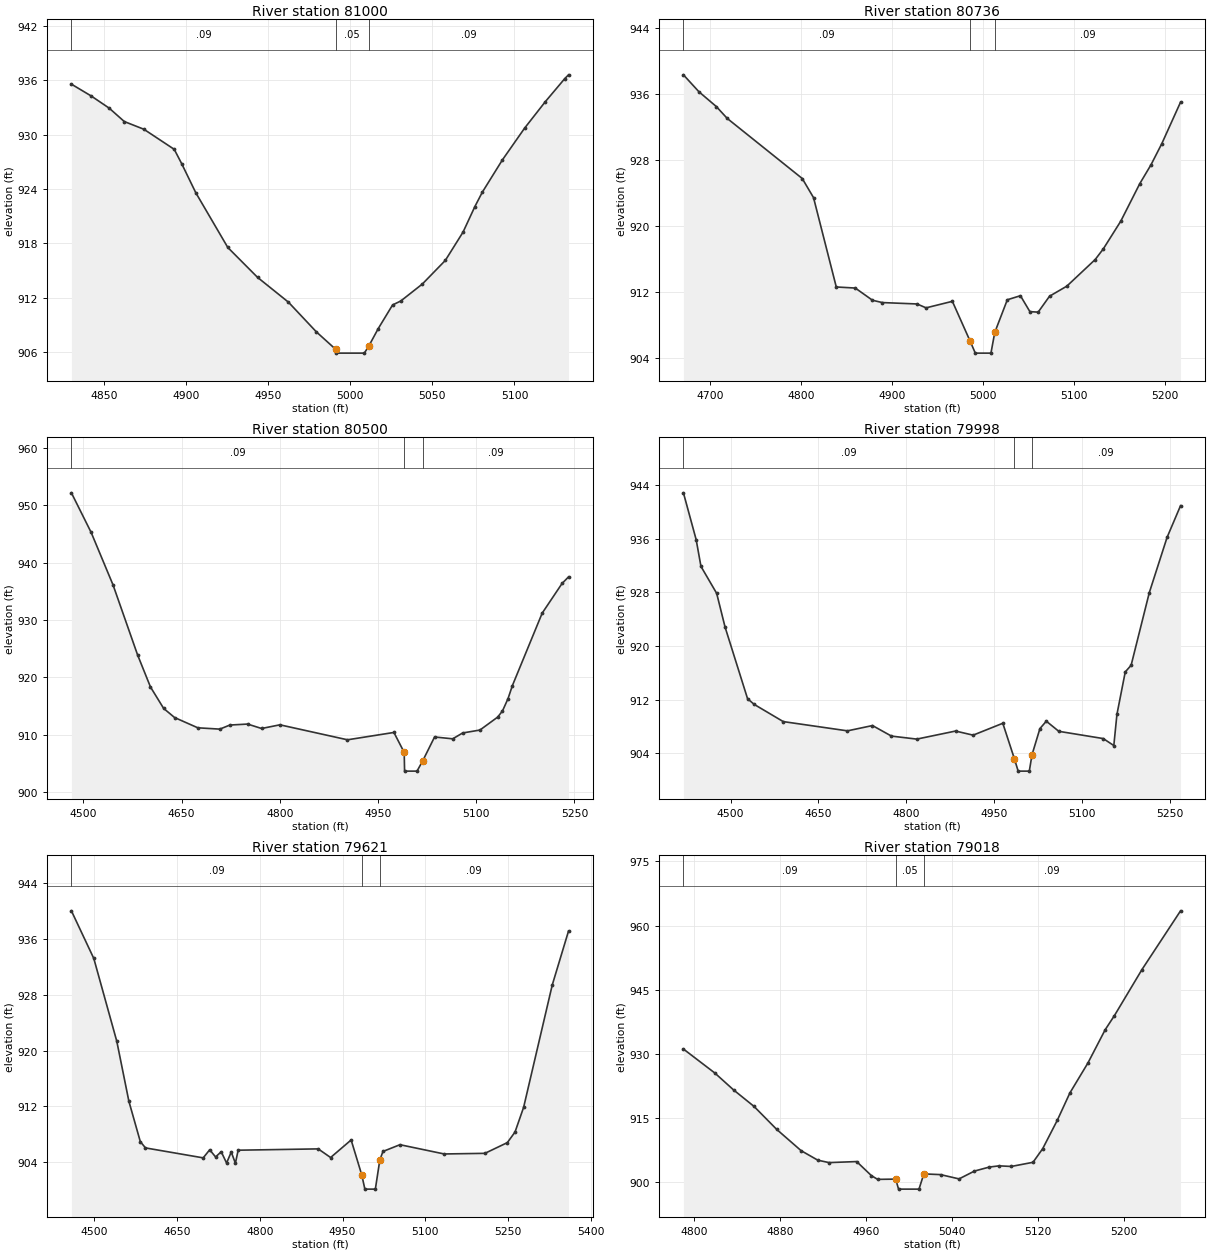
Type RM Length L Ch R = 1 ,81000   ,264,264,264
BEGIN DESCRIPTION:
Snow Creek 163.0
END DESCRIPTION:
XS GIS Cut Line= 3
      1654058.05      1005589.39      1654206.53      1005507.28
      1654307.58        1005421.
#Sta/Elev= 29
  4830.3  935.57  4842.3  934.27  4853.3  932.92  4862.5  931.44  4874.4  930.59
  4892.9  928.37  4897.5  926.76    4906  923.58  4925.5  917.53  4943.6  914.23
  4962.4  911.49  4979.4  908.21  4991.1  906.29  4991.4  905.86  5008.6  905.86
  5011.2   906.6  5017.1  908.58  5025.8  911.18  5030.8  911.62  5043.9  913.49
  5057.9   916.1  5068.7  919.23  5075.9  922.05  5080.4  923.63  5092.6  927.19
  5106.2  930.72  5118.8  933.64  5130.6  936.18  5132.9   936.6
#Mann= 3 ,-1 , 0
  4830.3     .09       0  4991.1     .05       0  5011.2     .09       0
Bank Sta=4991.1,5011.2
Exp/Cntr=0.3,0.1

Type RM Length L Ch R = 1 ,80736   ,236,236,236
BEGIN DESCRIPTION:
Snow Creek 162.5
END DESCRIPTION:
XS GIS Cut Line= 6
      1654029.51      1005773.64      1654195.93      1005779.92
      1654290.13      1005767.36      1654356.07      1005720.26
      1654409.45      1005635.48      1654434.57        1005535.
#Sta/Elev= 30
  4670.6  938.36  4687.7   936.3  4706.7  934.52  4718.8  933.07  4801.2  925.79
  4813.6  923.47  4838.6  912.64  4859.5  912.51  4878.4  911.03  4889.2  910.75
  4927.4  910.58  4937.3  910.11  4966.2   910.9  4985.8  906.05  4991.4  904.62
  5008.6  904.62  5012.8  907.13  5026.6  911.09    5041  911.58  5051.4  909.65
  5060.5  909.59    5073  911.52    5092  912.74  5123.2  915.97  5132.1  917.26
  5151.3  920.62  5172.2  925.17  5184.5  927.45  5196.4  930.02    5217  935.05
#Mann= 3 ,-1 , 0
  4670.6     .09       0  4985.8     .05       0  5012.8     .09       0
Bank Sta=4985.8,5012.8
Exp/Cntr=0.3,0.1

Type RM Length L Ch R = 1 ,80500   ,502,502,502
BEGIN DESCRIPTION:
Snow Creek 162.0
END DESCRIPTION:
XS GIS Cut Line= 3
      1654595.66      1006307.55      1654564.61      1005790.11
      1654536.83      1005550.84
#Sta/Elev= 30
  4481.6  952.18  4511.8  945.27  4545.2  936.13  4582.7  923.93  4602.4  918.34
  4622.5  914.61  4639.2  913.02  4674.7  911.23  4708.3     911  4723.6  911.71
  4750.7  911.88  4772.1  911.11  4800.1  911.75  4903.3  909.14  4974.2  910.42
  4989.9  906.94  4990.5  903.68  5009.5  903.68  5018.4  905.52  5036.3  909.63
    5064  909.31  5079.2  910.33  5105.6  910.84  5132.6  913.09    5140  914.16
  5148.5  916.32  5155.2   918.6  5200.7  931.22    5231  936.38  5240.9  937.53
#Mann= 3 ,-1 , 0
  4481.6     .09       0  4989.9     .05       0  5018.4     .09       0
Bank Sta=4989.9,5018.4
Exp/Cntr=0.3,0.1

Type RM Length L Ch R = 1 ,79998   ,377,377,377
BEGIN DESCRIPTION:
Snow Creek 161.0
END DESCRIPTION:
XS GIS Cut Line= 4
      1655200.22      1005849.06      1654869.54      1005459.55
      1654743.76      1005445.35       1654534.8      1005467.67
#Sta/Elev= 30
  4419.7  942.81  4441.4  935.84  4449.6  931.85  4476.4  927.83  4490.7  922.81
  4529.1  912.13  4540.6  911.28  4589.9  908.73  4699.4  907.35  4742.1  908.14
  4774.4  906.57  4817.6  906.12  4883.7  907.32  4913.7  906.71  4964.3  908.48
 4983.91  903.23  4990.5  901.35  5009.5  901.35  5014.1  903.79  5027.6  907.69
  5038.5  908.79  5059.8  907.28  5135.6   906.2  5153.6  905.16  5158.9   909.8
  5173.1  916.13  5183.1  917.12  5214.1  927.94  5244.4  936.17  5267.4   940.9
#Mann= 3 ,-1 , 0
  4419.7     .09       0 4983.91     .05       0  5014.1     .09       0
Bank Sta=4983.91,5014.1
Exp/Cntr=0.3,0.1

Type RM Length L Ch R = 1 ,79621   ,603,603,603
BEGIN DESCRIPTION:
Snow Creek 160.0
END DESCRIPTION:
XS GIS Cut Line= 4
      1655360.49      1005078.15      1655216.45      1005104.52
      1654824.91      1005100.47      1654461.77       1005102.5
#Sta/Elev= 30
  4458.5  940.07  4499.1  933.23  4540.8  921.33  4562.7  912.72  4583.4  906.93
  4592.8  906.02  4697.4  904.59  4709.2  905.75  4719.9  904.72  4730.1  905.47
  4739.8  903.85  4748.3  905.43  4755.8  903.81  4760.8  905.69  4905.9  905.88
  4928.4  904.64  4965.6  907.16 4984.91  902.13  4990.5   900.1  5009.5   900.1
  5017.6  904.28  5023.3  905.51  5054.1  906.48  5134.3  905.15  5208.1  905.24
  5248.8  906.78  5262.7   908.3  5278.3  911.85  5330.2  929.42  5359.7  937.17
#Mann= 3 ,-1 , 0
  4458.5     .09       0 4984.91     .05       0  5017.6     .09       0
Bank Sta=4984.91,5017.6
Exp/Cntr=0.3,0.1

Type RM Length L Ch R = 1 ,79018   ,518,518,518
BEGIN DESCRIPTION:
Snow Creek 159.0
END DESCRIPTION:
XS GIS Cut Line= 4
      1654857.11      1004771.05      1654717.64      1004710.19
      1654611.13      1004692.44      1654423.47      1004616.36
#Sta/Elev= 30
  4790.3  931.15  4819.5  925.55  4836.9  921.61    4856  917.74  4877.1  912.37
  4899.8   907.4  4915.4  905.17  4925.8  904.61  4951.5  904.85  4965.2  901.57
    4971  900.69 4987.79  900.75  4990.5  898.41  5009.5  898.41    5014  901.97
  5029.6   901.8  5046.8   900.8  5061.1  902.63    5075  903.57    5084  903.85
  5095.4  903.71  5115.6  904.68  5124.6  907.86  5138.2   914.5  5149.9  920.88
  5166.7  927.89  5182.8  935.68  5191.3  938.94    5217  949.73  5252.9  963.45
#Mann= 3 ,-1 , 0
  4790.3     .09       0 4987.79     .05       0    5014     .09       0
Bank Sta=4987.79,5014
Exp/Cntr=0.3,0.1

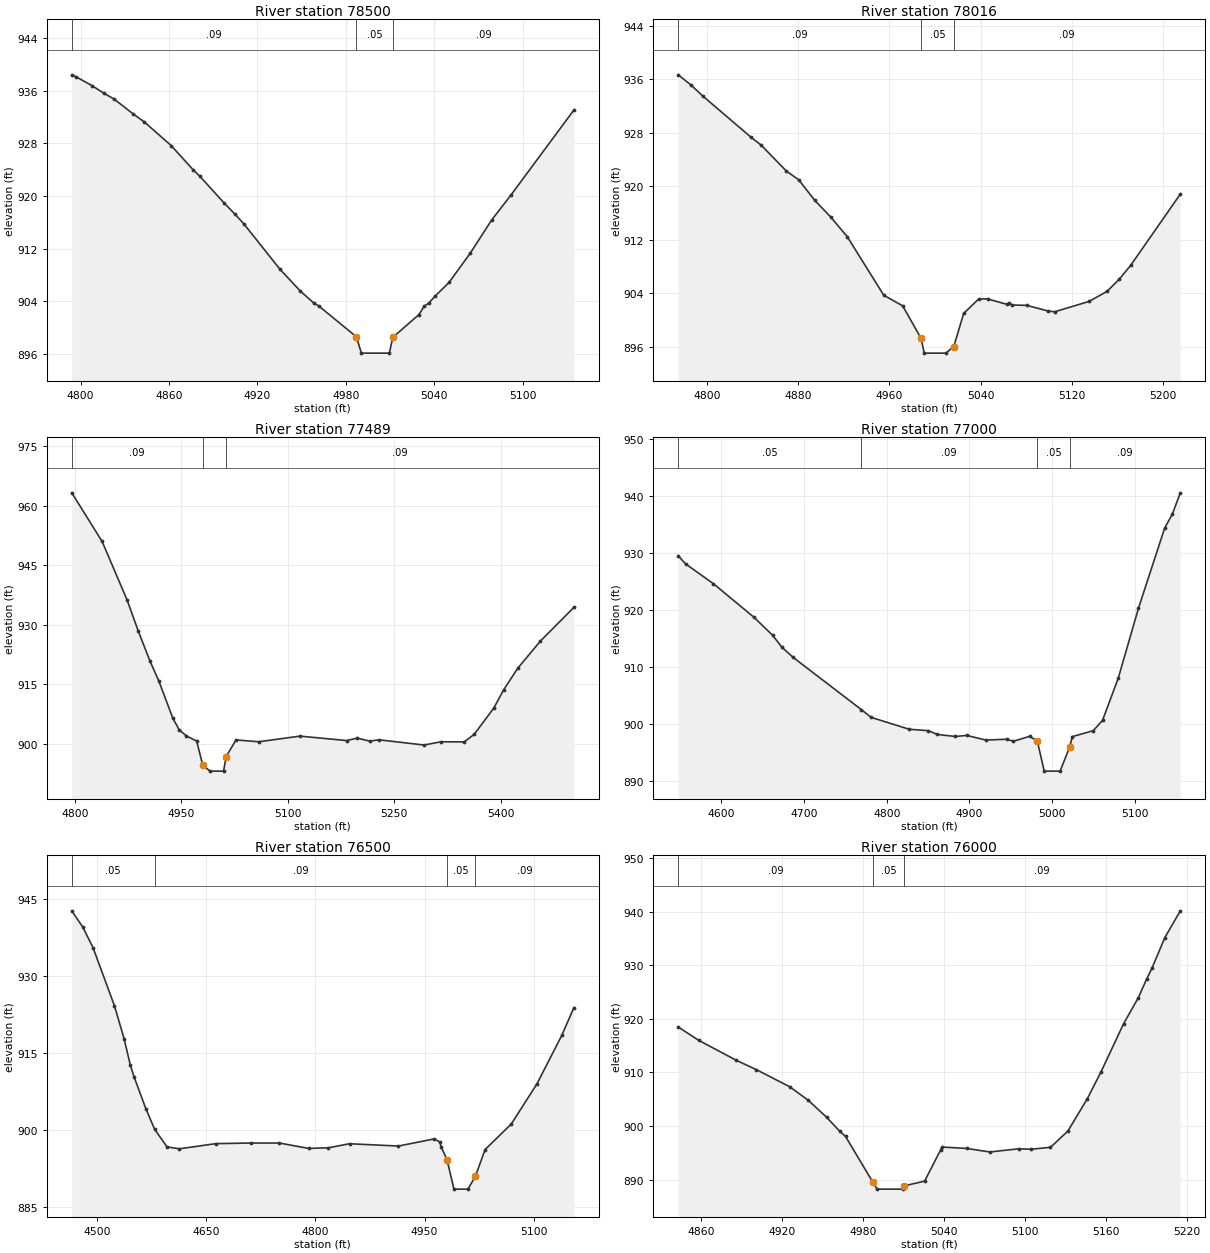
Type RM Length L Ch R = 1 ,78500   ,484,484,484
BEGIN DESCRIPTION:
Snow Creek 158.0
END DESCRIPTION:
XS GIS Cut Line= 3
      1655004.19      1004771.05      1655022.94      1004565.92
      1655019.41      1004431.24
#Sta/Elev= 30
    4794  938.39  4796.7  938.12  4807.8  936.74  4815.6  935.62  4822.7  934.71
  4835.6  932.46  4843.3  931.22  4861.4  927.65  4876.4  923.95    4881  922.96
  4897.6  918.86  4904.7  917.23  4910.9  915.71  4935.3  908.84  4949.1  905.54
  4958.3   903.7  4961.5  903.29 4987.14  898.59  4990.5  896.11  5009.5  896.11
 5011.77   898.5  5029.5  901.95  5033.2  903.26  5036.1  903.68  5040.5  904.76
    5050  906.85  5064.4   911.3  5078.8   916.3  5092.1  920.16  5134.7  933.05
#Mann= 3 ,-1 , 0
    4794     .09       0 4987.14     .05       0 5011.77     .09       0
Bank Sta=4987.14,5011.77
Exp/Cntr=0.3,0.1

Type RM Length L Ch R = 1 ,78016   ,527,527,527
BEGIN DESCRIPTION:
Snow Creek 157.0
END DESCRIPTION:
XS GIS Cut Line= 4
       1655605.2      1004722.87      1655513.91      1004573.25
      1655491.09      1004474.35      1655379.51      1004355.17
#Sta/Elev= 30
  4774.9  936.68  4785.9  935.19  4796.8  933.46  4838.8  927.33  4847.7  926.15
  4869.6   922.3  4880.6  920.96  4894.7  917.88  4908.6   915.4  4923.1  912.45
  4955.1  903.69  4971.6  902.12 4987.79  897.23  4990.5  895.04  5009.5  895.04
  5016.4  896.03  5025.1  900.99  5038.1  903.12    5046  903.15    5063  902.34
  5064.6  902.47  5067.8  902.24  5080.3  902.19  5099.1  901.34  5104.7  901.22
    5135  902.78  5150.7  904.28  5161.3  906.08  5171.4  908.17  5214.9  918.83
#Mann= 3 ,-1 , 0
  4774.9     .09       0 4987.79     .05       0  5016.4     .09       0
Bank Sta=4987.79,5016.4
Exp/Cntr=0.3,0.1

Type RM Length L Ch R = 1 ,77489   ,489,489,489
BEGIN DESCRIPTION:
Snow Creek 156.0
END DESCRIPTION:
XS GIS Cut Line= 4
      1656087.02      1004454.07      1655977.98      1004334.88
      1655899.37      1004289.23      1655453.05      1004200.48
#Sta/Elev= 30
  4795.6  963.24  4838.3     951  4873.5  936.26  4889.5  928.32  4905.7  920.88
  4918.3  915.81    4938  906.44    4947  903.52  4957.2  901.97  4971.6  900.68
  4980.2  894.55  4990.5  893.11  5009.5  893.11  5013.1  896.77    5027  900.97
    5059  900.51  5117.1  901.93  5183.1  900.81  5197.9  901.44  5215.6  900.66
  5228.1  901.01  5291.9  899.69  5316.2  900.51  5348.5  900.47  5362.6  902.37
  5390.4  909.05  5404.2  913.62  5424.1  919.06  5455.7  925.85  5503.1  934.38
#Mann= 3 ,-1 , 0
  4795.6     .09       0  4980.2     .05       0  5013.1     .09       0
Bank Sta=4980.2,5013.1
Exp/Cntr=0.3,0.1

Type RM Length L Ch R = 1 ,77000   ,500,500,500
BEGIN DESCRIPTION:
Snow Creek 155.0
END DESCRIPTION:
XS GIS Cut Line= 3
      1656173.24      1004035.64      1655743.04      1003895.96
      1655602.67      1003830.24
#Sta/Elev= 30
  4547.7  929.48  4556.6  928.06  4590.2  924.58  4639.6  918.65  4661.9  915.51
  4673.4  913.38  4686.9  911.62  4769.1  902.48    4781  901.11  4827.1  899.02
  4850.2  898.77    4861  898.11    4883  897.75  4896.7  897.94  4919.8  897.12
  4945.3  897.27    4953  896.91  4972.7  897.77    4982  896.98  4990.4  891.67
  5009.6  891.67  5021.3  895.93  5024.4  897.73  5049.6  898.76  5060.9  900.57
  5079.9  907.96  5104.4  920.26  5136.2  934.38  5145.3  936.75    5155  940.52
#Mann= 4 ,-1 , 0
  4547.7     .05       0  4769.1     .09       0    4982     .05       0
  5021.3     .09       0
Bank Sta=4982,5021.3
Exp/Cntr=0.3,0.1

Type RM Length L Ch R = 1 ,76500   ,500,500,500
BEGIN DESCRIPTION:
Snow Creek 154.0
END DESCRIPTION:
XS GIS Cut Line= 3
      1656300.04      1003886.03       1655954.6      1003477.84
      1655868.93      1003348.42
#Sta/Elev= 30
  4465.3  942.77  4480.5  939.58  4494.6  935.55    4524  924.21  4537.4   917.7
  4545.8  912.61  4551.1  910.28    4567  904.17    4579  900.16  4596.1  896.69
  4613.1  896.31  4663.3  897.32  4711.7  897.44  4750.5  897.44  4790.7  896.39
  4817.9  896.51  4846.9   897.3  4914.1  896.85  4963.5  898.25    4971  897.63
  4972.7  896.72  4980.8   894.2  4990.4  888.44  5009.6  888.44  5019.8  890.93
  5033.2  896.17  5069.1  901.14  5104.5  909.01  5138.5  918.44  5155.2  923.88
#Mann= 4 ,-1 , 0
  4465.3     .05       0    4579     .09       0  4980.8     .05       0
  5019.8     .09       0
Bank Sta=4980.8,5019.8
Exp/Cntr=0.3,0.1

Type RM Length L Ch R = 1 ,76000   ,500,500,500
BEGIN DESCRIPTION:
Snow Creek 153.0
END DESCRIPTION:
XS GIS Cut Line= 3
      1656480.09      1003612.15       1656391.6      1003482.49
      1656269.61      1003305.31
#Sta/Elev= 30
    4843  918.47  4858.3  915.96    4886  912.26  4900.9  910.51  4925.7  907.31
  4939.5  904.77  4953.1   901.6  4962.8  898.99    4967  898.05 4987.24  889.52
  4990.4  888.22  5009.6  888.22  5010.4  888.83  5025.6  889.71  5037.6  895.58
  5038.4  896.07  5056.8  895.81  5073.9  895.15  5095.2  895.74  5104.5  895.66
  5118.9  896.02  5131.8  899.05  5146.1  905.05  5156.4  910.12  5173.1  919.09
    5184  923.93  5190.2  927.44  5194.1  929.43  5203.6  935.12  5215.1  940.13
#Mann= 3 ,-1 , 0
    4843     .09       0 4987.24     .05       0  5010.4     .09       0
Bank Sta=4987.24,5010.4
Exp/Cntr=0.3,0.1

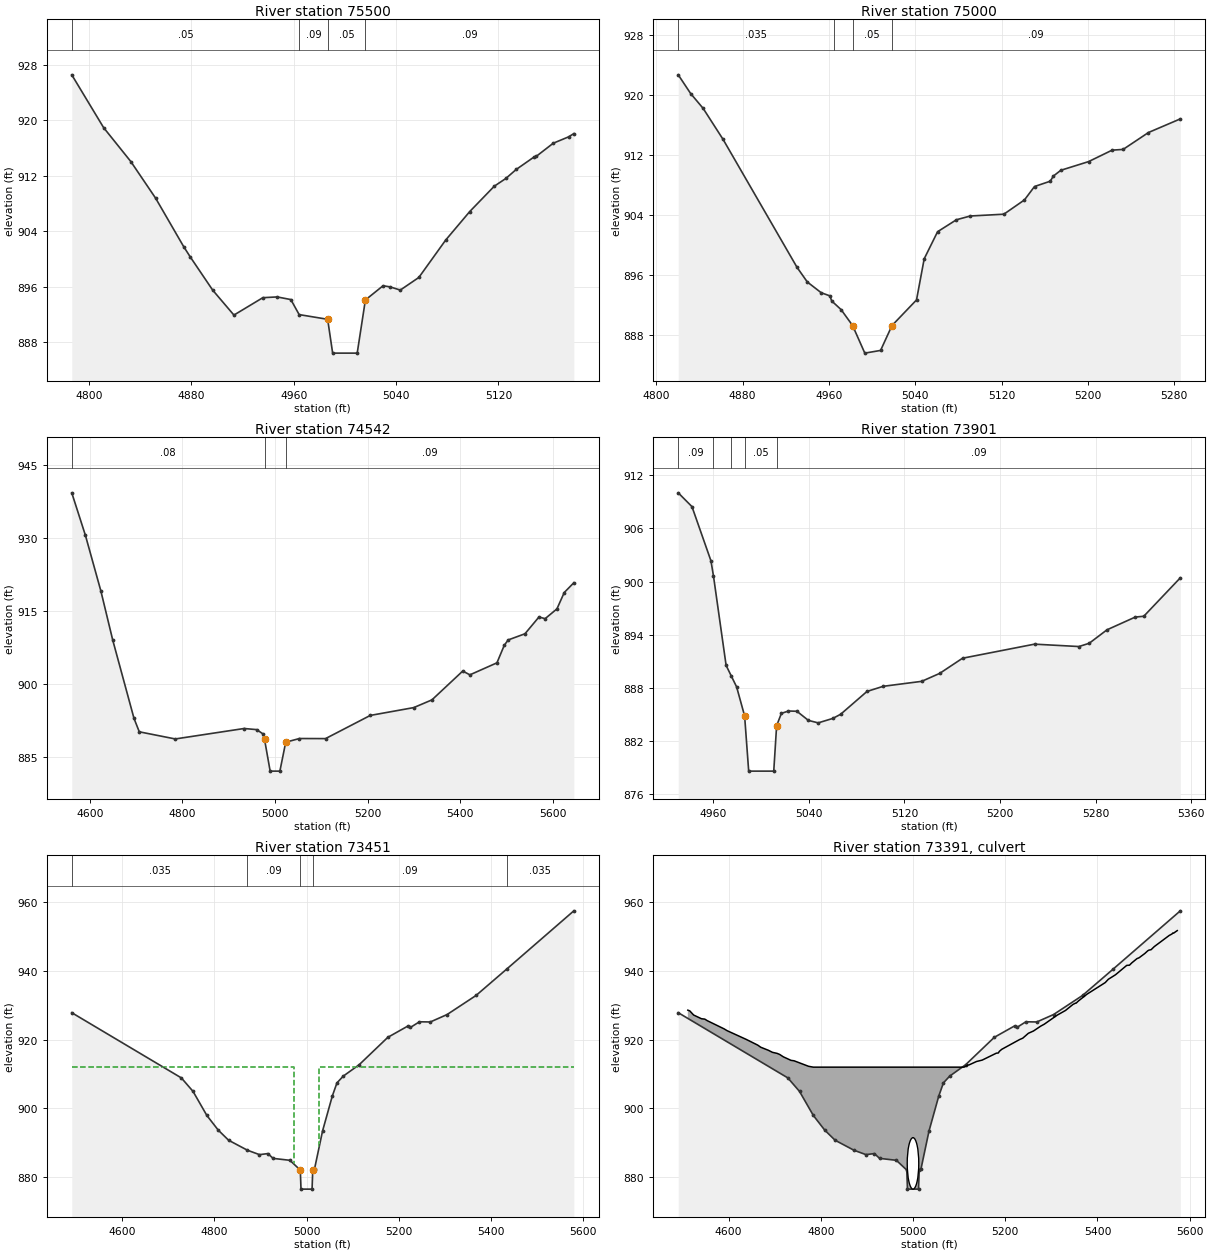
Type RM Length L Ch R = 1 ,75500   ,500,500,500
BEGIN DESCRIPTION:
Snow Creek 152.0
END DESCRIPTION:
XS GIS Cut Line= 4
      1656873.15      1003292.63      1656731.73       1003132.6
      1656713.39      1003102.43      1656578.99      1003051.72
#Sta/Elev= 30
  4786.4  926.59  4811.3  918.97  4832.6  914.07    4852  908.78  4873.9   901.8
  4879.1   900.3  4896.6  895.52  4913.2  891.92  4935.8  894.43    4947  894.54
  4957.7  894.16  4964.2  891.99 4986.49  891.31  4990.4  886.43  5009.6  886.43
    5016   894.1  5029.8  896.15  5035.3  895.99  5043.3  895.53  5057.8  897.35
  5078.8  902.75  5097.6  906.86  5116.8  910.52  5125.8  911.63  5133.9  912.93
  5148.1  914.76  5149.5  914.81  5162.9  916.72  5174.9  917.64    5179  918.11
#Mann= 4 ,-1 , 0
  4786.4     .05       0  4964.2     .09       0 4986.49     .05       0
    5016     .09       0
Bank Sta=4986.49,5016
Exp/Cntr=0.3,0.1

Type RM Length L Ch R = 1 ,75000   ,458,458,458
BEGIN DESCRIPTION:
Snow Creek 151.0
END DESCRIPTION:
XS GIS Cut Line= 4
      1657022.77       1003361.1      1657145.67      1003230.09
      1657185.06       1003170.9      1657096.31      1002975.64
#Sta/Elev= 30
  4820.4  922.74  4831.9  920.24  4843.5  918.25  4861.9  914.12  4930.5     897
    4940  895.05  4952.9  893.61    4961  893.19 4962.55  892.52 4971.34  891.35
 4981.95  889.23 4993.27  885.54 5007.88   885.9 5018.47  889.23 5041.18  892.65
  5048.3  898.15  5060.7  901.77  5078.2  903.37    5091  903.87  5122.1  904.11
  5141.2  906.02  5150.5  907.81  5165.1  908.52    5168  909.21  5174.9  909.98
  5200.6  911.14  5222.4  912.67  5232.6  912.77  5256.1  915.03  5285.6  916.85
#Mann= 4 ,-1 , 0
  4820.4    .035       0  4964.6     .09       0 4981.95     .05       0
 5018.47     .09       0
Bank Sta=4981.95,5018.47
Exp/Cntr=0.3,0.1

Type RM Length L Ch R = 1 ,74542   ,641,641,641
BEGIN DESCRIPTION:
Snow Creek 150.0
END DESCRIPTION:
XS GIS Cut Line= 5
      1657811.43      1003741.48      1657677.03      1003546.22
      1657535.02      1003437.17      1657218.03      1003203.87
      1657114.06      1002950.28
#Sta/Elev= 30
  4561.3  939.26  4590.8   930.5  4624.1  919.07  4649.7  908.97  4695.6  892.86
    4707  890.09  4784.7  888.62  4933.3  890.77  4960.4  890.54  4973.4   889.7
  4977.4  888.52  4989.5     882  5010.5     882  5023.1  887.95  5052.8  888.71
    5109  888.69  5205.6  893.46  5299.4  895.07  5338.7  896.66  5405.2  902.59
  5420.6  901.81    5479  904.28  5494.8  907.88  5503.2  908.99  5539.5  910.26
  5569.7  913.71    5583  913.37  5608.5  915.38  5624.3  918.75    5645  920.76
#Mann= 3 ,-1 , 0
  4561.3     .08       0  4977.4     .05       0  5023.1     .09       0
Bank Sta=4977.4,5023.1
Exp/Cntr=0.3,0.1

Type RM Length L Ch R = 1 ,73901   ,450,450,450
BEGIN DESCRIPTION:
Snow Creek 149.0
END DESCRIPTION:
XS GIS Cut Line= 5
      1657494.44      1002935.07      1657451.33      1002995.93
       1657385.4      1003145.54      1657329.61      1003168.37
      1657207.89      1003158.22
#Sta/Elev= 30
  4930.5  910.02    4942  908.46  4957.9  902.34    4960  900.64  4970.6  890.53
  4974.8  889.37  4979.4   888.1  4986.1  884.82  4989.5  878.59  5010.5  878.59
  5012.9  883.72  5016.9  885.11  5022.8  885.38  5029.9  885.35  5039.5  884.32
  5047.7  884.04  5059.9  884.54  5066.5  885.01  5088.6  887.59  5102.2  888.17
  5134.4  888.73  5149.5  889.63  5168.6  891.34  5228.9  892.93  5266.1  892.66
  5274.7  893.03  5289.6  894.55  5313.3  895.99  5320.4  896.08    5351  900.42
#Mann= 5 ,-1 , 0
  4930.5     .09       0    4960    .035       0  4974.8     .09       0
  4986.1     .05       0  5012.9     .09       0
Bank Sta=4986.1,5012.9
Exp/Cntr=0.5,0.3

Type RM Length L Ch R = 1 ,73451   ,146,146,146
BEGIN DESCRIPTION:
Sisk Rd. SR-1606 - US
END DESCRIPTION:
XS GIS Cut Line= 3
      1657723.03      1002791.82      1657258.61      1002737.27
      1656646.95      1002628.94
#Sta/Elev= 30
  4490.9  927.87  4728.6  908.86  4753.9  904.93  4783.8  897.93  4808.4  893.67
    4831   890.7  4871.8  887.79    4898   886.5  4916.2  886.81  4927.5  885.41
  4963.9  884.85  4986.5     882    4988  876.45    5012  876.45  5013.5     882
  5017.4  882.37  5034.8  893.42  5055.9  903.58    5066  907.41  5079.6  909.38
  5114.1   912.7  5176.3  920.69  5220.2  924.01  5225.3  923.57  5244.8  925.22
  5268.5  925.17  5304.8  927.33  5367.6  932.89  5433.9  940.56  5579.7  957.56
#Mann= 5 ,-1 , 0
  4490.9    .035       0  4871.8     .09       0  4986.5     .05       0
  5013.5     .09       0  5433.9    .035       0
#XS Ineff= 2 , 0
       0  4972.5     912  5027.5       0     912
Permanent Ineff=
       F       F
Bank Sta=4986.5,5013.5
Exp/Cntr=0.5,0.3

Type RM Length L Ch R = 2 ,73391   ,,,
BEGIN DESCRIPTION:
Sisk Rd. SR-1606
Structure ID: Sisk Rd. SR-1606
Approximate Survey Structure
END DESCRIPTION:
Bridge Culvert--1,0,-1,-1, 0
Deck Dist Width WeirC Skew NumUp NumDn MinLoCord MaxHiCord MaxSubmerge Is_Ogee
40,25,3,0, 60, 60, 912, , , 0, 1,1,,
  4511.7  4515.9  4524.3  4541.3  4548.5  4553.5  4590.2  4596.9    4638  4663.3
  4669.9  4686.3  4695.2  4705.4  4710.9  4718.8  4735.5    4742  4773.5  4783.9
  5110.7  5119.5  5121.7  5137.6    5150  5180.7  5185.3    5187  5192.4  5231.1
    5238  5250.2  5261.3    5277  5284.6  5312.6  5330.8  5346.9  5352.7  5353.7
  5358.4  5377.3  5416.9  5423.6  5439.2  5463.5  5469.4  5474.3  5485.7  5490.3
  5502.6  5509.1  5511.5  5516.4  5523.2  5555.7  5561.6  5563.5  5565.1  5573.1
  928.61   928.4  927.19  926.11     926  925.57  923.17  922.63  920.11  918.42
   917.8  916.92  916.32  916.01   915.7  915.01  913.98  913.86  912.25     912
     912  912.62  912.66  913.64  914.05  916.07  916.14  916.57  917.19  920.04
  920.44  921.87  922.54  923.96  924.51  927.15  928.53  930.28  930.67  930.64
  931.25  933.27  936.65  937.61  938.93  941.66  941.71  942.37  943.63  943.88
  945.11  945.91   946.1  946.24  947.13  950.39  950.81   951.1  951.05   951.8
  856.37  856.37  856.37  856.37  856.37  856.37  856.37  856.37  856.37  856.37
  856.37  856.37  856.37  856.37  856.37  856.37  856.37  856.37  856.37  856.37
  856.37  856.37  856.37  856.37  856.37  856.37  856.37  856.37  856.37  856.37
  856.37  856.37  856.37  856.37  856.37  856.37  856.37  856.37  856.37  856.37
  856.37  856.37  856.37  856.37  856.37  856.37  856.37  856.37  856.37  856.37
  856.37  856.37  856.37  856.37  856.37  856.37  856.37  856.37  856.37  856.37
  4511.7  4515.9  4524.3  4541.3  4548.5  4553.5  4590.2  4596.9    4638  4663.3
  4669.9  4686.3  4695.2  4705.4  4710.9  4718.8  4735.5    4742  4773.5  4783.9
  5110.7  5119.5  5121.7  5137.6    5150  5180.7  5185.3    5187  5192.4  5231.1
    5238  5250.2  5261.3    5277  5284.6  5312.6  5330.8  5346.9  5352.7  5353.7
  5358.4  5377.3  5416.9  5423.6  5439.2  5463.5  5469.4  5474.3  5485.7  5490.3
  5502.6  5509.1  5511.5  5516.4  5523.2  5555.7  5561.6  5563.5  5565.1  5573.1
  928.61   928.4  927.19  926.11     926  925.57  923.17  922.63  920.11  918.42
   917.8  916.92  916.32  916.01   915.7  915.01  913.98  913.86  912.25     912
     912  912.62  912.66  913.64  914.05  916.07  916.14  916.57  917.19  920.04
  920.44  921.87  922.54  923.96  924.51  927.15  928.53  930.28  930.67  930.64
  931.25  933.27  936.65  937.61  938.93  941.66  941.71  942.37  943.63  943.88
  945.11  945.91   946.1  946.24  947.13  950.39  950.81   951.1  951.05   951.8
   856.2   856.2   856.2   856.2   856.2   856.2   856.2   856.2   856.2   856.2
   856.2   856.2   856.2   856.2   856.2   856.2   856.2   856.2   856.2   856.2
   856.2   856.2   856.2   856.2   856.2   856.2   856.2   856.2   856.2   856.2
   856.2   856.2   856.2   856.2   856.2   856.2   856.2   856.2   856.2   856.2
   856.2   856.2   856.2   856.2   856.2   856.2   856.2   856.2   856.2   856.2
   856.2   856.2   856.2   856.2   856.2   856.2   856.2   856.2   856.2   856.2
Culvert=5,15,25,115,0.027,0.5,1,41,1,876.45,5000,875.88,5000,Culvert #1  , 0 ,2.5
Culvert Bottom n=0.027
BC Design=,, 0 ,, 0 ,,,,,,
BC HTab HWMax=957.56

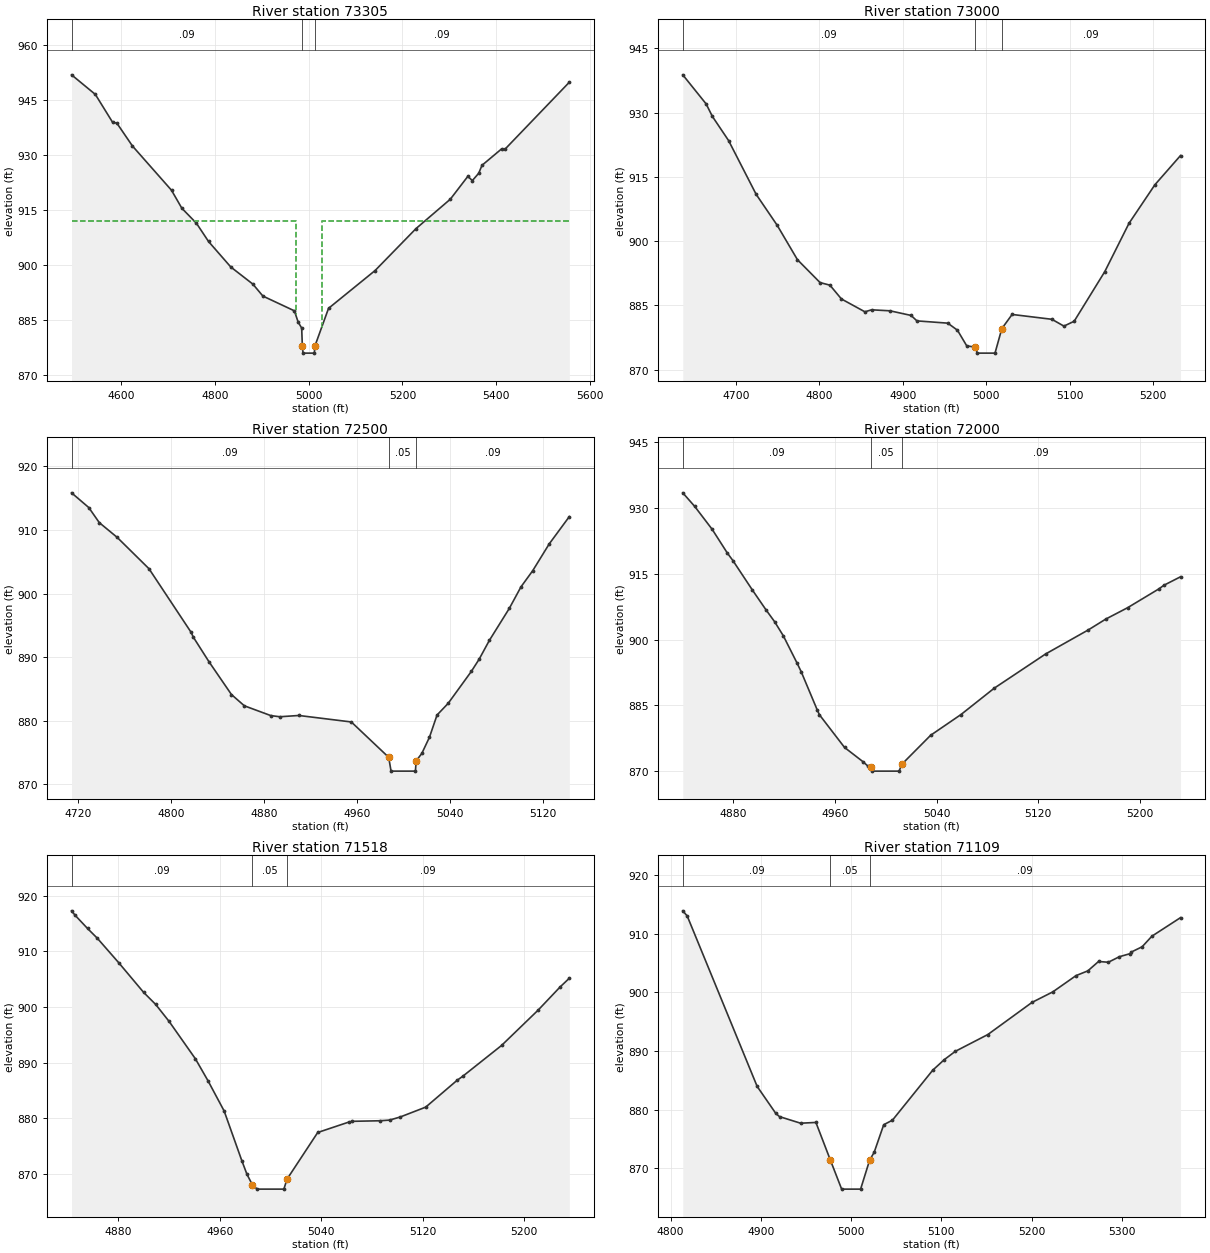
Type RM Length L Ch R = 1 ,73305   ,305,305,305
BEGIN DESCRIPTION:
Sisk Rd. SR-1606 - DS
END DESCRIPTION:
XS GIS Cut Line= 3
      1657753.11      1002689.08      1657271.29      1002595.25
       1656705.7       1002516.8
#Sta/Elev= 30
  4494.2  951.79    4545  946.44  4581.8  938.83  4590.8  938.62  4624.2  932.36
  4707.4  920.31  4729.4  915.41  4760.7  911.29  4786.4  906.33  4833.9  899.37
    4881   894.7  4902.4  891.44  4969.5  887.42  4977.6  884.33  4985.1  882.72
  4986.5  877.88    4988  875.88    5012  875.88  5013.5  877.88  5042.4   888.1
  5141.7  898.41  5228.9  909.84  5302.2  917.87  5339.5  924.09  5349.2  922.95
  5362.8  924.95  5369.7  927.11  5411.4  931.57  5418.7  931.49    5556  949.77
#Mann= 3 ,-1 , 0
  4494.2     .09       0  4986.5     .05       0  5013.5     .09       0
#XS Ineff= 2 , 0
       0  4972.5     912  5027.5       0     912
Permanent Ineff=
       F       F
Bank Sta=4986.5,5013.5
Exp/Cntr=0.5,0.3

Type RM Length L Ch R = 1 ,73000   ,500,500,500
BEGIN DESCRIPTION:
Snow Creek 147.0
END DESCRIPTION:
XS GIS Cut Line= 3
      1657671.96      1002476.07      1657344.25      1002318.05
      1657157.17      1002179.37
#Sta/Elev= 30
  4636.2  938.79  4664.2  932.01  4671.7  929.09  4691.1  923.47  4724.2  910.91
  4749.3  903.73  4773.7  895.67  4800.8  890.34  4812.6  889.74  4826.4  886.52
  4854.5  883.53  4862.6  883.99  4884.6  883.76  4909.9  882.68  4916.9  881.41
  4953.9  880.88  4965.5  879.23  4976.6  875.59    4986  875.31  4989.5  873.89
  5010.5  873.89  5018.7  879.61    5031  882.91  5078.7  881.78  5093.1  880.19
  5105.4  881.32  5142.1   892.9  5171.1  904.15  5202.2  913.16  5232.9  919.97
#Mann= 3 ,-1 , 0
  4636.2     .09       0    4986     .05       0  5018.7     .09       0
Bank Sta=4986,5018.7
Exp/Cntr=0.3,0.1

Type RM Length L Ch R = 1 ,72500   ,500,500,500
BEGIN DESCRIPTION:
Snow Creek 146.0
END DESCRIPTION:
XS GIS Cut Line= 3
      1657854.54      1002095.68      1657628.63       1001920.9
      1657514.73      1001834.49
#Sta/Elev= 30
  4714.4  915.84  4729.2  913.53  4738.3  911.15  4753.6  908.85  4781.1   903.9
  4817.4  893.89  4819.2  893.16  4832.7  889.29  4852.1  884.12  4863.2  882.35
    4886  880.81  4893.8  880.63  4910.1  880.83  4955.3  879.81 4987.49  874.25
  4989.5  872.08  5010.5  872.08  5011.1  873.69    5016  874.86  5022.6  877.42
  5029.1   880.9  5038.7  882.74  5058.6  887.75  5065.4  889.69  5074.1  892.62
  5091.3  897.66  5101.4  901.06  5111.5   903.6  5125.7  907.81    5143   912.1
#Mann= 3 ,-1 , 0
  4714.4     .09       0 4987.49     .05       0  5011.1     .09       0
Bank Sta=4987.49,5011.1
Exp/Cntr=0.3,0.1

Type RM Length L Ch R = 1 ,72000   ,482,482,482
BEGIN DESCRIPTION:
Snow Creek 145.0
END DESCRIPTION:
XS GIS Cut Line= 3
       1657978.8      1001487.07      1657823.63      1001525.75
      1657600.95      1001591.04
#Sta/Elev= 30
  4840.1  933.47  4849.4  930.41  4863.3  925.13  4875.2  919.74  4879.6  918.02
    4895  911.28  4905.8  906.73  4912.4   904.1  4919.3  900.87  4930.1  894.66
  4933.3  892.73    4946  883.97  4947.7  882.88  4967.5  875.42  4981.9   872.2
  4985.6  871.25  4988.1     871  4989.5  870.02  5010.5  870.02 5012.51  871.55
  5035.3  878.19  5059.2  882.92  5085.4  888.93  5125.9  896.74  5159.5  902.22
  5173.2  904.68  5190.5  907.29    5215  911.56  5219.1  912.41  5232.1  914.33
#Mann= 3 ,-1 , 0
  4840.1     .09       0  4988.1     .05       0 5012.51     .09       0
Bank Sta=4988.1,5012.51
Exp/Cntr=0.3,0.1

Type RM Length L Ch R = 1 ,71518   ,409,409,409
BEGIN DESCRIPTION:
Snow Creek 144.0
END DESCRIPTION:
XS GIS Cut Line= 3
       1657915.4      1001035.68      1657758.18      1001055.97
      1657542.63      1001147.26
#Sta/Elev= 30
    4843  917.31  4845.9  916.49  4855.6  914.14  4863.3  912.39  4880.3  907.96
  4899.9  902.64  4909.3   900.5    4920  897.42  4940.7  890.71  4950.6  886.78
  4963.4  881.32  4977.4  872.35  4981.4  869.94  4985.7  868.04  4989.5  867.28
  5010.5  867.28 5013.01  869.08  5037.2  877.46  5061.7  879.33  5064.5  879.47
  5086.3  879.57  5093.9  879.69  5102.3  880.25  5122.4  882.02  5147.1  886.83
  5151.8   887.6  5182.2   893.1  5211.1  899.46  5228.5  903.64  5235.7  905.19
#Mann= 3 ,-1 , 0
    4843     .09       0  4985.7     .05       0 5013.01     .09       0
Bank Sta=4985.7,5013.01
Exp/Cntr=0.3,0.1

Type RM Length L Ch R = 1 ,71109   ,609,609,609
BEGIN DESCRIPTION:
Snow Creek 143.0
END DESCRIPTION:
XS GIS Cut Line= 5
      1657659.64      1000612.89      1657546.98      1000705.07
      1657489.62      1000756.28      1657456.85      1000813.64
      1657438.41      1001075.83
#Sta/Elev= 30
  4813.5  913.88  4818.4  913.01  4895.9  883.97  4916.6  879.36  4920.7  878.82
    4944   877.7    4961  877.83  4977.1  871.38  4989.5  866.47  5010.5  866.47
  5020.5   871.4  5025.6  872.77  5036.1  877.44  5045.8  878.22  5090.4  886.73
  5103.3  888.54  5115.5  889.95  5151.4   892.8  5200.4  898.28  5223.4  900.07
  5249.1  902.84  5262.2  903.65  5274.1  905.25  5284.9  905.12  5297.1  906.06
  5309.4   906.6  5310.4  906.86  5322.4  907.76  5333.2  909.56  5364.9  912.72
#Mann= 3 ,-1 , 0
  4813.5     .09       0  4977.1     .05       0  5020.5     .09       0
Bank Sta=4977.1,5020.5
Exp/Cntr=0.3,0.1

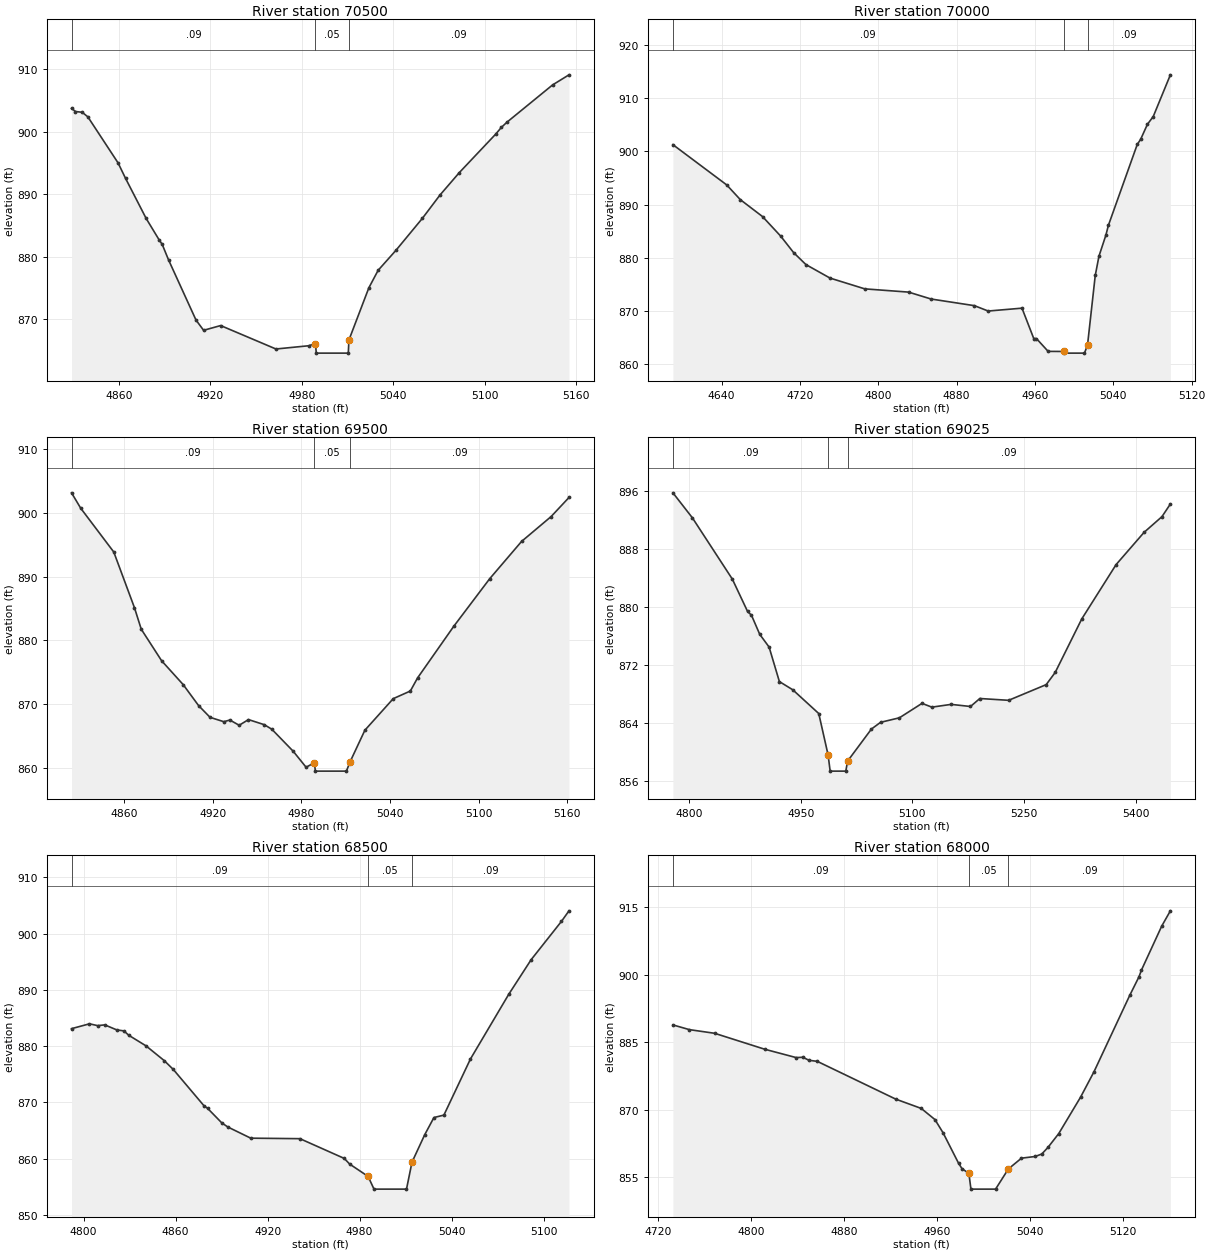
Type RM Length L Ch R = 1 ,70500   ,500,500,500
BEGIN DESCRIPTION:
Snow Creek 142.0
END DESCRIPTION:
XS GIS Cut Line= 3
      1657136.88       1000860.7      1657265.09      1000974.22
      1657375.26      1001083.86
#Sta/Elev= 30
  4828.8  903.78  4831.4  903.27  4835.8  903.15  4839.5  902.42  4859.3  895.07
  4864.3  892.56  4877.8  886.16  4886.4   882.7  4888.3  882.03  4892.5  879.53
  4910.5  869.92  4915.5  868.27  4926.7  869.03    4963  865.28  4984.5   865.8
  4988.9  866.15  4989.5  864.62  5010.5  864.62 5010.92  866.72    5024  875.07
  5030.1  877.87  5041.7  881.04  5059.1  886.17  5070.7  889.91  5083.4   893.5
  5107.3  899.66    5111  900.73  5114.7  901.57  5144.6  907.52  5155.4  909.14
#Mann= 3 ,-1 , 0
  4828.8     .09       0  4988.9     .05       0 5010.92     .09       0
Bank Sta=4988.9,5010.92
Exp/Cntr=0.3,0.1

Type RM Length L Ch R = 1 ,70000   ,500,500,500
BEGIN DESCRIPTION:
Snow Creek 141.0
END DESCRIPTION:
XS GIS Cut Line= 4
      1657040.52      1000880.99      1656936.55      1001175.15
      1656926.76      1001272.37      1656888.36      1001362.81
#Sta/Elev= 30
  4590.3  901.28  4645.2  893.71  4659.1  890.94  4681.8  887.75  4700.3  884.08
  4713.5  880.98  4726.1  878.72  4750.7  876.18  4786.2  874.15  4830.9  873.54
  4853.9  872.24  4898.1  870.99  4912.2  869.98  4946.7  870.52  4958.7  864.81
  4961.5  864.79  4973.4  862.39  4989.2  862.37  4989.5  862.06  5010.5  862.06
  5013.6  863.57  5021.5  876.67  5025.3  880.31  5032.4  884.28  5034.9  886.09
  5064.4  901.33  5067.8  902.27  5074.8  905.12  5080.7  906.57  5098.2  914.42
#Mann= 3 ,-1 , 0
  4590.3     .09       0  4989.2     .05       0  5013.6     .09       0
Bank Sta=4989.2,5013.6
Exp/Cntr=0.3,0.1

Type RM Length L Ch R = 1 ,69500   ,475,475,475
BEGIN DESCRIPTION:
Snow Creek 140.0
END DESCRIPTION:
XS GIS Cut Line= 3
      1656649.99      1000746.59      1656586.98      1000910.51
       1656523.2       1001058.5
#Sta/Elev= 30
  4824.4  903.13  4830.6  900.72    4853  893.85    4867  885.12  4871.6  881.75
  4885.4   876.8    4900  873.06  4910.4  869.78  4918.2  867.93  4927.5  867.25
  4931.6  867.51  4937.9  866.69  4944.2  867.58  4954.9  866.78    4960  866.07
  4974.5  862.61  4983.2  860.11  4988.8  860.81  4989.5   859.5  5010.5   859.5
 5012.91  860.92    5023  865.91  5042.2  870.86  5053.8  872.06  5058.7  874.12
  5083.2  882.21  5107.5  889.66  5129.1  895.51  5149.1  899.41  5161.2   902.4
#Mann= 3 ,-1 , 0
  4824.4     .09       0  4988.8     .05       0 5012.91     .09       0
Bank Sta=4988.8,5012.91
Exp/Cntr=0.3,0.1

Type RM Length L Ch R = 1 ,69025   ,525,525,525
BEGIN DESCRIPTION:
Snow Creek 139.0
END DESCRIPTION:
XS GIS Cut Line= 4
       1656325.4      1000460.03      1656244.25      1000569.07
      1656193.53      1000647.69      1656201.14       1001086.4
#Sta/Elev= 30
  4778.3  895.73  4804.5  892.28  4858.1  883.85  4878.6  879.39  4883.8  878.88
  4894.9  876.25  4907.5  874.49  4921.3  869.74  4939.3  868.61  4974.2  865.34
 4986.79  859.61  4989.5  857.41  5010.5  857.41    5013   858.8  5044.9   863.2
  5057.2  864.13  5082.5  864.75  5112.9  866.74  5126.1  866.22    5152   866.6
    5178  866.31  5190.6  867.41  5229.2  867.16  5279.7  869.32  5291.8     871
  5327.5  878.37  5373.6  885.85  5411.2  890.29  5435.2  892.45  5446.5  894.19
#Mann= 3 ,-1 , 0
  4778.3     .09       0 4986.79     .05       0    5013     .09       0
Bank Sta=4986.79,5013
Exp/Cntr=0.3,0.1

Type RM Length L Ch R = 1 ,68500   ,500,500,500
BEGIN DESCRIPTION:
Snow Creek 138.0
END DESCRIPTION:
XS GIS Cut Line= 4
      1656051.52      1000475.25      1655945.01      1000520.89
      1655853.27      1000513.76      1655737.07      1000523.43
#Sta/Elev= 30
  4792.1  883.11  4803.8  883.97  4809.1  883.65  4813.8  883.78  4821.6  882.89
  4826.3  882.71  4829.4  881.94  4840.7  880.05  4852.6  877.42  4858.5  875.85
  4878.4  869.43  4880.9  868.93  4890.1  866.36  4894.1  865.62    4909  863.64
  4941.1  863.55    4970  860.04  4973.5  859.04 4985.55  856.84  4989.4  854.58
  5010.6  854.58  5014.2  859.38  5022.5  864.26  5028.5  867.31    5035  867.74
  5052.3  877.71  5077.3  889.22  5091.9  895.37  5111.7  902.19  5116.6  904.06
#Mann= 3 ,-1 , 0
  4792.1     .09       0 4985.55     .05       0  5014.2     .09       0
Bank Sta=4985.55,5014.2
Exp/Cntr=0.3,0.1

Type RM Length L Ch R = 1 ,68000   ,500,500,500
BEGIN DESCRIPTION:
Snow Creek 137.0
END DESCRIPTION:
XS GIS Cut Line= 3
      1656241.71      1000064.43      1655976.16      1000035.18
      1655815.68      1000021.32
#Sta/Elev= 30
  4732.8  888.89    4747  887.84  4768.7  887.03  4811.9  883.48  4838.9  881.63
  4844.7   881.7  4849.9  881.03  4857.1  880.79  4924.7  872.39  4946.6  870.33
  4958.4  867.85  4965.4  864.91  4978.8  858.11  4981.7  856.94  4987.6  855.89
  4989.4  852.39  5010.6  852.39  5021.6  856.87  5032.9  859.27  5044.8  859.65
  5050.4   860.2  5055.7  861.66    5065  864.74  5083.8  872.84  5095.4  878.51
  5126.1  895.45  5134.1   899.6  5136.2  901.08  5153.7  910.88  5161.1  914.25
#Mann= 3 ,-1 , 0
  4732.8     .09       0  4987.6     .05       0  5021.6     .09       0
Bank Sta=4987.6,5021.6
Exp/Cntr=0.3,0.1