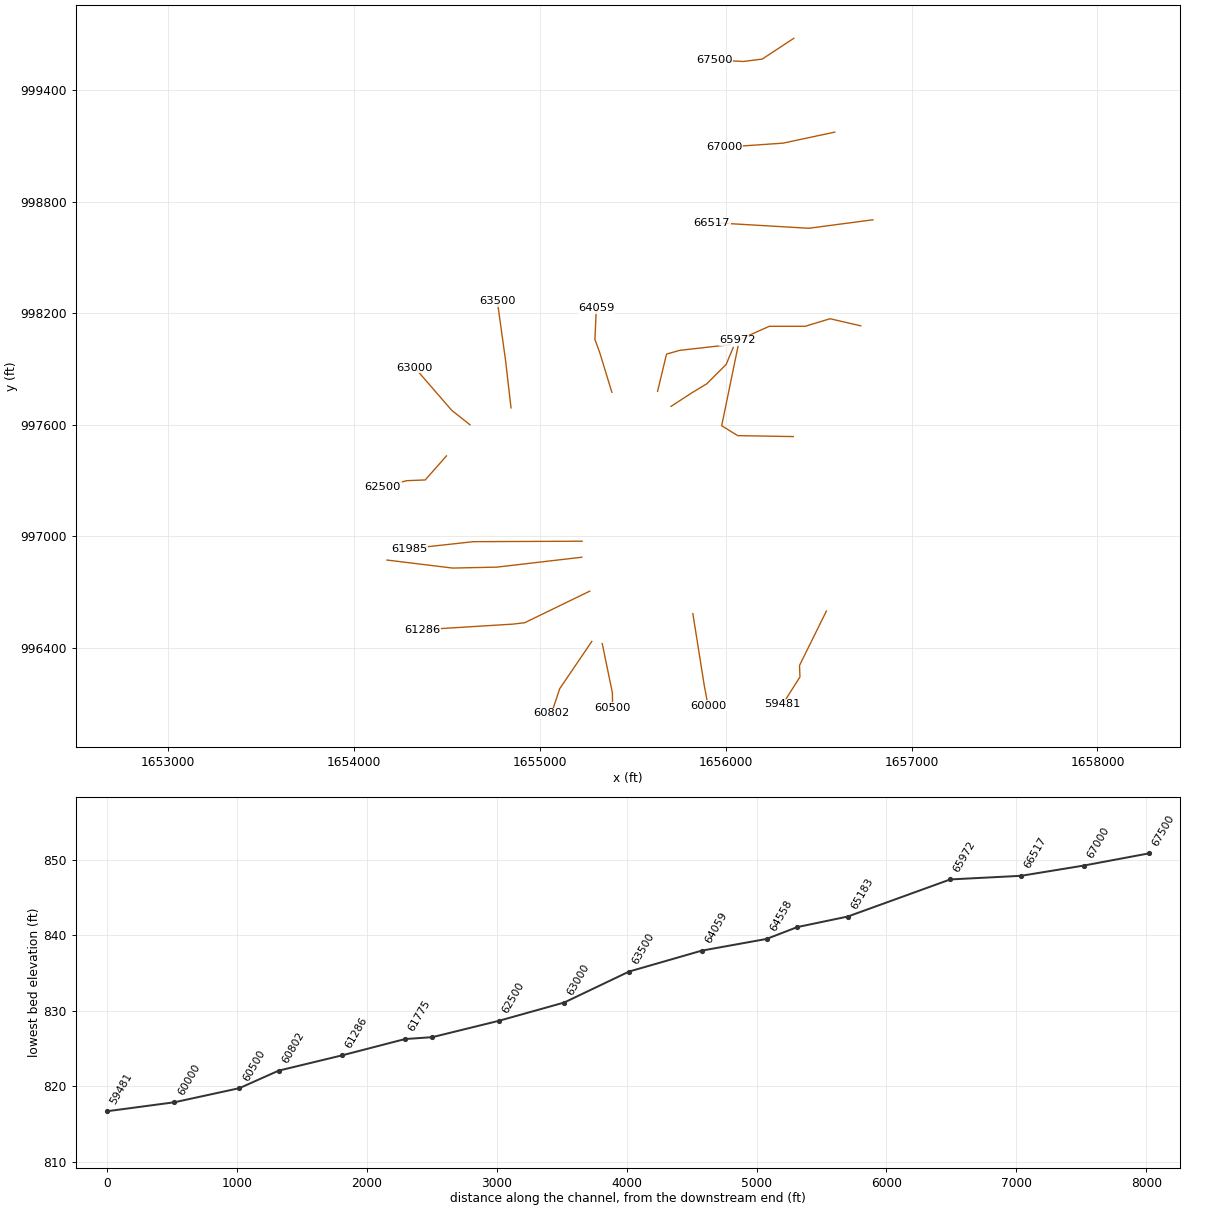
HEC-RAS study lds_snow_crk.prj: Snow Creek Limited Detail Study

--- lds_snow_crk.g02 (geometry) --- (continued)

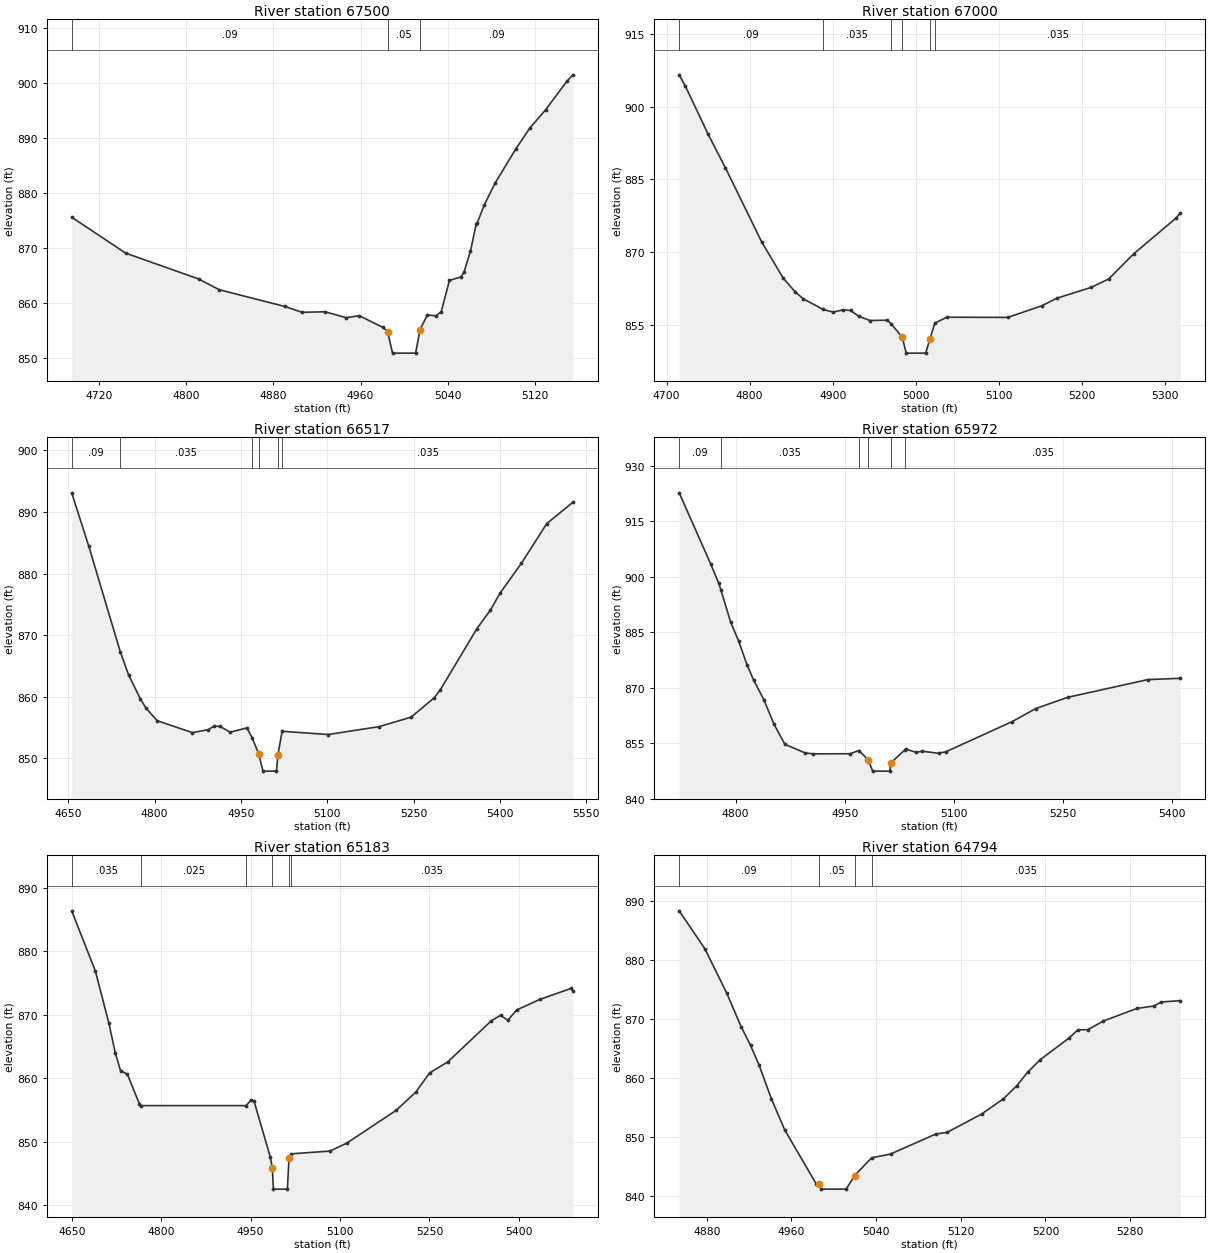
Type RM Length L Ch R = 1 ,67500   ,500,500,500
BEGIN DESCRIPTION:
Snow Creek 136.0
END DESCRIPTION:
XS GIS Cut Line= 4
      1656365.97       999678.97      1656196.07       999567.39
      1656094.89        999554.5      1655939.94       999562.32
#Sta/Elev= 30
  4694.7  875.58  4744.2  869.06  4811.2  864.36  4830.2   862.4  4890.5  859.35
  4906.4  858.29  4927.4  858.39  4946.9  857.31  4958.8  857.68  4980.6  855.54
  4984.9  854.79  4989.4  850.87  5010.6  850.87  5014.7  855.16  5021.5  857.83
  5029.1  857.64  5034.1  858.37  5041.7  864.08  5052.4  864.74  5055.1  865.63
    5061  869.41  5066.4  874.43  5067.4  874.62  5073.5  877.73  5083.5  881.74
  5102.7  888.01  5115.5  891.78  5130.2  895.15  5149.8  900.36  5155.1  901.47
#Mann= 3 ,-1 , 0
  4694.7     .09       0  4984.9     .05       0  5014.7     .09       0
Bank Sta=4984.9,5014.7
Exp/Cntr=0.3,0.1

Type RM Length L Ch R = 1 ,67000   ,483,483,483
BEGIN DESCRIPTION:
Snow Creek 135.0
END DESCRIPTION:
XS GIS Cut Line= 3
      1656586.59       999174.33      1656308.01       999114.97
      1655990.66       999093.18
#Sta/Elev= 30
  4715.2  906.52  4722.7  904.17  4750.1  894.27  4770.7  887.43  4814.5  872.12
  4840.3   864.7  4854.5  861.91  4864.6  860.41  4888.5  858.25  4900.3   857.7
  4912.3  858.16  4921.3  858.04  4931.1  856.86  4944.7  855.97  4965.7  856.04
  4970.4  855.26 4983.61   852.5  4988.3  849.26  5011.7  849.26  5016.7  852.07
  5022.7  855.44  5037.2  856.65  5110.4  856.61  5151.6  859.01  5169.4  860.55
  5210.5  862.77  5231.9  864.52  5261.9  869.68  5312.7  877.01  5318.1   878.1
#Mann= 6 ,-1 , 0
  4715.2     .09       0  4888.5    .035       0  4970.4     .08       0
 4983.61    .045       0  5016.7     .08       0  5022.7    .035       0
Bank Sta=4983.61,5016.7
Exp/Cntr=0.3,0.1

Type RM Length L Ch R = 1 ,66517   ,545,545,545
BEGIN DESCRIPTION:
Snow Creek 134.0
END DESCRIPTION:
XS GIS Cut Line= 3
        1656792.       998702.65      1656447.12       998657.01
      1655924.72       998687.44
#Sta/Elev= 30
  4655.8  893.11  4685.4  884.45  4740.1  867.33  4754.6  863.54  4775.3   859.6
  4785.2  858.11  4804.2   856.1  4865.6  854.15    4893  854.64  4903.2  855.21
  4913.6  855.16  4931.1  854.23  4960.4  854.92  4969.4  853.31  4980.7  850.75
  4988.3   847.9  5011.7   847.9  5014.1  850.51  5021.5  854.37  5101.8  853.85
  5190.2  855.13  5245.7  856.67  5285.7   859.8  5296.2  861.07  5359.6  870.98
  5383.4  874.05  5400.6  876.85  5437.2  881.64  5481.5  888.11  5526.9  891.58
#Mann= 6 ,-1 , 0
  4655.8     .09       0  4740.1    .035       0  4969.4     .06       0
  4980.7    .045       0  5014.1     .06       0  5021.5    .035       0
Bank Sta=4980.7,5014.1
Exp/Cntr=0.3,0.1

Type RM Length L Ch R = 1 ,65972   ,789,789,789
BEGIN DESCRIPTION:
Snow Creek 133.0
END DESCRIPTION:
XS GIS Cut Line= 5
      1656726.07       998132.08      1656561.23       998170.11
      1656426.83       998129.54       1656234.1       998129.54
       1656064.2       998053.46
#Sta/Elev= 30
  4722.5  922.62  4765.8  903.39  4776.9  898.14  4779.8  896.36  4793.3  887.61
  4804.2  882.56  4815.9  876.04  4824.6  872.08  4838.9  866.68  4852.8  860.07
  4867.7  854.67  4895.5  852.34  4906.8  852.09  4957.2  852.12  4969.1  852.99
 4982.03  850.54  4988.3  847.42  5011.7  847.42  5013.4   849.7  5032.1  853.09
    5034  853.34  5048.3  852.49  5056.1   852.8  5078.7  852.25  5088.6  852.64
    5180  860.81  5212.1  864.31  5255.9  867.35  5366.1  872.15  5410.9  872.51
#Mann= 6 ,-1 , 0
  4722.5     .09       0  4779.8    .035       0  4969.1     .06       0
 4982.03    .045       0  5013.4     .06       0  5032.1    .035       0
Bank Sta=4982.03,5013.4
Exp/Cntr=0.3,0.1

Type RM Length L Ch R = 1 ,65183   ,389,389,389
BEGIN DESCRIPTION:
Snow Creek 131.0
END DESCRIPTION:
XS GIS Cut Line= 4
      1656363.43       997536.14       1656064.2       997541.21
      1655977.98       997594.47      1656066.73       998025.57
#Sta/Elev= 30
  4649.9  886.38  4689.7  876.85    4712  868.75  4723.2   863.9  4731.8  861.17
  4743.3  860.62  4763.5  855.91  4766.7  855.67  4942.6  855.67  4951.1   856.6
  4955.8  856.36    4983  847.58  4986.5   845.8  4988.3   842.5  5011.7   842.5
  5014.4  847.34  5018.6  848.07  5083.1   848.5  5111.3  849.75  5194.3  854.93
  5227.3  857.82  5250.2  860.81  5281.4  862.61  5353.8  869.04  5369.3   869.9
  5381.6  869.14  5396.3  870.74  5434.8   872.4  5487.8  874.15  5490.7  873.76
#Mann= 6 ,-1 , 0
  4649.9    .035       0  4766.7    .025       0  4942.6     .05       0
  4986.5     .04       0  5014.4     .05       0  5018.6    .035       0
Bank Sta=4986.5,5014.4
Exp/Cntr=0.3,0.1

Type RM Length L Ch R = 1 ,64794   ,236,236,236
BEGIN DESCRIPTION:
Snow Creek 130.5
END DESCRIPTION:
XS GIS Cut Line= 5
      1655705.57       997698.76      1655814.53       997769.71
      1655898.15       997820.39      1656002.04       997924.28
      1656040.05        998015.5
#Sta/Elev= 30
  4853.9  888.41  4878.1  881.98  4898.9   874.4  4912.4  868.72  4921.3  865.55
  4929.4  862.18    4941  856.47  4953.6  851.18  4983.4  841.99  4986.3   841.9
  4988.3   841.1  5011.7   841.1  5019.7  843.41  5035.7  846.42  5053.6  847.07
  5096.2  850.45  5107.2  850.76    5140   853.9  5160.3  856.46  5172.7  858.64
  5183.1  860.96  5195.1  863.11  5222.1  866.76  5230.7  868.19    5240   868.2
  5254.8  869.68  5286.2  871.81  5302.5  872.23  5309.3  872.91  5327.5  873.15
#Mann= 4 ,-1 , 0
  4853.9     .09       0  4986.3     .05       0  5019.7     .09       0
  5035.7    .035       0
Bank Sta=4986.3,5019.7
Exp/Cntr=0.3,0.1

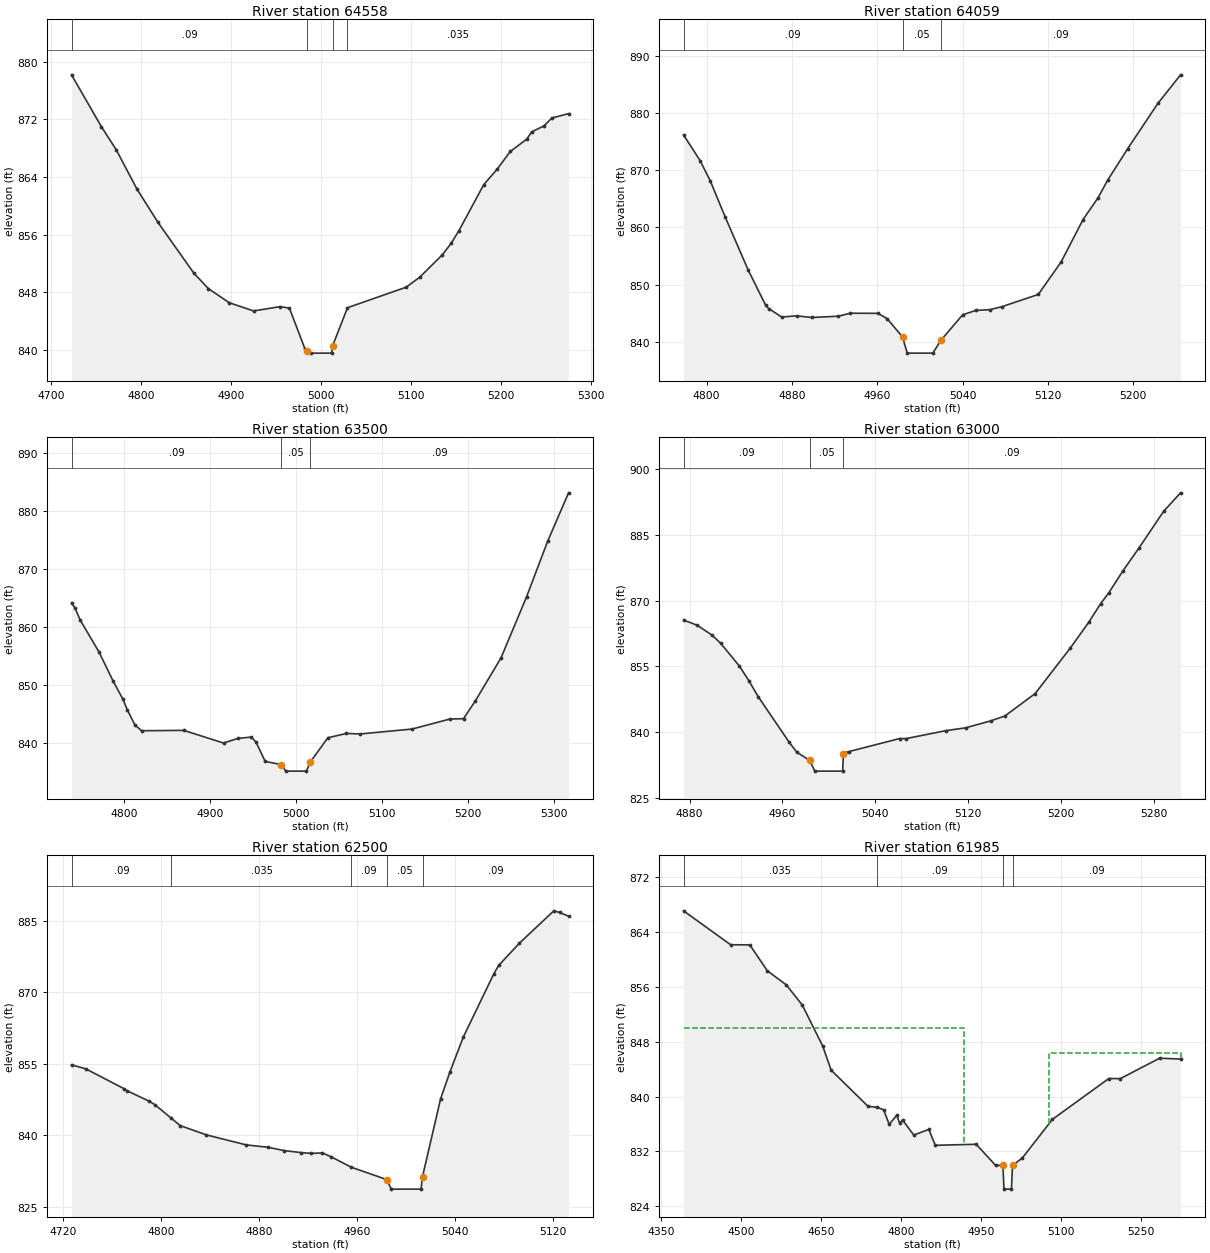
Type RM Length L Ch R = 1 ,64558   ,499,499,499
BEGIN DESCRIPTION:
Snow Creek 130.0
END DESCRIPTION:
XS GIS Cut Line= 4
       1655633.1       997779.59      1655681.28       997979.92
      1655752.28       998000.21      1656023.62       998030.64
#Sta/Elev= 30
  4722.4  878.19  4755.6  870.99  4772.1  867.79  4795.2  862.32  4818.6  857.69
  4858.6  850.62  4874.7  848.49  4897.9  846.53  4924.9  845.39  4954.4  845.99
  4964.8  845.78  4982.2  840.07  4984.8  839.77  4988.3  839.53  5011.7  839.53
 5012.81  840.54  5029.4  845.84  5094.7  848.69  5109.6  850.06  5134.8  853.17
  5144.7  854.78  5153.4  856.55  5180.9  862.92  5195.8  865.07  5210.5  867.54
  5228.8  869.25  5234.2  870.26    5248   871.1  5256.7  872.19  5275.3   872.8
#Mann= 4 ,-1 , 0
  4722.4     .09       0  4984.8     .05       0 5012.81     .09       0
  5029.4    .035       0
Bank Sta=4984.8,5012.81
Exp/Cntr=0.3,0.1

Type RM Length L Ch R = 1 ,64059   ,559,559,559
BEGIN DESCRIPTION:
Snow Creek 129.0
END DESCRIPTION:
XS GIS Cut Line= 4
      1655387.11       997774.51      1655321.18       997990.07
      1655295.82       998058.54      1655303.43        998225.9
#Sta/Elev= 30
  4778.3  876.21  4793.8  871.72  4803.4  868.15  4817.2   861.9  4838.8  852.59
  4855.2   846.4  4858.1  845.79  4870.3  844.31  4884.4  844.51  4898.4  844.23
    4923  844.44  4934.7  844.97  4960.5  844.95  4969.2  844.02 4983.61  840.82
    4988  837.98    5012  837.98 5019.96  840.31    5040   844.7  5052.5  845.47
  5065.2  845.58  5076.8  846.12  5110.9  848.26  5132.2  853.92  5152.9  861.39
  5166.9  865.19  5175.8  868.23  5194.6  873.77  5223.1  881.75  5244.3  886.74
#Mann= 3 ,-1 , 0
  4778.3     .09       0 4983.61     .05       0 5019.96     .09       0
Bank Sta=4983.61,5019.96
Exp/Cntr=0.3,0.1

Type RM Length L Ch R = 1 ,63500   ,500,500,500
BEGIN DESCRIPTION:
Snow Creek 128.0
END DESCRIPTION:
XS GIS Cut Line= 3
      1654844.43       997690.83      1654814.56       997950.25
      1654770.89       998263.94
#Sta/Elev= 30
  4738.9  864.21  4743.1  863.28  4748.9  861.25  4770.8  855.75  4787.4  850.69
  4798.7  847.59  4803.8  845.74  4812.6  843.18  4820.3  842.17  4869.3  842.23
  4915.6  840.05  4932.2  840.84    4948  841.08  4953.6  840.16    4964  836.89
 4982.92  836.33    4988  835.21    5012  835.21 5016.29  836.73  5036.9  840.96
  5058.5   841.7  5074.2  841.61  5134.9  842.46  5178.9  844.19  5194.6  844.24
  5208.4  847.32  5238.2  854.72  5267.9  865.24  5292.4   874.8  5316.7  883.15
#Mann= 3 ,-1 , 0
  4738.9     .09       0 4982.92     .05       0 5016.29     .09       0
Bank Sta=4982.92,5016.29
Exp/Cntr=0.3,0.1

Type RM Length L Ch R = 1 ,63000   ,500,500,500
BEGIN DESCRIPTION:
Snow Creek 127.0
END DESCRIPTION:
XS GIS Cut Line= 3
      1654623.81       997599.54       1654525.6       997677.11
      1654327.11       997906.38
#Sta/Elev= 30
  4874.8  865.56  4886.5  864.38  4899.3  862.14  4906.9  860.24  4922.9  855.09
    4931  851.77  4939.3  848.04    4966  837.64  4972.5   835.4 4983.52  833.57
    4988   831.1    5012   831.1  5012.6  834.94  5014.4  835.32  5017.4  835.56
  5061.1  838.53  5066.5  838.51  5100.7  840.32    5118  840.98  5139.5  842.55
  5151.9  843.69  5177.9  848.78  5208.4  859.23  5224.1  865.04  5234.4   869.3
  5241.5   871.8  5253.8  876.86  5267.4  881.98  5288.8   890.4  5303.3  894.58
#Mann= 3 ,-1 , 0
  4874.8     .09       0 4983.52     .05       0  5012.6     .09       0
Bank Sta=4983.52,5012.6
Exp/Cntr=0.3,0.1

Type RM Length L Ch R = 1 ,62500   ,515,515,515
BEGIN DESCRIPTION:
Snow Creek 126.0
END DESCRIPTION:
XS GIS Cut Line= 4
      1654497.01       997432.17       1654382.9       997302.84
       1654282.6       997298.77      1654154.67        997264.8
#Sta/Elev= 30
  4727.1   854.8  4738.7  853.95  4769.7  849.81  4772.6  849.32  4790.3  847.17
  4795.1  846.41  4808.6  843.55  4815.8  842.02  4837.1  840.08  4869.7  837.97
  4887.1  837.49  4900.3  836.79  4914.6  836.35  4922.6   836.2  4931.7  836.29
  4938.3  835.54  4955.4  833.27 4984.01  830.71  4987.9  828.69  5012.1  828.69
 5013.31  831.31  5028.1  847.69  5035.8  853.37  5046.5  860.58  5071.5  873.92
  5075.4  875.65  5092.3  880.33  5120.4  887.13  5125.1  886.78  5132.4  886.01
#Mann= 5 ,-1 , 0
  4727.1     .09       0  4808.6    .035       0  4955.4     .09       0
 4984.01     .05       0 5013.31     .09       0
Bank Sta=4984.01,5013.31
Exp/Cntr=0.5,0.3

Type RM Length L Ch R = 1 ,61985   ,210,210,210
BEGIN DESCRIPTION:
Snow Hill Church Rd. SR-1651 - US
END DESCRIPTION:
XS GIS Cut Line= 3
      1655227.35       996973.17      1654641.56       996970.64
      1654296.68        996932.6
#Sta/Elev= 30
  4391.6  867.09  4479.9  862.15    4516  862.12  4548.8  858.35  4584.5  856.29
  4614.5  853.35    4653  847.34  4668.6  843.86  4737.8  838.59  4755.1  838.44
  4767.1  838.07  4777.6  835.95  4791.8  837.28  4797.3  836.12  4802.9  836.58
  4823.7  834.39  4851.9  835.22    4864   832.9  4940.8  833.05  4977.4  829.96
    4991     830    4993  826.51    5007  826.51    5009     830  5026.9     831
    5084  836.69  5189.8  842.64  5211.2  842.62  5285.1   845.6  5324.4  845.48
#Mann= 4 ,-1 , 0
  4391.6    .035       0  4755.1     .09       0    4991     .05       0
    5009     .09       0
#XS Ineff= 2 , 0
       0  4918.4     850  5077.1       0  846.37
Permanent Ineff=
       F       F
Bank Sta=4991,5009
Exp/Cntr=0.5,0.3

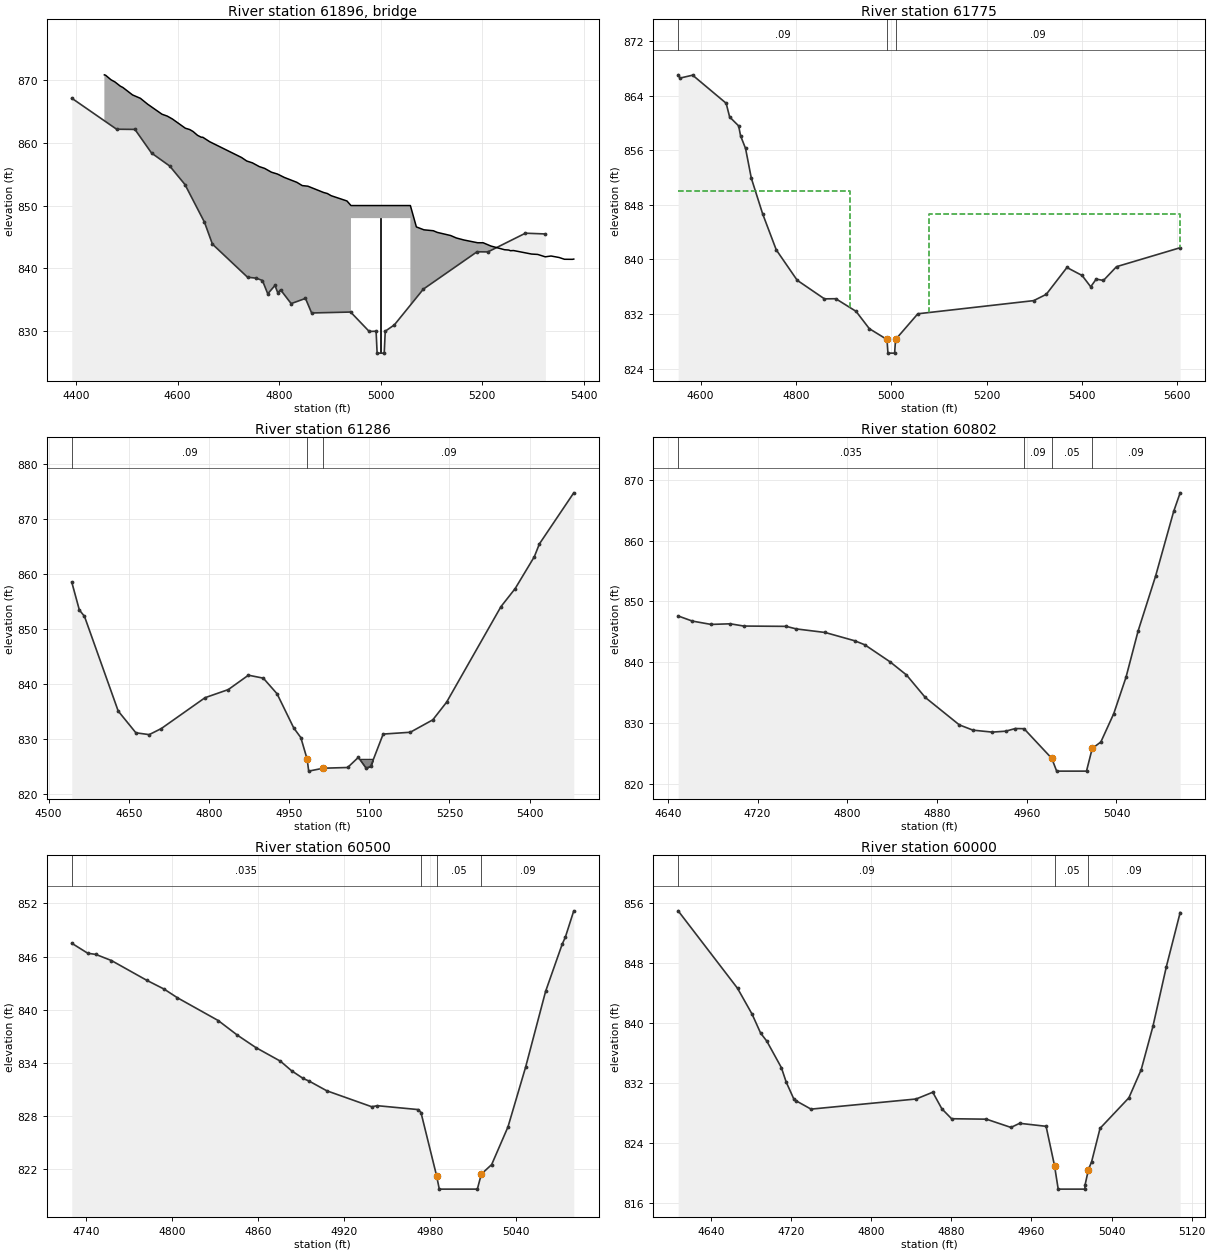
Type RM Length L Ch R = 3 ,61896   ,,,
BEGIN DESCRIPTION:
Snow Hill Church Rd. SR-1651
Structure ID: Snow Hill Church Rd. SR-1651
Approximate Survey Structure
END DESCRIPTION:
Bridge Culvert--1,0,-1,-1, 0
Deck Dist Width WeirC Skew NumUp NumDn MinLoCord MaxHiCord MaxSubmerge Is_Ogee
67.5,43,3,0, 60, 60, , , , 0, 1,1,,
  4455.8  4458.3  4468.9  4476.6  4487.3  4492.2  4511.3  4526.8    4541  4569.3
  4579.7  4589.8  4615.3  4623.9  4630.5  4639.3  4646.5  4649.7  4663.3    4726
  4736.2  4747.3    4761  4771.4  4784.9  4796.7  4810.4  4834.9  4845.5  4856.7
  4887.6  4894.9  4902.5  4933.6  4941.5  4941.5  5058.5  5058.5  5070.3  5085.1
  5103.8  5111.4  5137.8    5149  5163.9  5190.9  5201.8    5217  5243.9  5252.1
  5255.7  5261.6  5297.2  5309.3  5324.1  5335.5  5351.6  5361.9  5377.6  5380.3
  870.81  870.74  870.02  869.68     869   868.8  867.61  867.07  866.14  864.54
  864.24  863.78  862.31   862.1  861.79  861.18  860.88  860.87  860.16  857.65
  857.09   856.8   856.2  855.92  855.31  855.02  854.47   853.7  853.18  853.08
  852.08  851.92  851.57  850.73     850     850     850     850   846.6  846.14
  845.99  845.73  845.23  844.84  844.52  844.08  844.08  843.56  842.97  842.92
  842.81  842.84  842.28  842.22  841.84  841.97  841.73  841.45  841.44  841.48
  806.51  806.51  806.51  806.51  806.51  806.51  806.51  806.51  806.51  806.51
  806.51  806.51  806.51  806.51  806.51  806.51  806.51  806.51  806.51  806.51
  806.51  806.51  806.51  806.51  806.51  806.51  806.51  806.51  806.51  806.51
  806.51  806.51  806.51  806.51  806.51     848     848  806.51  806.51  806.51
  806.51  806.51  806.51  806.51  806.51  806.51  806.51  806.51  806.51  806.51
  806.51  806.51  806.51  806.51  806.51  806.51  806.51  806.51  806.51  806.51
  4455.8  4458.3  4468.9  4476.6  4487.3  4492.2  4511.3  4526.8    4541  4569.3
  4579.7  4589.8  4615.3  4623.9  4630.5  4639.3  4646.5  4649.7  4663.3    4726
  4736.2  4747.3    4761  4771.4  4784.9  4796.7  4810.4  4834.9  4845.5  4856.7
  4887.6  4894.9  4902.5  4933.6  4941.5  4941.5  5058.5  5058.5  5070.3  5085.1
  5103.8  5111.4  5137.8    5149  5163.9  5190.9  5201.8    5217  5243.9  5252.1
  5255.7  5261.6  5297.2  5309.3  5324.1  5335.5  5351.6  5361.9  5380.3  5472.5
  870.81  870.74  870.02  869.68     869   868.8  867.61  867.07  866.14  864.54
  864.24  863.78  862.31   862.1  861.79  861.18  860.88  860.87  860.16  857.65
  857.09   856.8   856.2  855.92  855.31  855.02  854.47   853.7  853.18  853.08
  852.08  851.92  851.57  850.73     850     850     850     850     848  846.14
  845.99  845.73  845.23  844.84  844.52  844.08  844.08  843.56  842.97  842.92
  842.81  842.84  842.28  842.22  841.84  841.97  841.73  841.45  841.48   838.9
  806.51  806.51  806.51  806.51  806.51  806.51  806.51  806.51  806.51  806.51
  806.51  806.51  806.51  806.51  806.51  806.51  806.51  806.51  806.51  806.51
  806.51  806.51  806.51  806.51  806.51  806.51  806.51  806.51  806.51  806.51
  806.51  806.51  806.51  806.51  806.51     848     848  806.51  806.51  806.51
  806.51  806.51  806.51  806.51  806.51  806.51  806.51  806.51  806.51  806.51
  806.51  806.51  806.51  806.51  806.51  806.51  806.51  806.51  806.51  806.51
Pier Skew, UpSta & Num, DnSta & Num=  ,5000, 2 ,5000, 2 , 0 , 0 , 0 ,0,0
       2       2
     828     850
       2       2
   826.2     850
Abutment Skew #Up #Dn= , 2 , 2
  4941.5    4950
     850  832.56
  4941.5    4950
     850  830.18
Abutment Skew #Up #Dn= , 2 , 2
    5050  5058.5
  834.19     850
    5050  5058.5
  831.66     850
BR Coef= 1 , 1 , 0 ,1.25, 0 ,,,0.8,0,2,0,
WSPro=,,,, 1 ,,,, 0 ,,,, 0 ,,,,-1 ,-1 ,-1 , 0 , 0 , 0 , 0 , 0
BC Design=,, 0 ,, 0 ,,,,,,
BC HTab HWMax=867.09

Type RM Length L Ch R = 1 ,61775   ,489,489,489
BEGIN DESCRIPTION:
Snow Hill Church Rd. SR-1651 - DS
END DESCRIPTION:
XS GIS Cut Line= 4
      1655224.82       996886.95      1654768.36        996833.7
      1654529.98       996828.63      1654177.49       996871.74
#Sta/Elev= 30
  4552.9  867.08  4556.7   866.6  4583.3  867.03  4653.6  862.91  4660.9   860.9
  4679.8  859.59  4683.9  858.13  4694.3  856.28  4706.4  851.92  4730.2  846.68
  4758.7  841.41  4802.6  836.95  4859.8  834.22  4883.6  834.24  4926.1  832.39
  4953.9  829.85    4991  828.26    4993  826.26    5007  826.26    5009  828.26
  5055.7  832.03  5298.7  833.96  5325.1  834.88  5368.5  838.82  5400.3  837.65
  5418.4  835.99  5429.9  837.12  5445.1  836.92  5472.5  838.94    5606  841.72
#Mann= 3 ,-1 , 0
  4552.9     .09       0    4991     .05       0    5009     .09       0
#XS Ineff= 2 , 0
       0  4914.1  850.11  5078.4       0  846.66
Permanent Ineff=
       F       F
Bank Sta=4991,5009
Exp/Cntr=0.5,0.3

Type RM Length L Ch R = 1 ,61286   ,484,484,484
BEGIN DESCRIPTION:
Snow Creek 124.0
END DESCRIPTION:
XS GIS Cut Line= 4
      1655267.93       996704.37      1654917.97       996534.46
      1654852.04       996526.85      1654368.77       996496.99
#Sta/Elev= 30
  4543.3  858.46  4557.5  853.39  4567.1  852.23  4630.2  835.01  4663.3  831.05
  4688.2  830.72  4710.8  831.82  4792.8  837.44  4836.2  838.91  4873.9  841.53
  4901.8  840.99  4927.5  838.15  4958.7  831.94    4972  830.18 4983.91  826.22
  4986.7  824.08    5014  824.61  5059.6  824.74  5079.6  826.58  5094.2  824.61
  5102.8  824.96  5126.1  830.82  5176.8  831.15    5219  833.41  5244.8  836.62
  5346.6  854.01  5373.1  857.28  5409.1   863.1  5418.4   865.4  5482.8   874.7
#Mann= 3 ,-1 , 0
  4543.3     .09       0 4983.91     .05       0    5014     .09       0
#Block Obstruct= 1 ,-1
  5082.8  5106.6  826.33
Bank Sta=4983.91,5014
Exp/Cntr=0.3,0.1

Type RM Length L Ch R = 1 ,60802   ,302,302,302
BEGIN DESCRIPTION:
Snow Creek 123.0
END DESCRIPTION:
XS GIS Cut Line= 3
      1655279.24       996434.08      1655106.59       996179.77
      1655062.26       996046.78
#Sta/Elev= 30
  4649.2   847.6  4661.8  846.76  4678.5  846.21  4695.7  846.31  4707.7  845.94
  4745.5  845.89  4754.5  845.47  4780.3  844.88  4806.6  843.52  4815.6  842.86
  4838.1  840.06  4852.8  837.89  4869.5   834.2  4899.9  829.68  4912.1  828.81
  4929.3  828.49  4941.2  828.64  4949.9  829.08  4957.6  829.05 4982.32  824.17
  4986.7  822.07  5013.3  822.07  5018.4   825.8  5026.1  826.87  5037.6  831.53
  5048.5   837.5  5059.3  845.12  5074.9  854.16    5091  864.79  5096.8  867.86
#Mann= 4 ,-1 , 0
  4649.2    .035       0  4957.6     .09       0 4982.32     .05       0
  5018.4     .09       0
Bank Sta=4982.32,5018.4
Exp/Cntr=0.3,0.1

Type RM Length L Ch R = 1 ,60500   ,500,500,500
BEGIN DESCRIPTION:
Snow Creek 122.0
END DESCRIPTION:
XS GIS Cut Line= 3
      1655335.24       996422.41      1655389.83       996157.81
      1655391.23       996077.11
#Sta/Elev= 30
  4729.8  847.51    4741  846.38  4746.6  846.25  4757.5  845.56  4782.3  843.32
  4794.4  842.33  4803.6  841.36  4832.2  838.78  4845.6  837.13  4858.5  835.73
  4875.7  834.19  4883.4  833.12  4891.6  832.24  4895.8  831.94  4908.1  830.85
  4939.5  829.05  4943.4  829.17    4972  828.73  4973.9   828.4 4984.81  821.26
  4986.7  819.75  5013.3  819.75  5016.1  821.45  5023.3  822.52  5034.7  826.77
    5047   833.5    5061  842.07  5072.6   847.4  5074.8  848.19  5080.7  851.17
#Mann= 4 ,-1 , 0
  4729.8    .035       0  4973.9     .09       0 4984.81     .05       0
  5016.1     .09       0
Bank Sta=4984.81,5016.1
Exp/Cntr=0.3,0.1

Type RM Length L Ch R = 1 ,60000   ,519,519,519
BEGIN DESCRIPTION:
Snow Creek 121.0
END DESCRIPTION:
XS GIS Cut Line= 3
      1655822.87        996583.4      1655884.52       996195.39
      1655904.53       996088.77
#Sta/Elev= 30
  4607.1  854.96  4666.4  844.64    4681  841.18  4689.5  838.66  4695.6  837.61
  4710.2  834.07    4715  832.15  4722.6   829.9    4725  829.64  4739.8  828.54
  4844.8  829.89  4861.4  830.79  4870.5  828.58  4880.2  827.26    4915   827.2
  4939.5   826.1  4948.2  826.65  4974.6  826.25    4983  821.02  4986.7  817.88
  5013.3  817.88  5013.6  818.48  5016.9  820.49  5020.1  821.54  5028.5  825.98
  5057.3  830.05  5069.6   833.8  5081.3  839.56  5094.7  847.51  5108.5  854.73
#Mann= 3 ,-1 , 0
  4607.1     .09       0    4983     .05       0  5016.9     .09       0
Bank Sta=4983,5016.9
Exp/Cntr=0.3,0.1

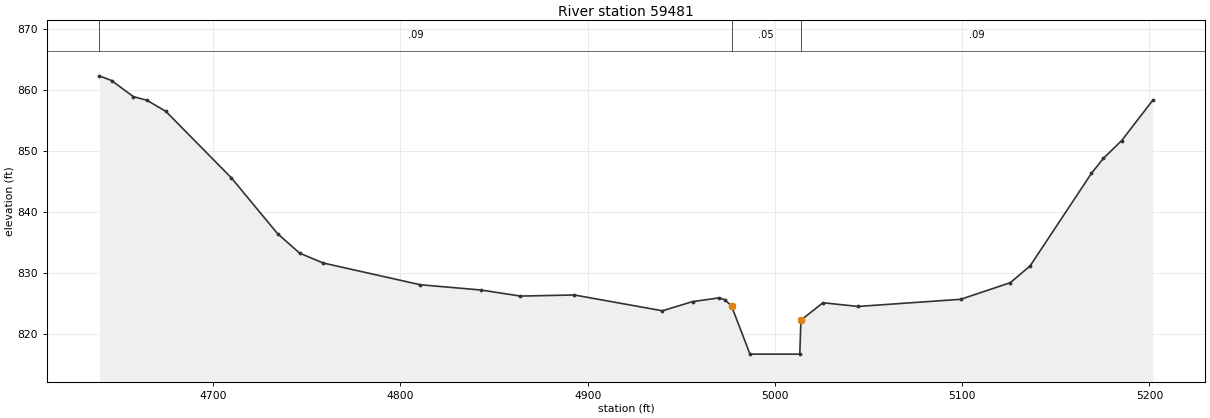
Type RM Length L Ch R = 1 ,59481   ,472,472,472
BEGIN DESCRIPTION:
Snow Creek 120.0
END DESCRIPTION:
XS GIS Cut Line= 4
      1656541.48        996597.4      1656396.77        996304.6
      1656399.15       996242.76      1656305.83       996095.77
#Sta/Elev= 30
  4639.2  862.28  4645.7  861.51  4657.4  858.87  4664.6  858.28  4674.8  856.44
  4709.7  845.57  4734.5  836.39  4746.2  833.23  4758.7  831.62  4810.7  828.05
  4842.9   827.2  4864.1   826.2  4892.9  826.38  4939.9  823.79    4956  825.29
  4970.3  825.91  4973.5  825.57  4976.9  824.52  4986.7  816.69  5013.3  816.69
  5013.9  822.26  5025.7  825.11  5044.4   824.5  5099.2  825.67  5125.7  828.39
  5136.3  831.14    5169  846.28  5175.4  848.75  5185.2  851.67  5201.8  858.28
#Mann= 3 ,-1 , 0
  4639.2     .09       0  4976.9     .05       0  5013.9     .09       0
Bank Sta=4976.9,5013.9
Exp/Cntr=0.3,0.1