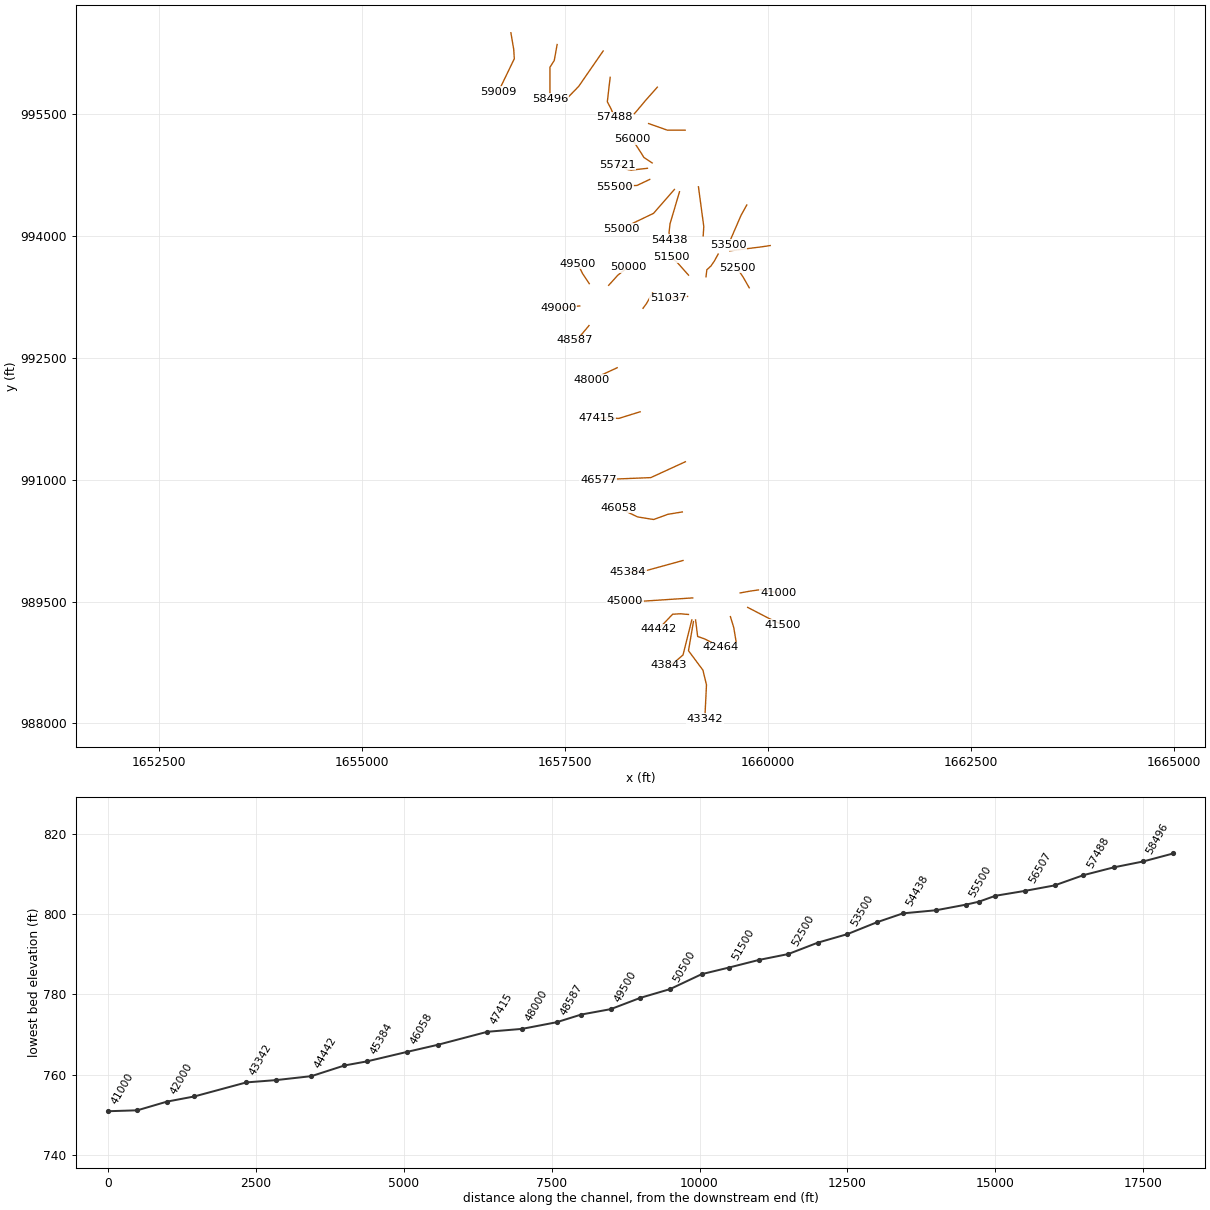
HEC-RAS study lds_snow_crk.prj: Snow Creek Limited Detail Study

--- lds_snow_crk.g02 (geometry) --- (continued)

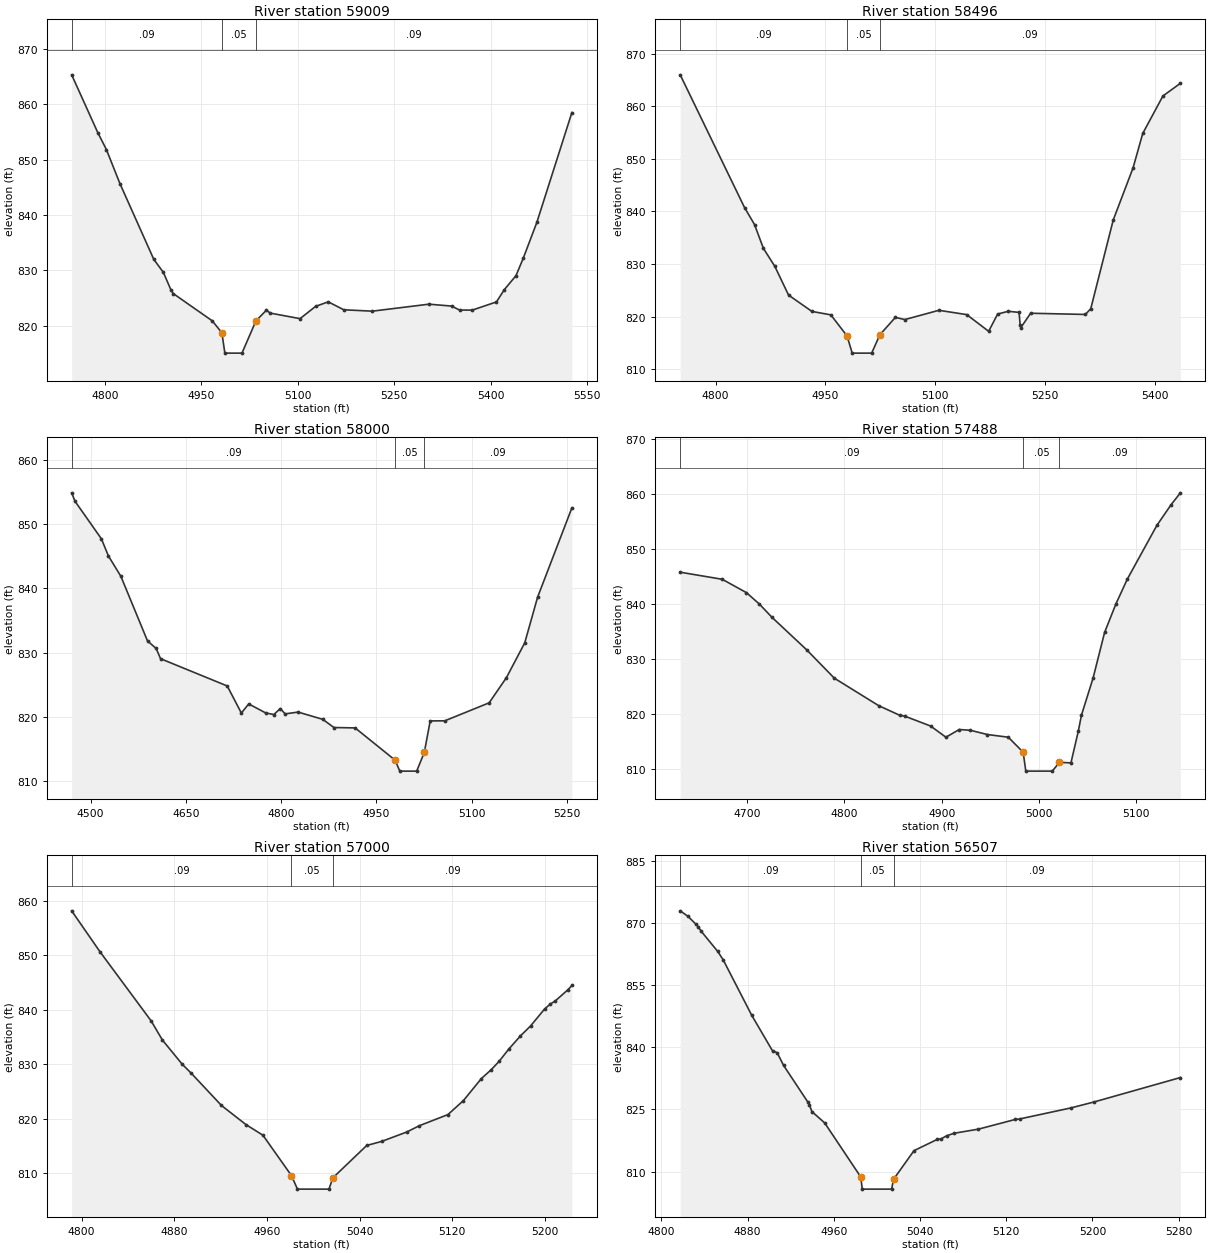
Type RM Length L Ch R = 1 ,59009   ,513,513,513
BEGIN DESCRIPTION:
Snow Creek 119.0
END DESCRIPTION:
XS GIS Cut Line= 4
      1656830.79       996504.07      1656865.78       996298.76
      1656872.78       996184.43        1656675.         995775.
#Sta/Elev= 30
  4748.6  865.28  4789.2  854.85  4802.6  851.79  4823.6  845.66  4876.2     832
  4891.2  829.62  4902.8   826.5  4906.8  825.79  4967.2  820.89  4982.1  818.73
  4986.7  815.07  5013.3  815.07    5035  820.88  5051.2  822.81  5057.3  822.29
  5103.6  821.29  5127.8  823.51  5147.4  824.32  5171.6  822.89  5215.8  822.64
  5303.9   823.9  5339.2  823.56  5351.5  822.84  5371.3  822.83  5408.9  824.31
    5421  826.51  5439.2  829.04  5450.5  832.18  5471.6  838.64  5526.1  858.47
#Mann= 3 ,-1 , 0
  4748.6     .09       0  4982.1     .05       0    5035     .09       0
Bank Sta=4982.1,5035
Exp/Cntr=0.3,0.1

Type RM Length L Ch R = 1 ,58496   ,496,496,496
BEGIN DESCRIPTION:
Snow Creek 118.0
END DESCRIPTION:
XS GIS Cut Line= 4
      1657400.08       996359.42      1657365.08       996163.43
      1657311.42       996079.44      1657311.42       995694.47
#Sta/Elev= 30
  4751.6  865.95  4839.5  840.73  4853.2  837.49  4865.3  832.97  4880.9  829.56
  4899.7  824.09  4931.6  820.99  4957.5  820.33 4979.64  816.33  4986.7  813.06
  5013.3  813.06  5024.5  816.55  5045.7  819.85  5058.7  819.44  5105.2   821.2
  5143.2  820.38  5173.2  817.21  5185.5  820.49  5200.1  821.01  5214.8   820.8
  5216.3  818.34  5217.2  817.91  5230.6  820.64  5305.5  820.41  5312.8  821.52
  5343.5  838.36  5370.6  848.27  5383.8   854.8  5411.4  861.93  5435.3  864.34
#Mann= 3 ,-1 , 0
  4751.6     .09       0 4979.64     .05       0  5024.5     .09       0
Bank Sta=4979.64,5024.5
Exp/Cntr=0.3,0.1

Type RM Length L Ch R = 1 ,58000   ,512,512,512
BEGIN DESCRIPTION:
Snow Creek 117.0
END DESCRIPTION:
XS GIS Cut Line= 3
      1657967.03       996280.09      1657665.75       995844.32
       1657486.4       995659.47
#Sta/Elev= 30
  4470.2  854.87  4475.5  853.55    4517  847.72    4528  845.06  4547.6   841.9
  4589.6  831.84  4603.2  830.67  4610.1  829.08  4715.1  824.84  4737.3  820.63
  4748.9  822.05  4775.8  820.64  4788.5   820.4  4798.6  821.33  4806.2   820.5
  4826.7  820.78  4865.5  819.65    4883  818.38  4916.4  818.32  4979.4   813.3
  4986.7   811.6  5013.3   811.6  5025.3  814.51  5034.6  819.41  5057.5  819.42
  5127.4  822.22  5154.6  826.14  5183.4  831.54  5203.6  838.63  5257.6  852.53
#Mann= 3 ,-1 , 0
  4470.2     .09       0  4979.4     .05       0  5025.3     .09       0
Bank Sta=4979.4,5025.3
Exp/Cntr=0.3,0.1

Type RM Length L Ch R = 1 ,57488   ,488,488,488
BEGIN DESCRIPTION:
Snow Creek 116.0
END DESCRIPTION:
XS GIS Cut Line= 4
      1658053.36       995955.78      1658018.36       995654.81
      1658065.03       995566.15      1658107.02       995463.49
#Sta/Elev= 30
  4631.2  845.85  4674.4  844.56  4699.3  842.13  4712.6  840.05  4725.3  837.68
  4761.3  831.71  4789.6  826.57  4835.2  821.57  4857.2  819.79    4862  819.66
  4888.5  817.87  4904.3  815.83    4918  817.23  4929.5  817.09  4946.9  816.32
  4968.4  815.83 4983.71   813.1  4986.4  809.66  5013.6  809.66    5021  811.26
  5032.8  811.16  5040.4  816.96  5043.6  819.84  5055.6  826.62  5067.4   834.9
    5079  840.07  5090.7  844.58  5121.1  854.36  5135.6   858.1  5145.3  860.29
#Mann= 3 ,-1 , 0
  4631.2     .09       0 4983.71     .05       0    5021     .09       0
Bank Sta=4983.71,5021
Exp/Cntr=0.3,0.1

Type RM Length L Ch R = 1 ,57000   ,493,493,493
BEGIN DESCRIPTION:
Snow Creek 115.0
END DESCRIPTION:
XS GIS Cut Line= 3
      1658634.32       995834.46      1658495.88       995678.53
        1658352.       995507.82
#Sta/Elev= 30
  4791.5  858.11  4815.8  850.65  4860.1  837.94  4869.8  834.44    4887  829.98
  4894.5   828.4  4920.8  822.44    4942  818.93  4956.6  816.99 4981.23  809.59
  4986.4  807.11  5013.6  807.11 5016.98  809.18  5046.2  815.11  5059.2  815.86
  5080.8  817.58  5091.6  818.73  5116.3  820.77  5129.7  823.34  5145.2  827.38
  5153.7     829  5160.5  830.53  5168.7  832.74  5178.9  835.19  5187.6     837
  5199.7  840.11  5204.4  840.98  5209.1  841.62    5220  843.67  5223.3  844.44
#Mann= 3 , 0 , 0
  4791.5     .09       0 4981.23     .05       0 5016.98     .09       0
Bank Sta=4981.23,5016.98
Exp/Cntr=0.3,0.1

Type RM Length L Ch R = 1 ,56507   ,507,507,507
BEGIN DESCRIPTION:
Snow Creek 114.0
END DESCRIPTION:
XS GIS Cut Line= 3
      1658977.29       995304.83      1658757.97       995304.83
      1658526.99       995386.49
#Sta/Elev= 30
  4817.4  872.91  4824.7  871.56  4832.2  869.62  4834.1  869.08  4836.8  868.01
  4852.2  863.12  4857.3  861.09  4883.8   847.7  4903.1  839.12  4907.4  838.69
  4913.4   835.6  4936.1  826.69  4937.4  826.07  4939.6  824.49  4951.5  821.75
    4985   808.7  4986.4  805.77  5013.6  805.77 5015.49  808.16  5034.4  815.05
  5056.1  817.78  5059.6   817.9  5064.7  818.64  5071.7  819.25  5094.2  820.24
  5128.4  822.58  5132.5   822.7  5179.7  825.34  5201.7  826.81  5281.7  832.69
#Mann= 3 , 0 , 0
  4817.4     .09       0    4985     .05       0 5015.49     .09       0
Bank Sta=4985,5015.49
Exp/Cntr=0.3,0.1

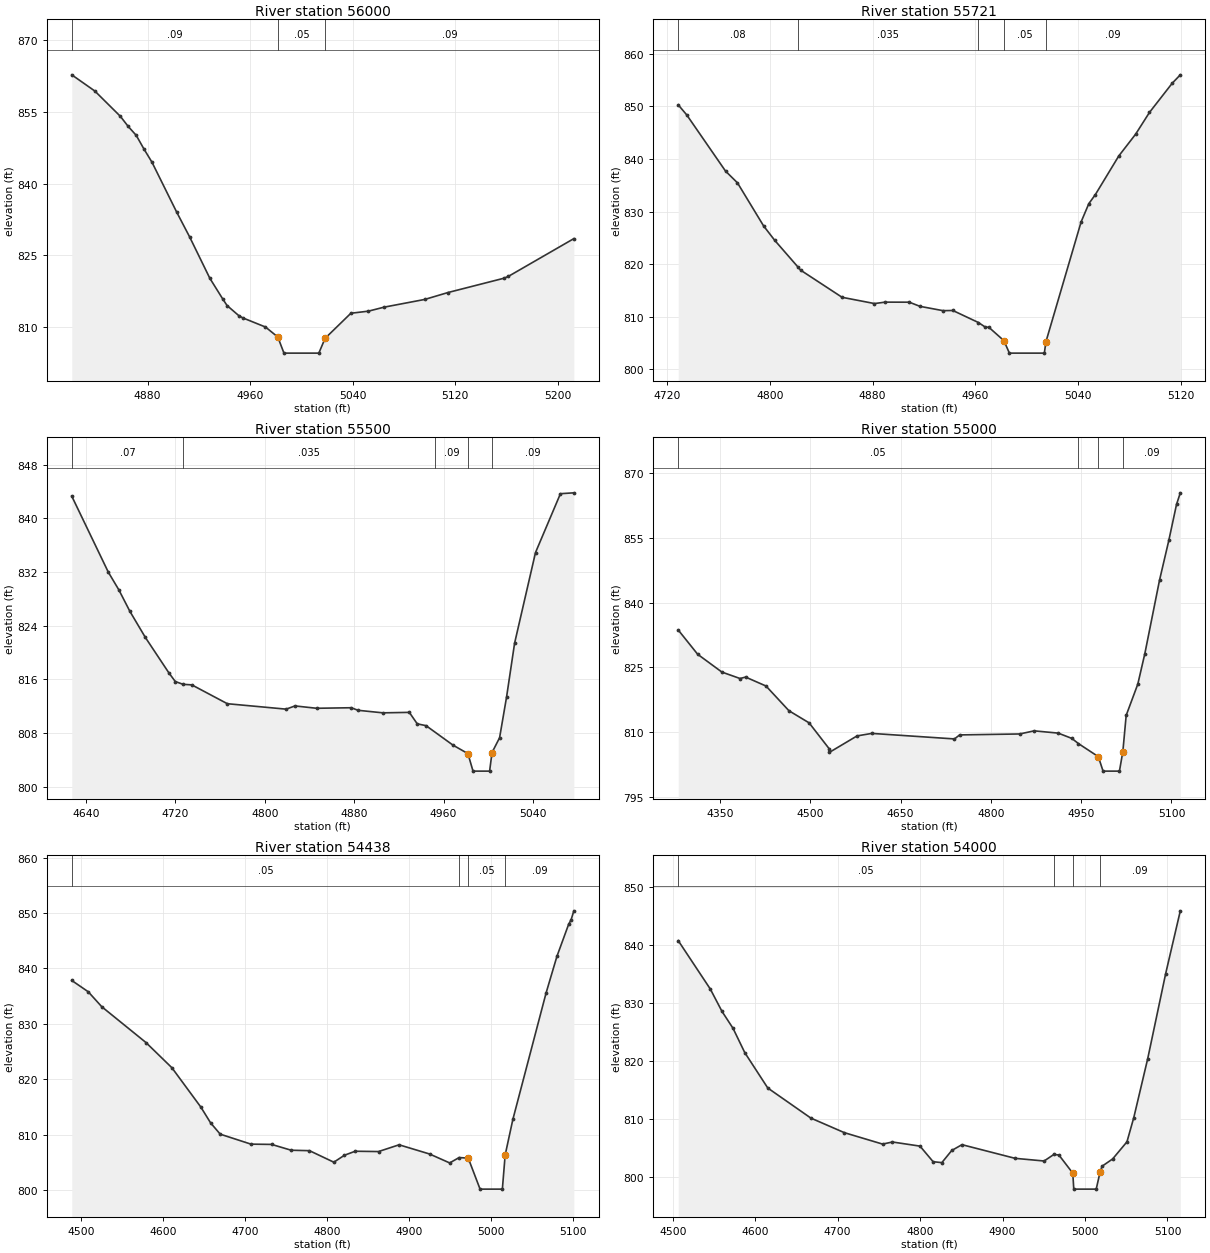
Type RM Length L Ch R = 1 ,56000   ,279,279,279
BEGIN DESCRIPTION:
Snow Creek 113.0
END DESCRIPTION:
XS GIS Cut Line= 4
      1658571.32        994901.2      1658468.66       994968.86
      1658439.43       995016.76      1658324.01       995195.17
#Sta/Elev= 27
  4820.9  862.74  4838.9  859.35  4858.8  854.06  4864.9  851.95  4871.2  850.07
  4877.1  847.27  4883.5  844.44  4902.7  834.04  4912.8  828.85  4928.6  820.18
  4938.6  815.88    4942  814.49  4951.1  812.39  4954.3   811.9    4972  809.99
  4981.6   807.9  4986.4  804.53  5013.6  804.53 5018.47  807.62  5038.6  812.87
  5052.3  813.31  5064.4  814.14  5096.2  815.76  5114.4  817.21  5157.9  820.19
  5161.3  820.56  5212.5  828.48
#Mann= 3 , 0 , 0
  4820.9     .09       0  4981.6     .05       0 5018.47     .09       0
Bank Sta=4981.6,5018.47
Exp/Cntr=0.3,0.1

Type RM Length L Ch R = 1 ,55721   ,221,221,221
BEGIN DESCRIPTION:
Snow Creek 112.5
END DESCRIPTION:
XS GIS Cut Line= 5
       1658512.5       994835.42      1658309.72       994812.25
      1658261.44        994821.9      1658201.57       994860.53
      1658137.84       994877.91
#Sta/Elev= 30
  4728.7  850.29  4735.3  848.38  4765.5  837.69  4774.8  835.45  4795.1  827.27
  4803.7  824.54  4821.9  819.43  4823.9  818.85  4856.2  813.68  4881.4  812.49
  4889.7  812.76  4908.5  812.75  4916.8  811.96  4934.7  811.14  4942.4  811.17
  4962.3  808.88  4967.7     808  4970.4  807.98  4982.1  805.44  4986.4  803.06
  5013.6  803.06  5014.8   805.2  5042.2  828.02  5048.2  831.49  5053.3  833.22
  5071.5  840.56  5084.6   844.7  5095.4  848.85  5113.1   854.4  5119.4     856
#Mann= 5 ,-1 , 0
  4728.7     .08       0  4821.9    .035       0  4962.3     .09       0
  4982.1     .05       0  5014.8     .09       0
Bank Sta=4982.1,5014.8
Exp/Cntr=0.3,0.1

Type RM Length L Ch R = 1 ,55500   ,500,500,500
BEGIN DESCRIPTION:
Snow Creek 112.0
END DESCRIPTION:
XS GIS Cut Line= 4
      1658540.99       994698.21      1658382.33       994623.55
      1658185.13       994620.62      1658109.36       994609.55
#Sta/Elev= 30
  4627.4  843.31  4660.1  831.98  4669.5  829.35  4679.4  826.14  4693.2  822.26
  4714.2  816.99    4720  815.68    4727  815.26  4734.8  815.18  4766.6  812.37
  4819.2  811.56  4827.1  812.04  4846.5  811.69 4877.47  811.77 4883.49  811.39
 4905.71  811.01  4929.4  811.08 4936.49  809.37 4944.36   809.1 4968.43   806.2
 4981.83  804.93  4986.4  802.32 5001.24  802.32  5003.4  805.09 5010.17   807.3
 5016.39  813.35  5023.6   821.4  5042.3  834.91  5064.6  843.68  5076.6  843.81
#Mann= 5 ,-1 , 0
  4627.4     .07       0    4727    .035       0  4952.7     .09       0
 4981.83     .05       0  5003.4     .09       0
Bank Sta=4981.83,5003.4
Exp/Cntr=0.3,0.1

Type RM Length L Ch R = 1 ,55000   ,562,562,562
BEGIN DESCRIPTION:
Snow Creek 111.0
END DESCRIPTION:
XS GIS Cut Line= 4
       1658844.3       994574.56      1658587.65       994280.58
        1658291.       994138.53      1658186.35       994091.59
#Sta/Elev= 30
  4280.8  833.64  4313.1  828.01  4353.3  823.89  4383.4   822.4  4392.7  822.73
  4426.6  820.66  4464.7  814.93  4498.2  812.12  4531.3  806.16  4531.9  805.29
  4577.8   809.1  4602.3  809.68  4739.6   808.4  4748.2  809.33  4847.9  809.55
    4872  810.27  4911.8  809.75  4934.6  808.52  4945.4  807.33 4978.55  804.29
  4986.4  800.94  5013.6  800.94 5019.27  805.48  5024.8  813.86  5044.1   821.1
  5055.8  828.17  5080.2   845.2  5095.6  854.39  5108.4  862.73  5114.7  865.42
#Mann= 4 ,-1 , 0
  4280.8     .05       0  4945.4     .09       0 4978.55     .05       0
 5019.27     .09       0
Bank Sta=4978.55,5019.27
Exp/Cntr=0.3,0.1

Type RM Length L Ch R = 1 ,54438   ,438,438,438
BEGIN DESCRIPTION:
Snow Creek 110.0
END DESCRIPTION:
XS GIS Cut Line= 4
      1658907.29       994546.56      1658790.64       994152.25
      1658778.97       994047.26       1658781.3        993951.6
#Sta/Elev= 30
  4488.3  837.82  4508.4  835.78  4524.9  833.08  4578.8  826.62  4610.5  822.06
  4645.8  814.96  4657.7  812.11  4669.4  810.08  4706.9  808.28  4732.1  808.23
    4756  807.18  4778.3   807.1    4808  805.02    4821  806.28  4834.1     807
  4862.5  806.94  4887.6  808.16  4924.8   806.5  4949.3  804.89  4960.9  805.86
    4972  805.75  4986.4  800.16  5013.6  800.16    5017  806.31  5026.4  812.74
    5067   835.6  5080.2  842.19  5094.4  847.94  5097.4  848.75  5100.8  850.39
#Mann= 4 ,-1 , 0
  4488.3     .05       0  4960.9     .09       0    4972     .05       0
    5017     .09       0
Bank Sta=4972,5017
Exp/Cntr=0.3,0.1

Type RM Length L Ch R = 1 ,54000   ,500,500,500
BEGIN DESCRIPTION:
Snow Creek 109.0
END DESCRIPTION:
XS GIS Cut Line= 3
      1659140.61       994607.22      1659206.28       994118.32
      1659198.94       994002.93
#Sta/Elev= 30
  4506.7  840.72  4545.6  832.39  4559.7  828.56  4573.2  825.62  4587.4  821.45
  4615.3  815.36  4667.6  810.18  4708.3  807.67  4754.5  805.71  4766.5  806.07
  4799.9  805.36  4815.8  802.68  4826.4  802.52  4838.4  804.61  4850.8  805.61
  4915.2  803.26  4950.4   802.8  4962.2  803.92  4968.3  803.84  4985.2  800.71
  4986.4  797.96  5013.6  797.96  5018.4  800.96  5020.7   801.9  5033.5  803.15
  5050.9   806.1  5059.2  810.28  5076.1  820.43  5097.8  835.02  5115.6  845.85
#Mann= 4 ,-1 , 0
  4506.7     .05       0  4962.2     .09       0  4985.2     .05       0
  5018.4     .09       0
Bank Sta=4985.2,5018.4
Exp/Cntr=0.3,0.1

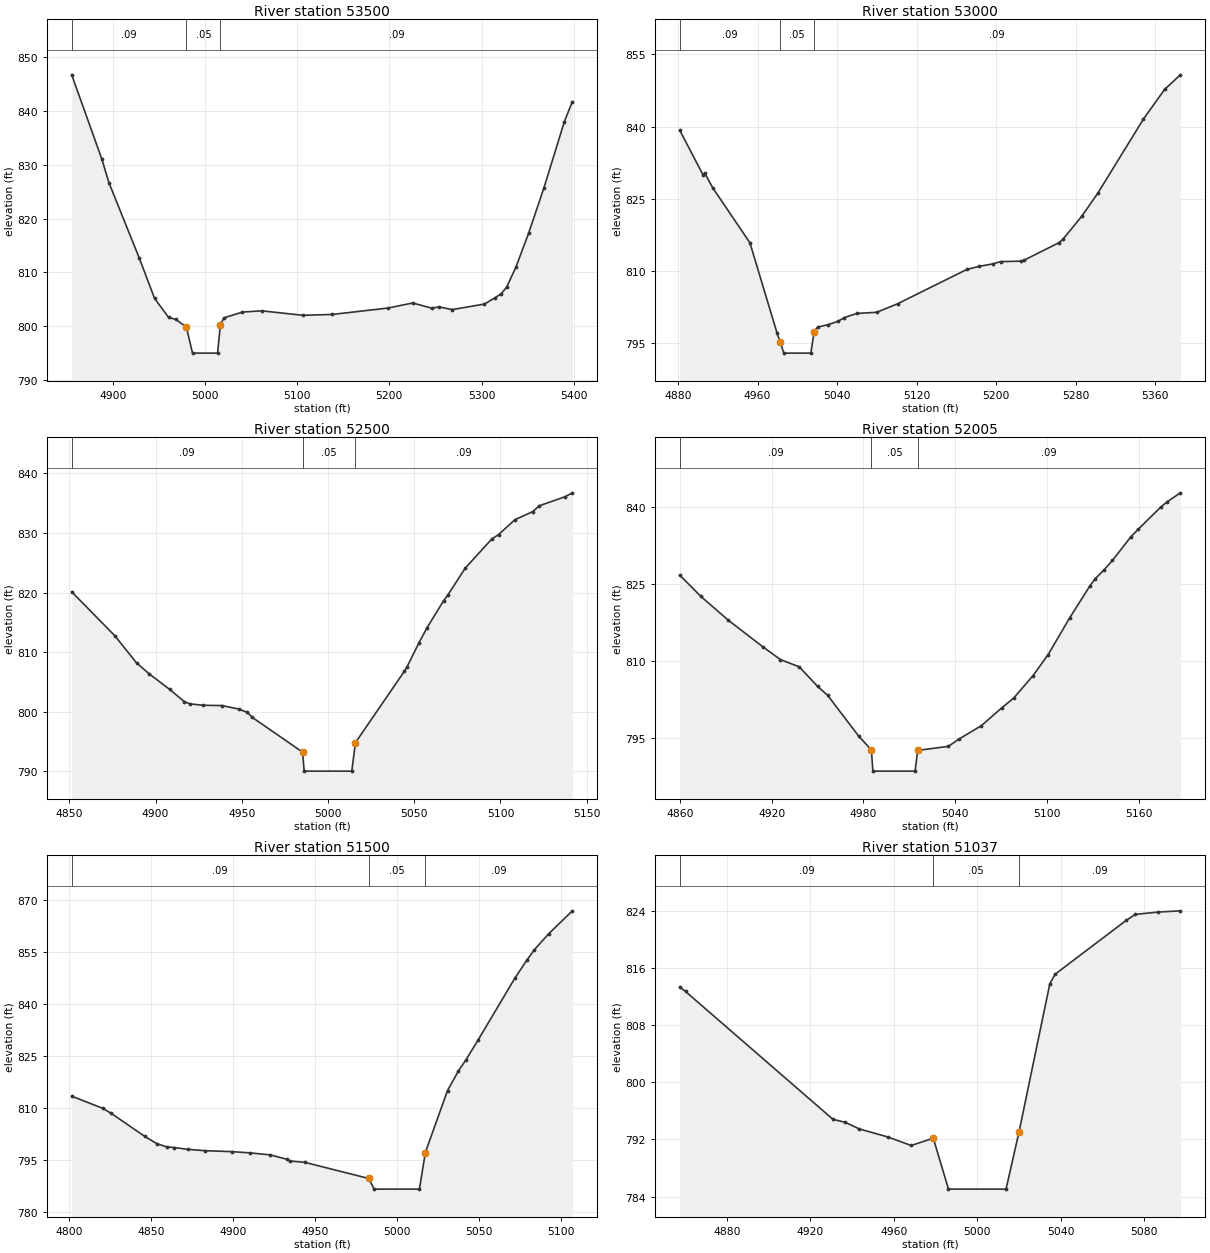
Type RM Length L Ch R = 1 ,53500   ,500,500,500
BEGIN DESCRIPTION:
Snow Creek 108.0
END DESCRIPTION:
XS GIS Cut Line= 3
      1659735.56       994383.24      1659665.46       994256.63
      1659506.92       993890.94
#Sta/Elev= 30
  4855.3  846.71  4887.9   831.1  4895.8  826.62  4928.7  812.63  4945.2  805.17
  4960.4  801.65  4968.3  801.25  4979.7  799.85  4986.4     795  5013.6     795
  5016.6  800.18  5020.4  801.55  5040.6  802.63  5061.4  802.86  5106.1  802.03
  5138.2  802.19  5198.6  803.38  5225.3  804.32  5245.8  803.36    5254  803.58
  5268.3  803.09  5303.2  804.12    5315  805.32  5321.6  806.07  5327.2  807.25
  5337.3  810.96    5351  817.23  5367.8  825.74  5389.9  838.01  5398.6  841.75
#Mann= 3 , 0 , 0
  4855.3     .09       0  4979.7     .05       0  5016.6     .09       0
Bank Sta=4979.7,5016.6
Exp/Cntr=0.3,0.1

Type RM Length L Ch R = 1 ,53000   ,500,500,500
BEGIN DESCRIPTION:
Snow Creek 107.0
END DESCRIPTION:
XS GIS Cut Line= 3
      1660024.88       993883.94      1659907.84       993866.57
      1659525.58       993818.61
#Sta/Elev= 30
  4881.7  839.26  4905.2  829.94  4906.8  830.34  4914.8  827.31  4952.3  815.84
  4979.7     797  4982.9  795.15  4986.4  792.88  5013.6  792.88    5017  797.37
  5020.4  798.29  5030.6  798.78  5040.9  799.49  5047.3  800.28  5059.9  801.13
    5080  801.38    5101  803.16  5170.5  810.28  5182.4   810.9  5196.8  811.45
  5204.4  811.91  5224.6  812.01  5227.8  812.18  5262.9  815.82    5267  816.52
  5286.3   821.4  5302.2  826.13    5348  841.52  5369.5  847.74  5385.3  850.76
#Mann= 3 , 0 , 0
  4881.7     .09       0  4982.9     .05       0    5017     .09       0
Bank Sta=4982.9,5017
Exp/Cntr=0.3,0.1

Type RM Length L Ch R = 1 ,52500   ,495,495,495
BEGIN DESCRIPTION:
Snow Creek 106.0
END DESCRIPTION:
XS GIS Cut Line= 3
       1659765.9       993363.65       1659692.3       993492.75
      1659614.24       993610.96
#Sta/Elev= 30
  4851.4  820.13  4876.5  812.73    4889   808.2  4896.2   806.4  4908.2  803.75
  4916.7   801.7  4919.9  801.34  4927.4  801.09  4938.6  801.04  4948.2  800.46
  4953.3  799.88  4956.2  799.04 4985.25  793.23  4986.2  790.04  5013.8  790.04
  5015.9  794.82  5044.2  806.76  5045.9  807.58  5052.8   811.6  5057.5  814.14
    5067  818.62  5069.4  819.56  5079.6  824.11  5094.9  828.97  5098.9  829.74
  5108.4  832.23  5118.6  833.57  5122.6  834.58  5137.4  836.08  5141.7  836.74
#Mann= 3 , 0 , 0
  4851.4     .09       0 4985.25     .05       0  5015.9     .09       0
Bank Sta=4985.25,5015.9
Exp/Cntr=0.3,0.1

Type RM Length L Ch R = 1 ,52005   ,505,505,505
BEGIN DESCRIPTION:
Snow Creek 105.0
END DESCRIPTION:
XS GIS Cut Line= 5
      1659233.47       993499.97      1659244.21       993585.92
      1659293.64       993631.04      1659336.61       993693.36
      1659383.88       993779.31
#Sta/Elev= 30
  4859.9   826.8  4873.8  822.64  4891.7     818  4914.1  812.86  4925.7  810.34
  4938.1  808.91    4950  805.11  4956.6  803.37    4977  795.37  4985.2  792.73
  4986.2  788.58  5013.8  788.58 5015.44  792.62  5035.5  793.41  5042.6  794.86
  5057.1  797.44  5070.3  800.89  5078.2  802.81  5090.9  807.22  5100.8  811.32
  5114.8  818.45  5128.2  824.77  5131.5  826.09  5137.2  827.79  5142.8  829.67
  5154.9   834.3  5159.6  835.73  5174.4  840.08  5178.6  841.11  5187.2  842.85
#Mann= 3 , 0 , 0
  4859.9     .09       0  4985.2     .05       0 5015.44     .09       0
Bank Sta=4985.2,5015.44
Exp/Cntr=0.3,0.1

Type RM Length L Ch R = 1 ,51500   ,463,463,463
BEGIN DESCRIPTION:
Snow Creek 104.0
END DESCRIPTION:
XS GIS Cut Line= 3
       1659018.6       993519.31      1658886.79        993667.7
      1658806.97       993739.29
#Sta/Elev= 28
  4801.5  813.52  4820.4  810.02  4825.5   808.6  4846.2  801.88  4853.5  799.81
  4859.5  798.88  4864.2  798.69  4872.6  798.16  4883.1  797.78  4899.3  797.51
  4910.1  797.16  4922.5  796.59    4933   795.3  4934.5  794.82  4943.9  794.41
  4982.8  789.77  4986.2  786.69  5013.8  786.69 5017.43  797.26 5030.96  815.15
  5037.6  820.77  5042.3  824.08  5049.8  829.86    5072  847.51  5079.3   852.7
    5084  855.79  5092.7  860.37  5107.2  867.01
#Mann= 3 , 0 , 0
  4801.5     .09       0  4982.8     .05       0 5017.43     .09       0
Bank Sta=4982.8,5017.43
Exp/Cntr=0.3,0.1

Type RM Length L Ch R = 1 ,51037   ,537,537,537
BEGIN DESCRIPTION:
Snow Creek 103.0
END DESCRIPTION:
XS GIS Cut Line= 3
      1659006.16        993257.2      1658880.75       993245.53
      1658767.01       993236.78
#Sta/Elev= 17
  4857.3  813.32  4860.1  812.71  4930.8  794.81  4936.6   794.4  4943.4  793.47
    4957  792.35  4968.3  791.15  4978.9  792.17  4986.2  785.04  5013.8  785.04
 5020.06   793.1  5034.8   813.8  5037.3  815.12  5071.5  822.68  5075.8   823.5
  5086.5  823.82  5097.4     824
#Mann= 3 , 0 , 0
  4857.3     .09       0  4978.9     .05       0 5020.06     .09       0
Bank Sta=4978.9,5020.06
Exp/Cntr=0.3,0.1

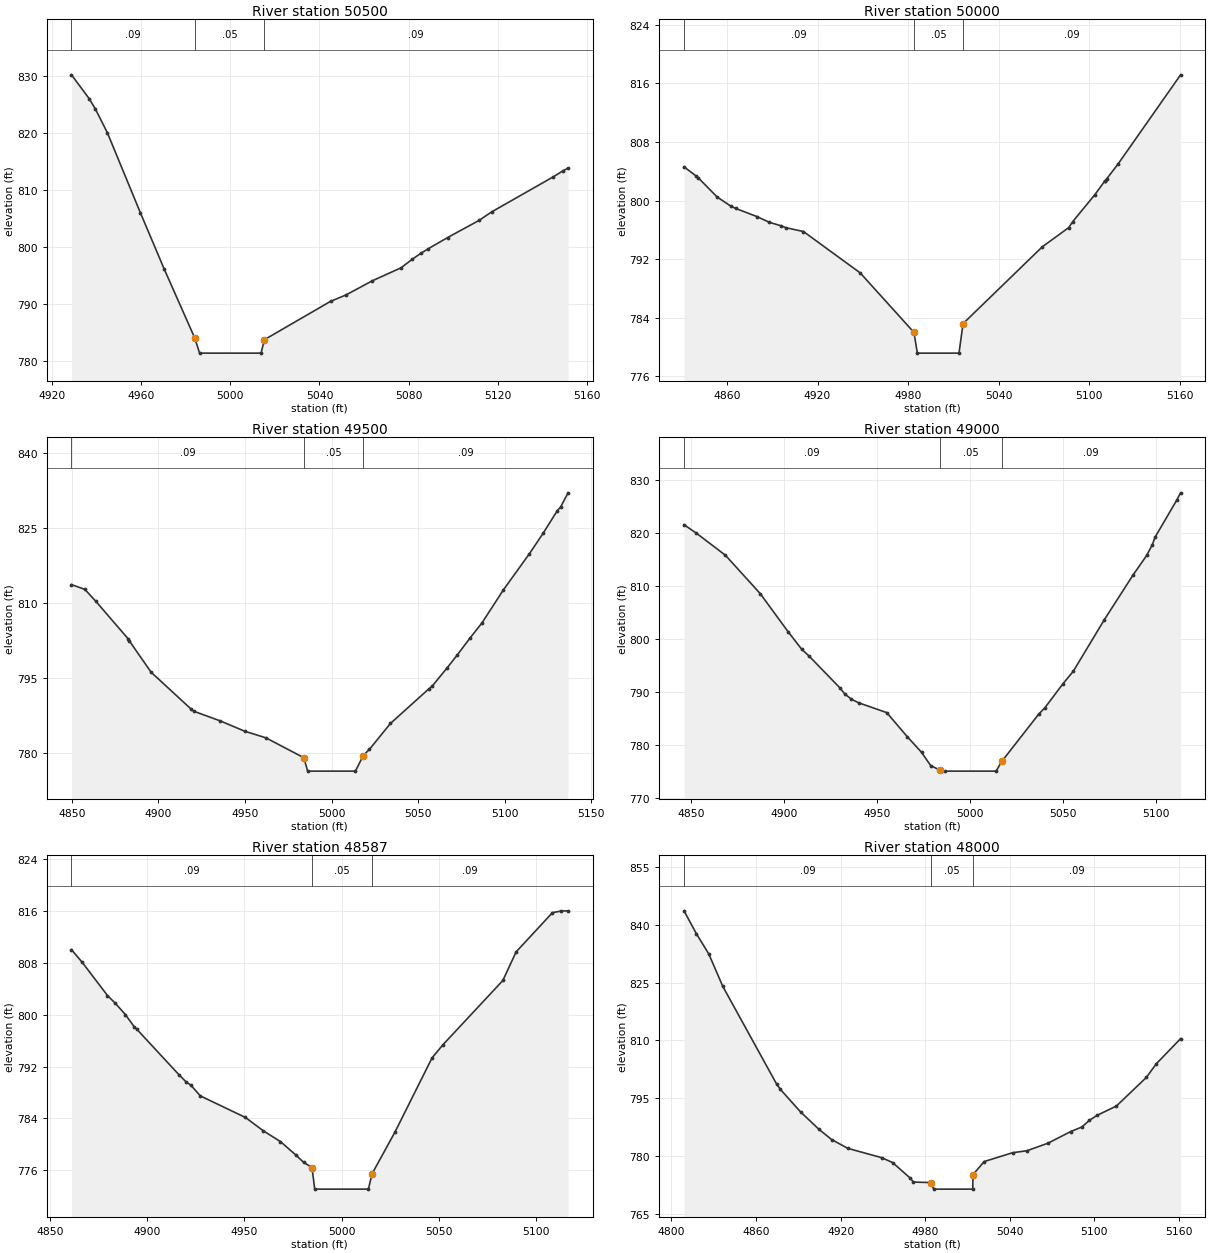
Type RM Length L Ch R = 1 ,50500   ,500,500,500
BEGIN DESCRIPTION:
Snow Creek 102.0
END DESCRIPTION:
XS GIS Cut Line= 3
      1658457.87       993111.38      1658500.28       993168.73
      1658574.53       993300.95
#Sta/Elev= 23
  4928.7  830.16  4936.6     826  4939.4  824.18  4944.8     820  4959.6  805.97
  4970.3  796.08 4984.01  783.98  4986.2  781.31  5013.8  781.31 5015.29  783.67
    5045   790.4  5051.9  791.52  5063.7     794  5076.6  796.28  5081.7   797.8
  5085.4   798.8  5088.7   799.6  5097.5  801.59  5111.7  804.62  5117.3   806.1
  5144.9  812.24  5149.2  813.28  5151.6  813.79
#Mann= 3 , 0 , 0
  4928.7     .09       0 4984.01     .05       0 5015.29     .09       0
Bank Sta=4984.01,5015.29
Exp/Cntr=0.3,0.1

Type RM Length L Ch R = 1 ,50000   ,500,500,500
BEGIN DESCRIPTION:
Snow Creek 101.0
END DESCRIPTION:
XS GIS Cut Line= 3
      1658034.99       993394.27      1658148.13       993519.09
      1658274.13       993618.84
#Sta/Elev= 25
  4831.5   804.6  4839.4  803.37    4841  803.09  4853.5  800.47  4862.5  799.24
  4865.7  798.92  4879.9   797.8  4888.1  797.02  4895.8  796.55    4899  796.29
  4910.7  795.76  4948.3  790.11 4983.91  781.99  4986.2  779.15  5013.8  779.15
 5016.48  783.18    5069  793.67  5086.6  796.31  5089.2  797.12  5103.7  800.75
  5110.4  802.64  5110.8  802.68  5111.7  802.96  5119.3     805  5160.7  817.17
#Mann= 3 , 0 , 0
  4831.5     .09       0 4983.91     .05       0 5016.48     .09       0
Bank Sta=4983.91,5016.48
Exp/Cntr=0.3,0.1

Type RM Length L Ch R = 1 ,49500   ,500,500,500
BEGIN DESCRIPTION:
Snow Creek 100.0
END DESCRIPTION:
XS GIS Cut Line= 3
      1657795.84       993414.69      1657712.93        993539.9
      1657652.93       993662.58
#Sta/Elev= 29
  4849.8  813.65  4857.5   812.7  4863.7  810.37  4882.4  802.86  4883.3  802.35
  4895.8  796.12  4918.6  788.84  4920.4  788.32  4935.4  786.43  4949.8  784.33
  4962.1     783    4984  779.02  4986.2  776.34  5013.8  776.34  5018.3  779.46
  5021.9  780.71    5034  785.87  5056.1  792.77    5058  793.29  5066.9  797.06
  5072.6  799.57  5079.9  802.93  5086.8  805.95  5099.3  812.62  5114.2  819.79
  5122.2  823.92  5130.3  828.39  5132.4  829.24  5136.6  832.01
#Mann= 3 , 0 , 0
  4849.8     .09       0    4984     .05       0  5018.3     .09       0
Bank Sta=4984,5018.3
Exp/Cntr=0.3,0.1

Type RM Length L Ch R = 1 ,49000   ,413,413,413
BEGIN DESCRIPTION:
Snow Creek 99.0
END DESCRIPTION:
XS GIS Cut Line= 3
      1657679.18       993140.54       1657526.1       993123.78
      1657413.78       993111.38
#Sta/Elev= 30
    4846  821.61  4852.7  819.99  4868.3  815.82    4887  808.56  4901.9  801.39
  4909.3  798.04  4913.2  796.77  4929.9  790.71  4932.4   789.6    4936   788.6
  4940.1  787.89    4955  786.06  4966.1  781.48  4973.7  778.56  4978.6  776.05
  4983.5  775.19  4986.2  774.99  5013.8  774.99 5016.88  776.84  5036.7  785.76
  5040.1  787.01  5049.8  791.54  5055.3  793.88    5072  803.64  5087.4  812.07
  5094.8  815.81  5097.8  817.82  5099.3  819.26  5110.9  826.24    5113  827.64
#Mann= 3 , 0 , 0
    4846     .09       0  4983.5     .05       0 5016.88     .09       0
Bank Sta=4983.5,5016.88
Exp/Cntr=0.3,0.1

Type RM Length L Ch R = 1 ,48587   ,587,587,587
BEGIN DESCRIPTION:
Snow Creek 98.0
END DESCRIPTION:
XS GIS Cut Line= 3
      1657792.92       992898.48      1657687.93       992773.07
      1657615.02       992717.66
#Sta/Elev= 28
  4861.2  810.01  4866.6  808.11  4879.7  802.95  4883.7  801.76  4888.9  800.01
  4893.5   798.1  4894.7  797.77  4916.4  790.74  4920.2   789.6  4922.5  789.14
  4927.4  787.47  4950.6  784.14  4959.7   782.1  4968.6  780.42  4976.7   778.3
  4980.5  777.22  4984.8  776.42  4986.2  773.09  5013.8  773.09 5015.64  775.44
  5027.4  781.86  5046.5  793.33  5052.1  795.36  5082.9  805.27  5089.7  809.68
  5108.4  815.73  5112.9  815.98  5116.4  816.01
#Mann= 3 , 0 , 0
  4861.2     .09       0  4984.8     .05       0 5015.64     .09       0
Bank Sta=4984.8,5015.64
Exp/Cntr=0.3,0.1

Type RM Length L Ch R = 1 ,48000   ,585,585,585
BEGIN DESCRIPTION:
Snow Creek 97.0
END DESCRIPTION:
XS GIS Cut Line= 3
      1658139.98       992379.35      1657966.61       992298.99
      1657819.17       992233.53
#Sta/Elev= 30
  4808.9  843.63  4817.6  837.74  4826.5  832.43  4836.4  824.04  4874.6  798.69
  4877.3   797.3  4891.6  791.47  4904.7  786.93  4913.7  784.28  4925.2     782
  4949.2  779.59  4956.9  778.33  4969.5  774.27  4971.7  773.26 4983.91  773.13
  4986.2  771.43  5013.8  771.43    5014   775.2  5021.9  778.58  5042.1  780.88
  5052.3  781.39  5067.2  783.35  5083.2  786.34  5091.3  787.56  5096.6  789.29
  5101.9  790.54  5115.8     793    5137  800.41  5144.1  803.96  5161.3  810.47
#Mann= 3 , 0 , 0
  4808.9     .09       0 4983.91     .05       0    5014     .09       0
Bank Sta=4983.91,5014
Exp/Cntr=0.3,0.1

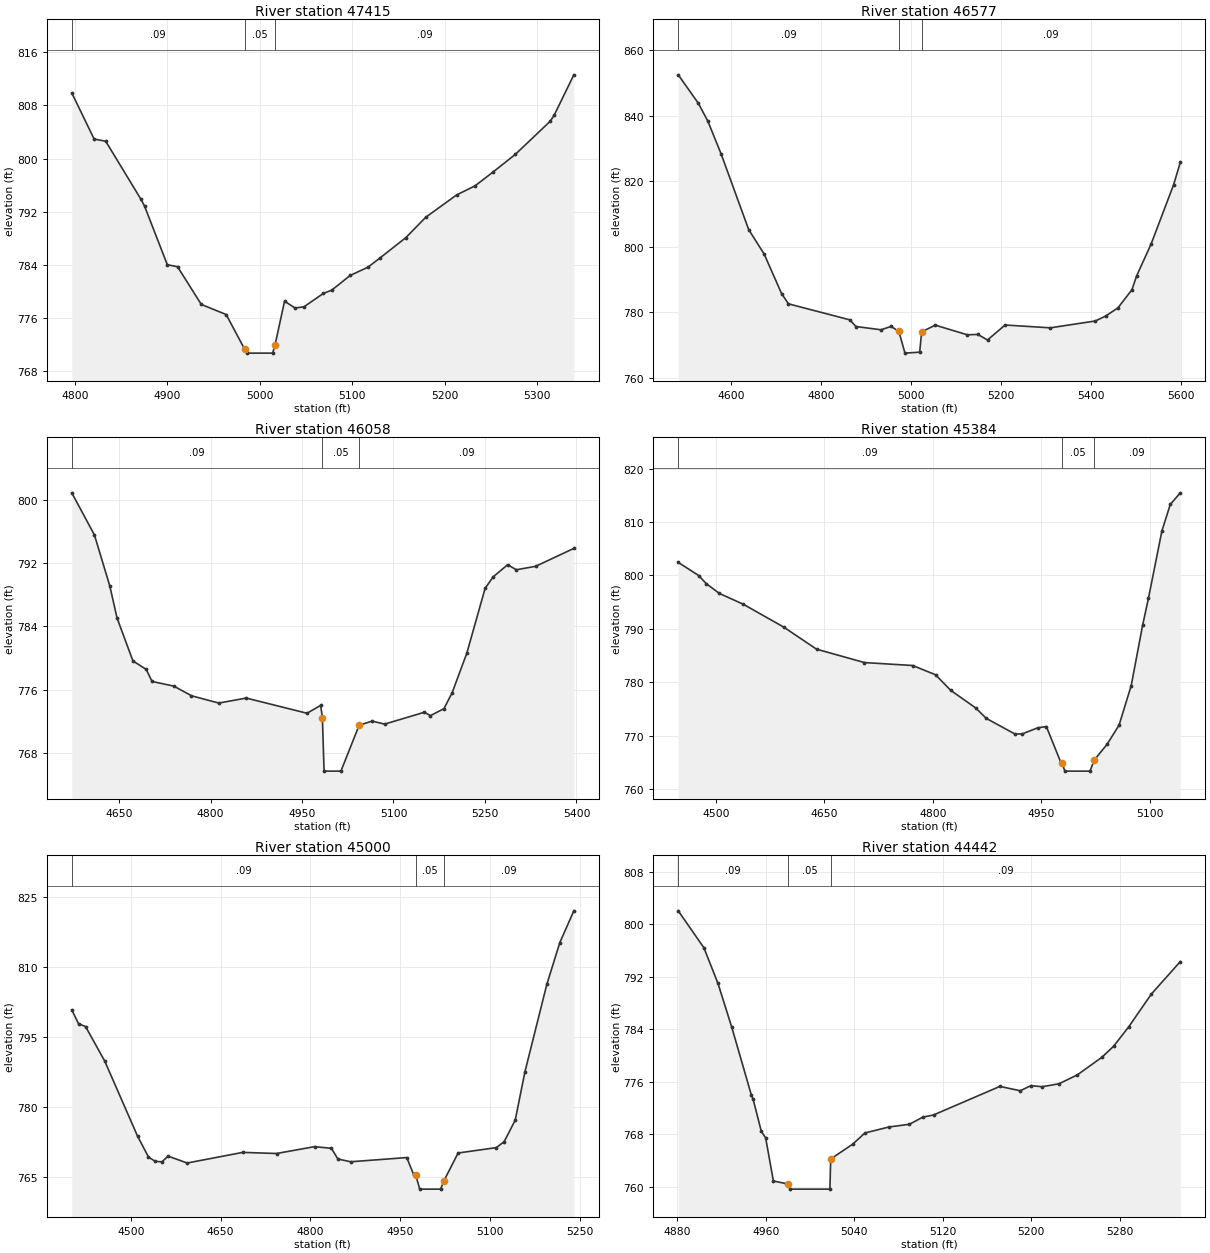
Type RM Length L Ch R = 1 ,47415   ,838,838,838
BEGIN DESCRIPTION:
Snow Creek 96.0
END DESCRIPTION:
XS GIS Cut Line= 3
      1658422.87       991836.89      1658160.39       991755.23
      1657892.08       991763.98
#Sta/Elev= 30
  4796.4  809.88  4820.6  802.93  4833.1  802.61  4871.4  793.84  4875.2  792.83
  4899.8  784.02  4910.9  783.71  4936.6  778.04  4963.5  776.52 4983.61  771.28
  4986.2  770.71  5013.8  770.71 5016.29  771.87  5026.7  778.53  5037.9  777.51
  5047.6  777.67  5068.7   779.7  5077.8  780.19  5097.7   782.4  5116.9  783.64
  5129.8  785.01    5158   788.1  5179.5  791.16    5213  794.53  5232.8  795.88
    5252  797.93  5276.4  800.62  5314.2  805.61  5318.4  806.49  5339.8   812.6
#Mann= 3 , 0 , 0
  4796.4     .09       0 4983.61     .05       0 5016.29     .09       0
Bank Sta=4983.61,5016.29
Exp/Cntr=0.3,0.1

Type RM Length L Ch R = 1 ,46577   ,519,519,519
BEGIN DESCRIPTION:
Snow Creek 94.0
END DESCRIPTION:
XS GIS Cut Line= 3
      1658979.91       991221.52      1658554.11       991026.12
      1657906.66       990999.87
#Sta/Elev= 30
    4482  852.51  4526.4  843.88  4547.8  838.37  4577.3  828.37  4638.6  805.24
  4673.1  797.73  4711.9  785.64  4727.1  782.53  4863.3  777.65  4877.3   775.6
  4933.1   774.6  4955.2  775.63  4972.6  774.12  4986.2  767.47  5018.9  767.76
 5023.24  773.95  5053.5  776.03  5124.8  773.07  5148.2  773.18  5169.8  771.49
  5208.8  776.06  5309.4   775.2  5409.5  777.29  5433.2  778.86  5459.8  781.31
  5490.9  786.83  5501.4  791.08  5533.7  800.86  5583.6  818.93  5598.5  825.77
#Mann= 3 , 0 , 0
    4482     .09       0  4972.6     .05       0 5023.24     .09       0
Bank Sta=4972.6,5023.24
Exp/Cntr=0.3,0.1

Type RM Length L Ch R = 1 ,46058   ,674,674,674
BEGIN DESCRIPTION:
Snow Creek 93.0
END DESCRIPTION:
XS GIS Cut Line= 5
        1658942.       990603.24       1658764.1       990574.07
      1658589.11       990509.91      1658390.79       990541.99
      1658160.39       990652.82
#Sta/Elev= 30
  4572.5  800.87  4609.7  795.54  4634.8  789.12  4646.8  785.04  4672.8  779.63
  4694.6  778.56  4704.1  777.04  4739.9  776.45  4768.8  775.23  4813.5  774.31
  4858.6  774.94  4958.3  773.02  4980.6  774.02  4983.4  772.47  4986.2  765.71
  5013.8  765.71  5043.7  771.51    5065  772.03  5085.5  771.65  5150.7  773.15
  5160.6  772.72  5182.7   773.6  5196.3  775.64  5220.2  780.61  5250.2   788.8
  5263.5  790.26  5287.2  791.79  5301.4  791.15  5333.2  791.59  5395.7  793.85
#Mann= 3 , 0 , 0
  4572.5     .09       0  4983.4     .05       0  5043.7     .09       0
Bank Sta=4983.4,5043.7
Exp/Cntr=0.3,0.1

Type RM Length L Ch R = 1 ,45384   ,384,384,384
BEGIN DESCRIPTION:
Snow Creek 92.0
END DESCRIPTION:
XS GIS Cut Line= 4
      1658950.75       990005.37      1658504.53       989882.87
      1658417.04       989877.04      1658274.13       989859.54
#Sta/Elev= 30
    4448  802.43  4476.4  799.96  4486.7  798.46  4504.9  796.62  4538.2  794.58
    4594  790.31  4639.2  786.19  4705.5  783.68  4772.1  783.13  4803.8   781.4
  4824.8  778.48  4859.4  775.18  4873.9  773.24  4913.8  770.29  4923.9  770.34
  4945.2  771.47  4957.1   771.7  4977.4  764.88  4978.9  764.87  4982.6  763.36
  5017.4  763.36  5023.2  765.42  5041.1  768.39  5057.6  771.97  5074.4  779.37
  5090.2  790.68  5098.3  795.75  5116.8  808.29  5128.4  813.28  5142.3  815.45
#Mann= 3 , 0 , 0
    4448     .09       0  4978.9     .05       0  5023.2     .09       0
Bank Sta=4978.9,5023.2
Exp/Cntr=0.3,0.1

Type RM Length L Ch R = 1 ,45000   ,558,558,558
BEGIN DESCRIPTION:
Snow Creek 91.0
END DESCRIPTION:
XS GIS Cut Line= 3
      1659070.32       989544.57      1658473.18       989505.38
       1658233.3       989506.65
#Sta/Elev= 30
  4401.6  800.77    4413  797.78  4424.6   797.2  4456.6   789.8  4511.5  773.67
  4529.7  769.22  4540.7   768.3  4552.1  768.18  4562.4   769.4  4594.3  767.93
  4687.1  770.21  4743.5  769.97  4807.1  771.44  4835.1  771.08    4846  768.78
  4867.4   768.2  4960.9   769.1  4972.4  765.47    4976  765.29  4982.6  762.33
  5017.4  762.33  5023.2  764.18  5046.7  770.08  5110.5  771.23  5123.5   772.5
    5142  777.11  5158.2  787.47  5194.8  806.25  5216.5   815.2  5239.9  822.01
#Mann= 3 , 0 , 0
  4401.6     .09       0    4976     .05       0  5023.2     .09       0
Bank Sta=4976,5023.2
Exp/Cntr=0.3,0.1

Type RM Length L Ch R = 1 ,44442   ,599,599,599
BEGIN DESCRIPTION:
Snow Creek 90.0
END DESCRIPTION:
XS GIS Cut Line= 4
      1659017.83       989340.42      1658918.67       989349.17
      1658822.43       989343.33      1658644.52       989156.68
#Sta/Elev= 30
  4880.9  802.03  4904.1  796.41  4916.8  790.99  4929.3  784.31  4946.9  774.05
  4948.6  773.35    4956  768.46  4959.9  767.49  4966.9  760.92  4980.4  760.45
    4982  759.68    5018  759.68  5018.7  764.27  5038.5  766.51  5049.7  768.23
  5071.2  769.13  5089.9  769.55  5101.9  770.63  5111.7  770.97  5171.6  775.31
  5190.1  774.65  5199.6  775.43  5209.9  775.26    5225  775.71  5241.6  777.06
  5263.7  779.73  5274.4  781.42  5288.2  784.41  5308.6  789.38  5334.7  794.31
#Mann= 3 , 0 , 0
  4880.9     .09       0  4980.4     .05       0  5018.7     .09       0
Bank Sta=4980.4,5018.7
Exp/Cntr=0.3,0.1

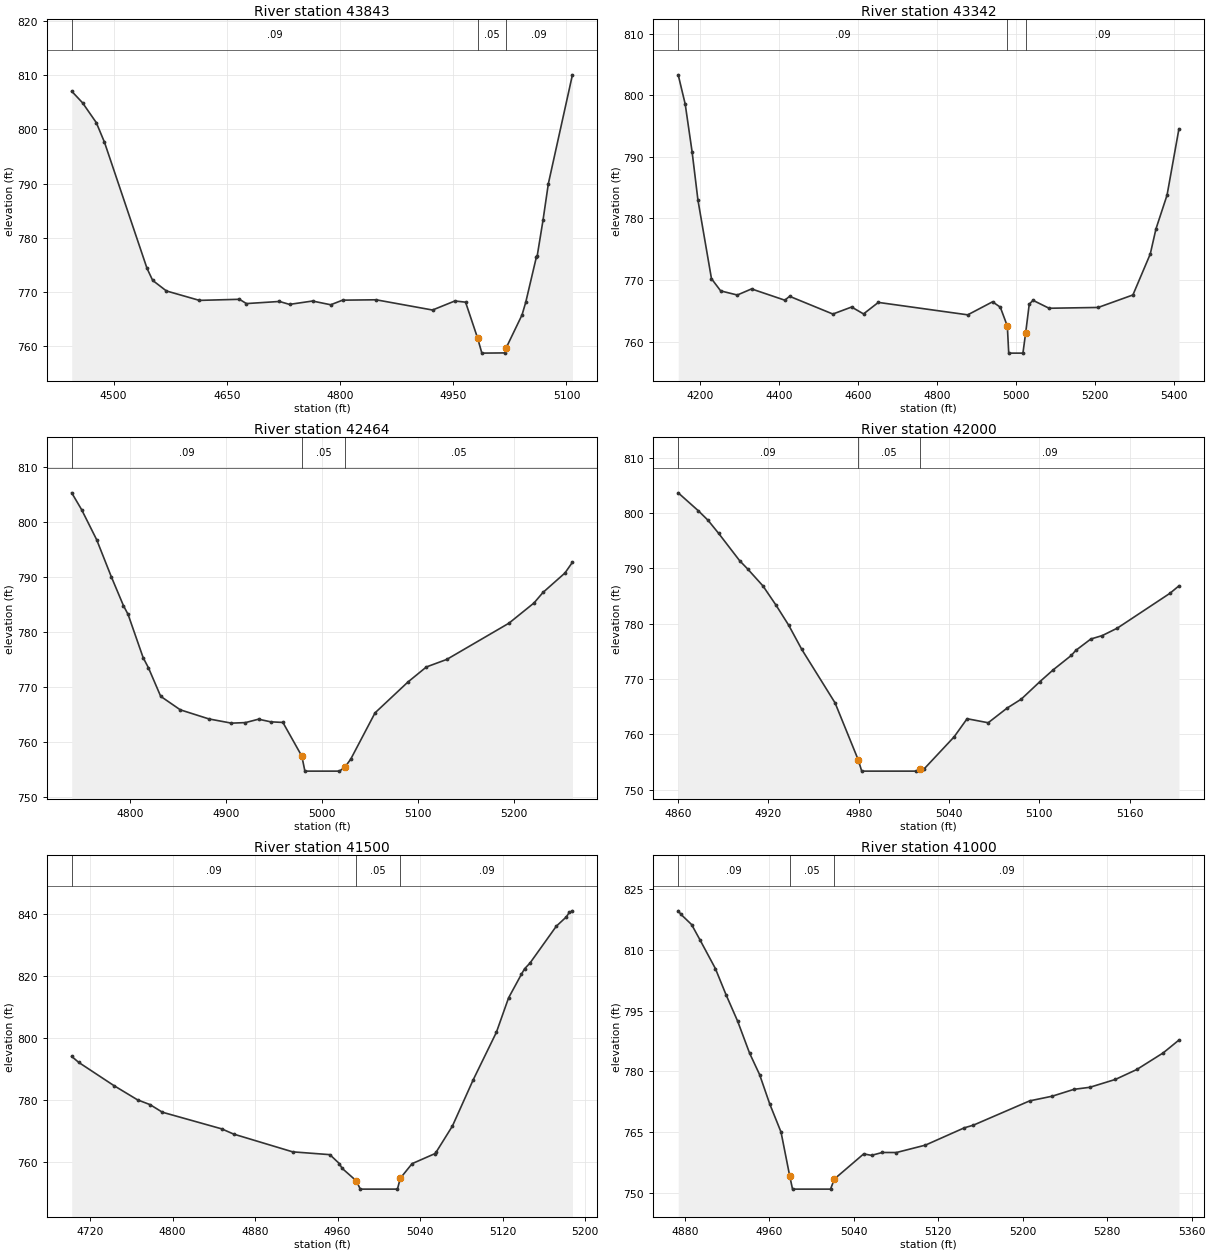
Type RM Length L Ch R = 1 ,43843   ,501,501,501
BEGIN DESCRIPTION:
Snow Creek 89.0
END DESCRIPTION:
XS GIS Cut Line= 4
      1659058.66       989273.34      1658950.75        988841.7
      1658869.09       988771.71      1658772.85        988716.3
#Sta/Elev= 30
  4444.4  807.05  4458.8  804.91    4477  801.25  4487.8  797.64  4544.2  774.34
  4551.7  772.12  4569.9  770.17  4613.6  768.43  4666.7  768.63  4675.9  767.84
  4719.6  768.23    4733  767.69  4763.5  768.31  4787.6  767.62  4803.3  768.47
  4847.7  768.54  4922.5  766.65  4952.1  768.32  4966.3   768.1 4982.32  761.43
 4987.88  758.69    5018  758.73  5019.7  759.55  5041.1  765.74    5046  768.07
    5060  776.36  5061.3  776.71  5068.9  783.22    5076  789.99  5107.9  810.08
#Mann= 3 , 0 , 0
  4444.4     .09       0 4982.32     .05       0  5019.7     .09       0
Bank Sta=4982.32,5019.7
Exp/Cntr=0.3,0.1

Type RM Length L Ch R = 1 ,43342   ,878,878,878
BEGIN DESCRIPTION:
Snow Creek 88.0
END DESCRIPTION:
XS GIS Cut Line= 5
      1659079.07       989252.92      1659017.83        988894.2
      1659195.73       988655.05      1659239.48       988474.23
      1659219.06       988054.27
#Sta/Elev= 30
  4144.7  803.33  4162.4  798.59  4179.9  790.83  4194.7  782.99    4229  770.21
  4252.3  768.23  4294.4  767.56  4330.5  768.55  4414.8  766.72  4426.9  767.35
  4536.5  764.47    4584  765.61  4614.2  764.49  4651.7  766.36  4878.2  764.34
  4941.1  766.46  4960.7  765.58  4978.5  762.51    4982  758.12    5018  758.12
    5025  761.46    5034  766.07  5043.5   766.7  5084.2  765.41  5208.6  765.54
  5296.6  767.57  5340.6  774.23    5355   778.3  5383.1  783.79  5413.2  794.56
#Mann= 3 , 0 , 0
  4144.7     .09       0  4978.5     .05       0    5025     .09       0
Bank Sta=4978.5,5025
Exp/Cntr=0.3,0.1

Type RM Length L Ch R = 1 ,42464   ,464,464,464
BEGIN DESCRIPTION:
Snow Creek 86.0
END DESCRIPTION:
XS GIS Cut Line= 4
      1659105.32       989273.34      1659130.71       989069.37
      1659216.15       989040.02      1659417.38       988937.95
#Sta/Elev= 30
  4739.1  805.38  4749.4  802.32  4765.1  796.83  4780.3   790.1    4793  784.81
  4797.8  783.22  4813.5  775.33    4819  773.49  4831.8  768.27  4852.2  765.81
    4882  764.15  4905.5  763.38  4920.1  763.48  4933.7   764.1  4946.4  763.62
  4959.1  763.51 4978.85  757.35    4982  754.63    5018  754.63  5023.8  755.37
  5029.8  756.83  5055.1  765.26  5089.4  770.89  5108.6  773.63  5129.8     775
  5194.5   781.6  5220.7   785.3    5230  787.21  5252.9  790.76  5260.7  792.72
#Mann= 3 , 0 , 0
  4739.1     .09       0 4978.85     .05       0  5023.8     .05       0
Bank Sta=4978.85,5023.8
Exp/Cntr=0.3,0.1

Type RM Length L Ch R = 1 ,42000   ,500,500,500
BEGIN DESCRIPTION:
Snow Creek 85.0
END DESCRIPTION:
XS GIS Cut Line= 3
      1659534.04       989314.17      1659575.22       989180.49
      1659606.95       988990.44
#Sta/Elev= 30
  4860.1  803.68  4873.5  800.43  4879.9  798.72  4886.9  796.37  4900.9  791.41
  4906.2  789.92  4916.4  786.84  4925.2  783.31  4933.5  779.73  4942.2  775.35
  4964.3  765.68 4979.64  755.41    4982  753.34    5018  753.34  5020.7  753.67
  5023.2  753.67  5043.4  759.55    5052  762.82    5066  762.09  5078.6  764.75
    5088  766.37  5100.4  769.54  5109.3  771.69  5121.3  774.29  5124.1  775.16
  5134.2  777.24  5141.8  777.86  5151.8  779.21  5186.7   785.5  5192.7  786.85
#Mann= 3 , 0 , 0
  4860.1     .09       0 4979.64     .05       0  5020.7     .09       0
Bank Sta=4979.64,5020.7
Exp/Cntr=0.3,0.1

Type RM Length L Ch R = 1 ,41500   ,500,500,500
BEGIN DESCRIPTION:
Snow Creek 84.0
END DESCRIPTION:
XS GIS Cut Line= 3
      1659746.94       989427.91      1660011.17       989290.79
      1660181.49       989212.09
#Sta/Elev= 30
  4702.3  794.06  4709.2  792.11  4743.1  784.66  4766.1  780.03  4778.2  778.49
  4790.2  776.03  4847.7  770.65  4859.3  768.96  4916.4  763.23  4952.5  762.32
  4961.6  759.46  4964.3  757.93 4978.05  753.88    4982  751.18    5018  751.18
 5020.75  754.69  5032.2  759.41  5054.4  762.66  5055.7  763.23  5071.3  771.58
  5091.4  786.49  5113.9  801.86  5125.7  812.98  5138.1  820.58  5141.2  822.38
  5146.4   824.2    5172  836.15  5181.7  839.15  5184.5  840.58  5187.6  841.11
#Mann= 3 , 0 , 0
  4702.3     .09       0 4978.05     .05       0 5020.75     .09       0
Bank Sta=4978.05,5020.75
Exp/Cntr=0.3,0.1

Type RM Length L Ch R = 1 ,41000   ,500,500,500
BEGIN DESCRIPTION:
Snow Creek 83.0
END DESCRIPTION:
XS GIS Cut Line= 4
      1659653.61       989605.81      1659777.94       989628.32
      1659907.34       989646.64      1660121.18       989607.89
#Sta/Elev= 30
  4873.7   819.6  4876.3  818.73  4886.4  816.21  4894.2   812.5  4908.9  805.37
    4919  798.91    4930  792.38  4941.3   784.5  4950.8   779.2  4960.4  771.96
  4971.1  765.02 4979.34  754.17    4982  750.95    5018  750.95 5021.65  753.45
  5049.4  759.64  5056.8  759.28    5067  759.99  5080.4  759.98  5107.8   761.8
  5144.7  766.07  5153.4  766.74  5206.6  772.72  5227.9  773.87  5248.6  775.57
  5263.6  776.07  5287.8  778.01  5308.1  780.46  5333.1  784.56    5348  787.72
#Mann= 3 , 0 , 0
  4873.7     .09       0 4979.34     .05       0 5021.65     .09       0
Bank Sta=4979.34,5021.65
Exp/Cntr=0.3,0.1