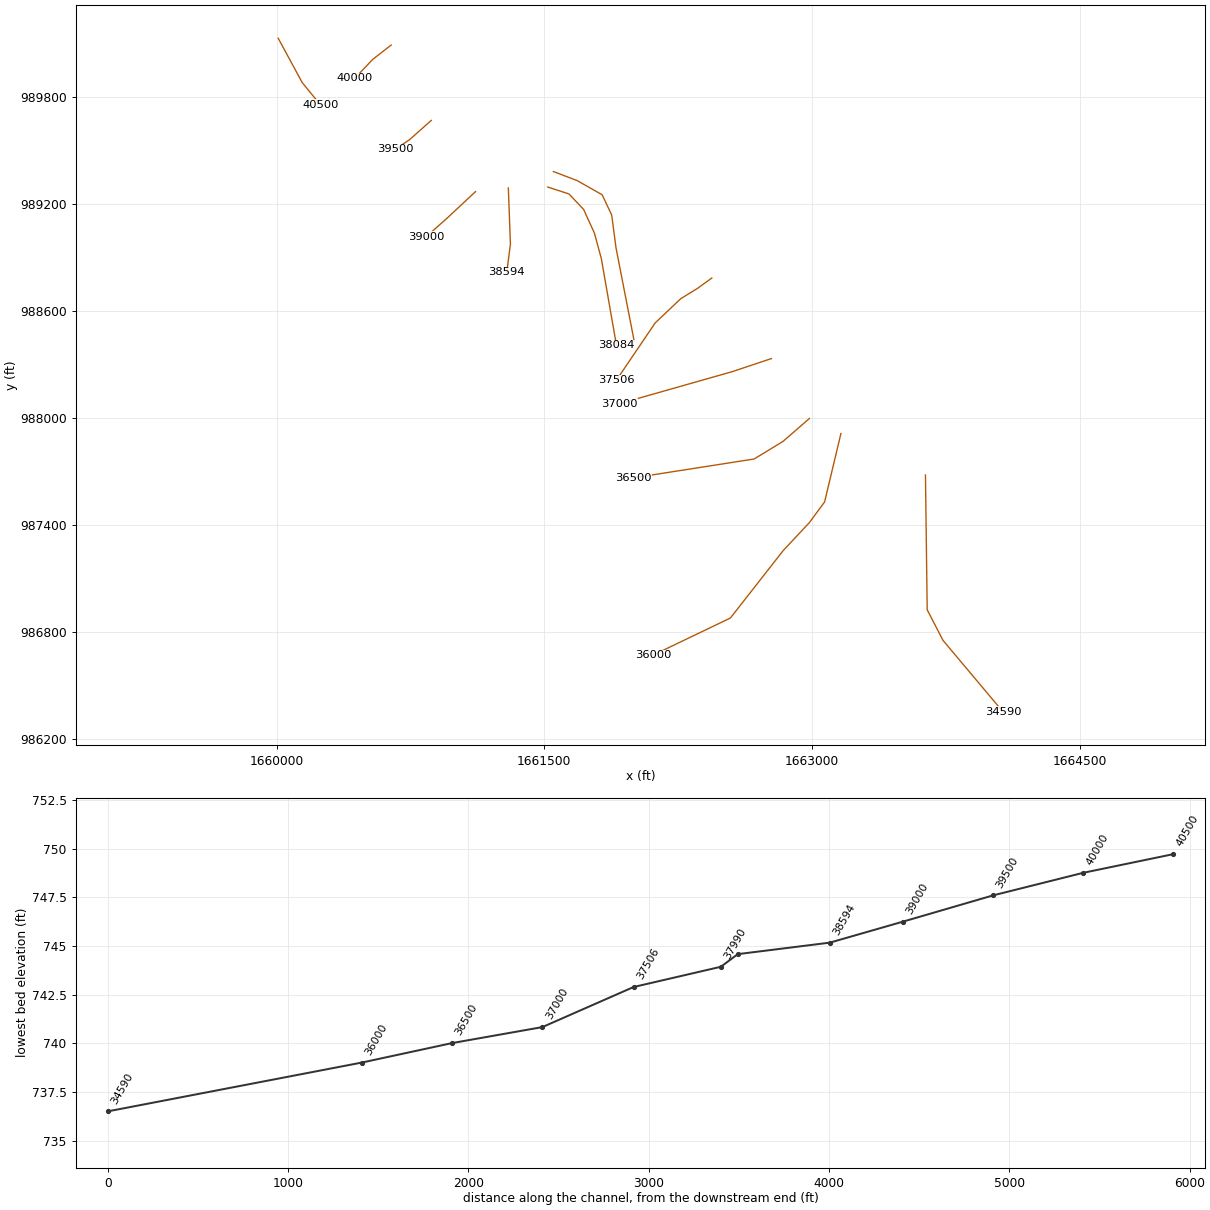
HEC-RAS study lds_snow_crk.prj: Snow Creek Limited Detail Study

--- lds_snow_crk.g02 (geometry) --- (continued)

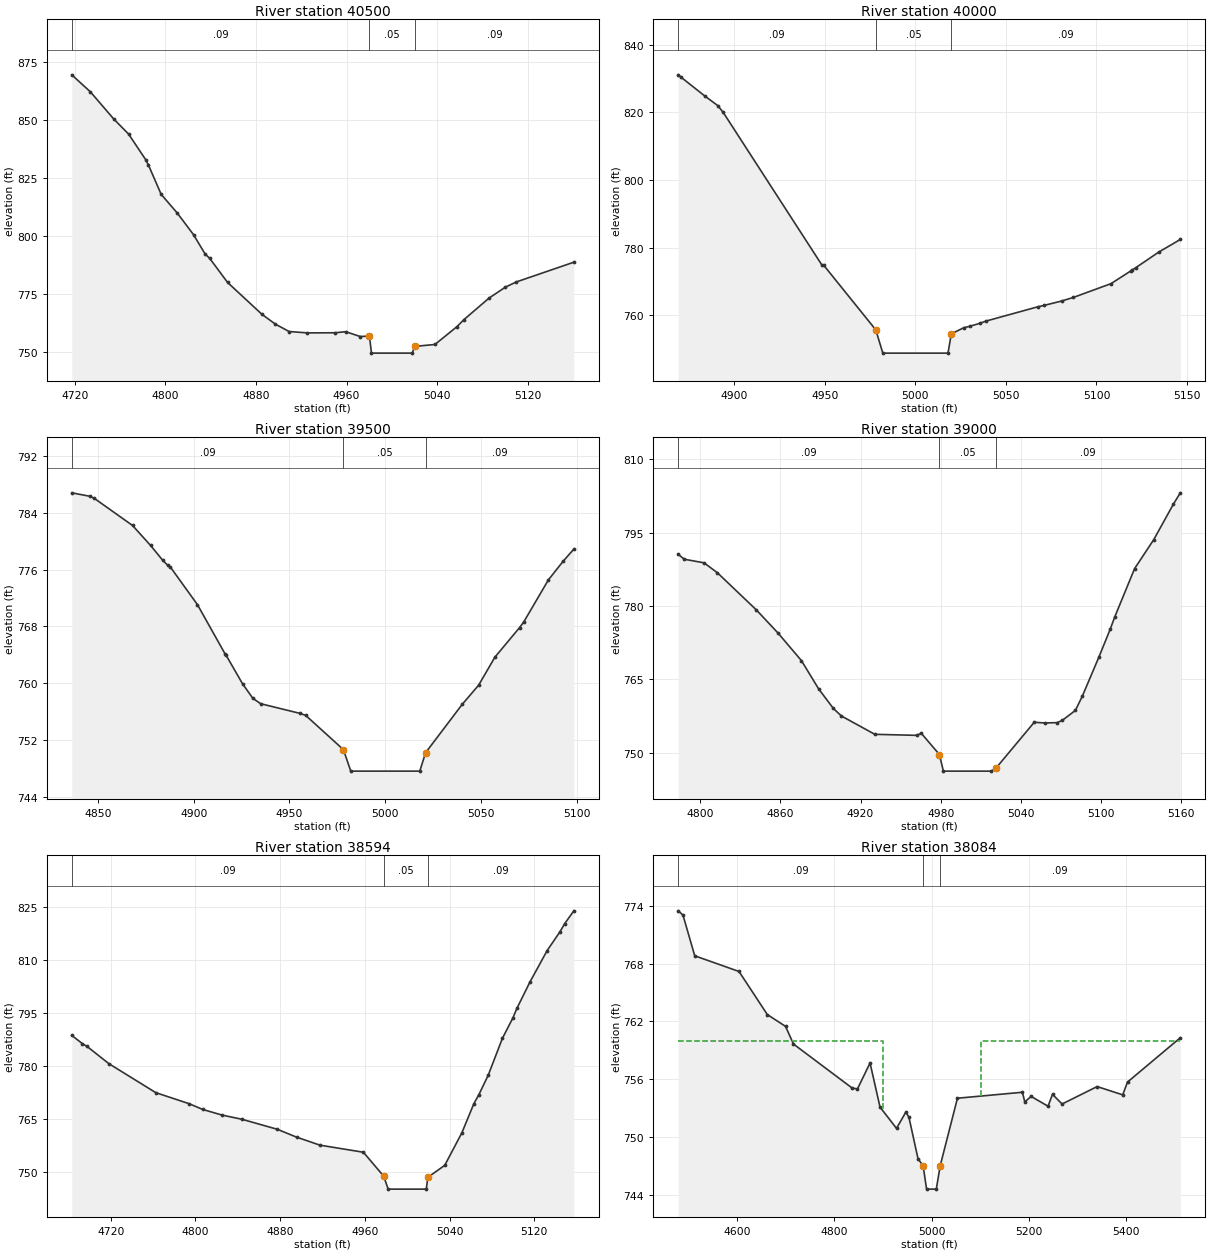
Type RM Length L Ch R = 1 ,40500   ,500,500,500
BEGIN DESCRIPTION:
Snow Creek 82.0
END DESCRIPTION:
XS GIS Cut Line= 3
      1660009.42       990130.77       1660143.9       989881.97
      1660245.65       989757.47
#Sta/Elev= 30
  4717.2  869.62  4733.6  862.32  4754.4  850.53  4767.4   844.1  4782.7  832.93
  4784.9  830.81  4796.2  818.11  4810.3  810.14  4824.8  800.74    4835  792.43
    4839  790.59  4854.9  780.15  4885.3  766.41  4897.1  762.21  4909.2  759.03
  4925.3  758.44  4949.7  758.49  4959.2  758.95  4972.1  756.87  4980.2  757.08
    4982  749.72    5018  749.72 5020.26  752.62  5038.1  753.45  5057.5  761.12
  5063.6  764.12  5085.9  773.44  5100.4  778.17  5110.1  780.41  5160.8   788.9
#Mann= 3 , 0 , 0
  4717.2     .09       0  4980.2     .05       0 5020.26     .09       0
Bank Sta=4980.2,5020.26
Exp/Cntr=0.3,0.1

Type RM Length L Ch R = 1 ,40000   ,500,500,500
BEGIN DESCRIPTION:
Snow Creek 81.0
END DESCRIPTION:
XS GIS Cut Line= 3
      1660642.29       990092.86      1660538.92        990012.3
      1660438.14       989906.21
#Sta/Elev= 25
    4869  831.14  4870.4   830.5  4883.7  824.86  4890.8  822.05  4893.8  820.05
  4948.3  774.88  4949.3  774.81  4978.1  755.65    4982  748.76    5018  748.76
 5019.81  754.46  5026.7  756.28  5029.9  756.68  5035.6  757.59    5039  758.25
  5067.5  762.46  5071.1  762.89  5080.7  764.18  5087.3  765.26    5108  769.32
    5119  773.11  5119.8   773.4  5121.7  774.05  5134.4  778.67  5146.3  782.41
#Mann= 3 , 0 , 0
    4869     .09       0  4978.1     .05       0 5019.81     .09       0
Bank Sta=4978.1,5019.81
Exp/Cntr=0.3,0.1

Type RM Length L Ch R = 1 ,39500   ,500,500,500
BEGIN DESCRIPTION:
Snow Creek 80.0
END DESCRIPTION:
XS GIS Cut Line= 3
      1660866.85       989669.97      1660744.58       989561.22
       1660662.7       989506.65
#Sta/Elev= 28
  4836.4  786.83  4845.9  786.34    4848  786.08  4868.1  782.23  4877.5  779.42
  4883.9  777.31  4886.5  776.61  4887.9  776.35    4902  771.06  4916.3  764.17
  4916.8     764  4925.5  759.92  4930.9  757.86    4935   757.1  4955.5  755.74
  4958.5  755.45 4978.15  750.63    4982   747.6    5018   747.6 5021.05   750.2
  5040.2  757.03  5048.7  759.71  5057.2  763.66  5070.1  767.84  5072.2   768.6
  5085.1  774.55  5092.8  777.18  5098.4   778.9
#Mann= 3 , 0 , 0
  4836.4     .09       0 4978.15     .05       0 5021.05     .09       0
Bank Sta=4978.15,5021.05
Exp/Cntr=0.3,0.1

Type RM Length L Ch R = 1 ,39000   ,406,406,406
BEGIN DESCRIPTION:
Snow Creek 79.0
END DESCRIPTION:
XS GIS Cut Line= 3
      1661114.75       989270.42      1660956.69       989122.61
      1660837.69       989016.69
#Sta/Elev= 30
  4783.6  790.56  4788.1  789.55  4802.9  788.82  4812.9  786.79    4842  779.21
  4858.2  774.49  4875.8  768.83  4888.6  763.08  4899.7  759.05  4905.7  757.52
  4930.7  753.77    4962  753.56  4965.5  753.98 4979.05  749.64    4982  746.25
    5018  746.25  5021.5  746.91    5050  756.24  5057.9  756.09  5067.1  756.16
    5071  756.62  5080.8  758.66    5086  761.58  5098.4  769.57  5106.8  775.22
  5110.3   777.8  5125.1  787.64  5139.4  793.54    5154  800.75  5159.3  803.12
#Mann= 3 , 0 , 0
  4783.6     .09       0 4979.05     .05       0  5021.5     .09       0
Bank Sta=4979.05,5021.5
Exp/Cntr=0.3,0.1

Type RM Length L Ch R = 1 ,38594   ,510,510,510
BEGIN DESCRIPTION:
Snow Creek 78.0
END DESCRIPTION:
XS GIS Cut Line= 3
      1661298.49       989290.84      1661310.15       988975.86
      1661289.74       988818.37
#Sta/Elev= 30
  4683.3  788.63  4693.4  786.28  4697.8  785.49  4718.4  780.62  4762.7  772.43
  4793.8  769.35    4807  767.69  4824.8  766.13  4844.3  764.89  4877.5  762.07
  4895.5  759.87  4917.6   757.6  4958.6   755.6 4977.76  748.84    4982  745.17
    5018  745.17 5019.46   748.5  5035.4  751.89  5051.6   761.1  5062.9  769.32
  5067.7  771.91  5076.5   777.4  5089.9  787.83  5099.8  793.59  5103.5  796.24
  5115.9  803.75  5132.1  812.61  5144.3  817.96  5148.6   820.2  5157.3  823.84
#Mann= 3 , 0 , 0
  4683.3     .09       0 4977.76     .05       0 5019.46     .09       0
Bank Sta=4977.76,5019.46
Exp/Cntr=0.5,0.3

Type RM Length L Ch R = 1 ,38084   ,94,94,94
BEGIN DESCRIPTION:
Moir Farm Rd. SR-1652 - US
END DESCRIPTION:
XS GIS Cut Line= 6
      1661519.56       989295.92      1661638.04       989257.23
      1661720.25       989170.18      1661780.71       989037.19
      1661819.39       988894.52      1661904.02        988408.5
#Sta/Elev= 30
  4479.3  773.48    4489  773.04  4513.2  768.81  4604.2  767.18  4662.3  762.71
  4699.8  761.48    4716  759.65  4836.8  755.07  4847.6  754.99  4873.4  757.68
  4893.9   753.1  4927.8  750.89    4947  752.58  4953.3  752.05    4972  747.73
  4982.5     747 4989.57  744.58 5009.53  744.58  5017.5     747    5053  754.02
 5186.46  754.64 5191.38  753.63 5204.29  754.21  5239.1  753.19  5248.3  754.42
    5268  753.42    5340  755.23  5392.6  754.37  5402.4   755.7  5510.9   760.3
#Mann= 3 , 0 , 0
  4479.3     .09       0  4982.5     .05       0  5017.5     .09       0
#XS Ineff= 2 , 0
       0    4899     760    5101       0     760
Permanent Ineff=
       F       F
Bank Sta=4982.5,5017.5
Exp/Cntr=0.5,0.3

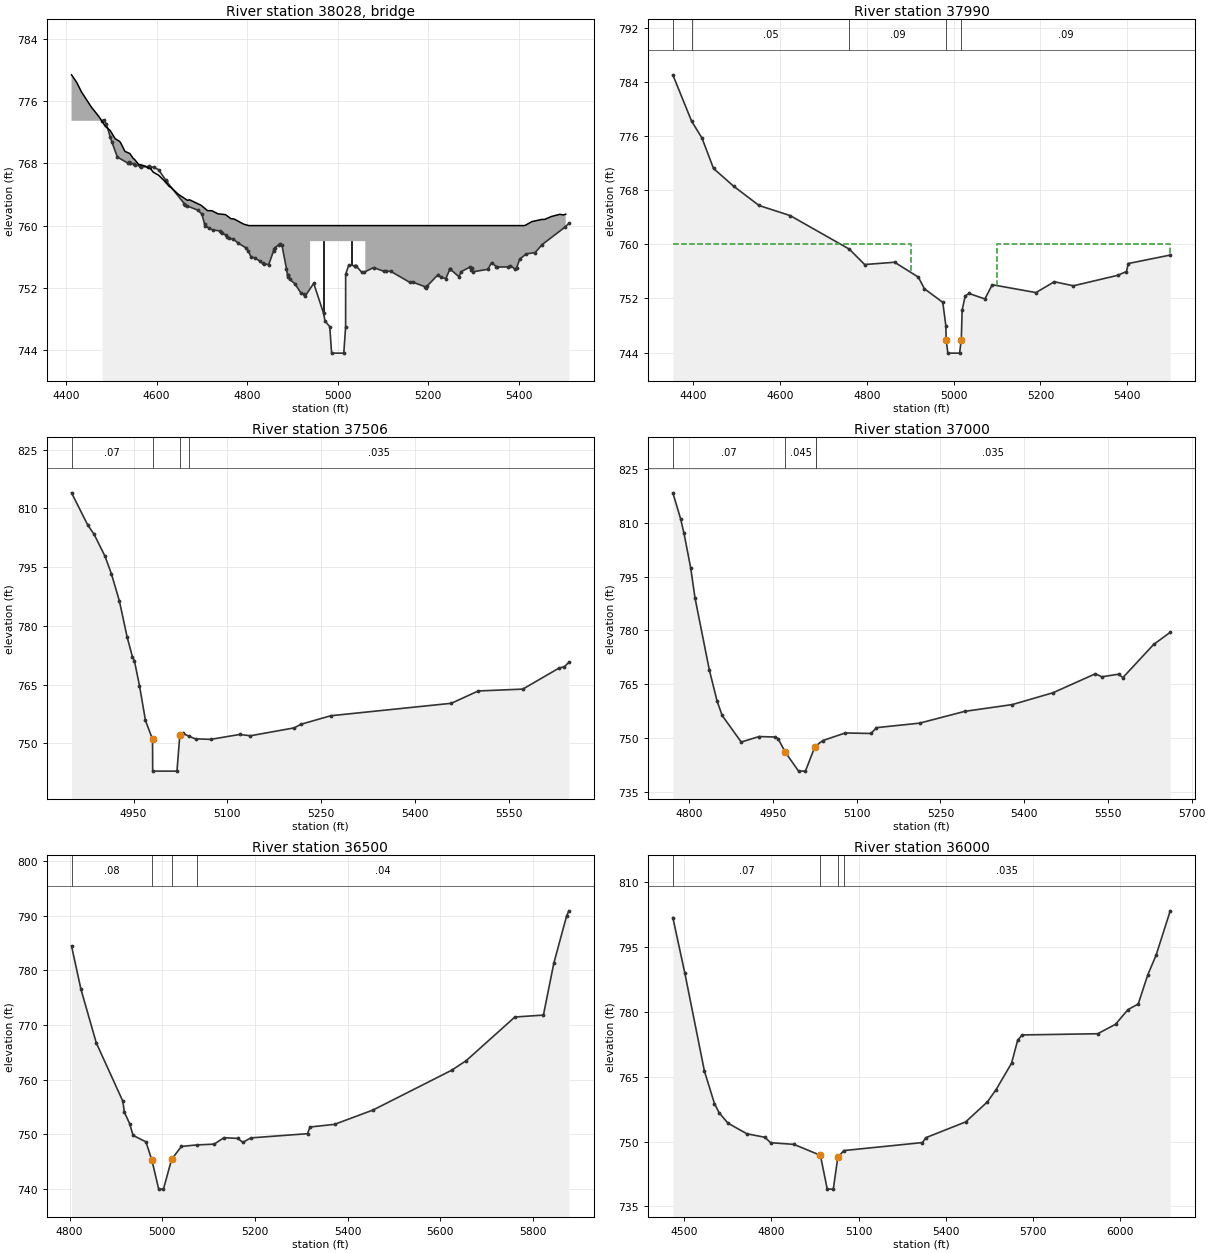
Type RM Length L Ch R = 3 ,38028   ,,,
BEGIN DESCRIPTION:
Moir Farm Rd. SR-1652
Structure ID: Moir Farm Rd - SR 1652
Approximate Survey Structure
END DESCRIPTION:
Bridge Culvert--1,0,-1,-1, 0
Deck Dist Width WeirC Skew NumUp NumDn MinLoCord MaxHiCord MaxSubmerge Is_Ogee
20,32,3,0, 47, 47, , , , 0, 1,1,,
  4411.9  4423.2  4433.9  4455.2  4472.8  4486.6  4497.2  4508.2  4518.1  4520.1
    4530  4540.7  4548.7  4550.9  4560.1  4571.6  4586.8  4592.6  4604.2  4618.1
  4627.3  4632.1  4647.3    4668  4672.7  4698.5  4712.2  4722.2  4735.2  4752.1
  4764.2  4771.1  4792.5  4803.9    4939    4939    5061    5061  5411.4  5414.6
  5429.3  5451.7  5456.9  5472.2  5490.7  5498.8  5503.7
  779.39  778.43  777.19  775.28  773.99  772.76  772.24  771.18  770.83  770.68
  769.54  769.27  768.61  768.53  767.87  767.72   767.3  766.86  766.48   765.7
  765.06  764.88  764.05  763.25  763.32   762.6  761.93  761.91  761.52  761.41
  760.89  760.85  760.18     760     760     760     760     760     760  760.04
  760.52   760.8  760.79  761.17  761.45  761.37  761.47
  724.18  724.18  724.18  724.18  724.18  724.18  724.18  724.18  724.18  724.18
  724.18  724.18  724.18  724.18  724.18  724.18  724.18  724.18  724.18  724.18
  724.18  724.18  724.18  724.18  724.18  724.18  724.18  724.18  724.18  724.18
  724.18  724.18  724.18  724.18  724.18     758     758  724.18  724.18  724.18
  724.18  724.18  724.18  724.18  724.18  724.18  724.18
  4411.9  4423.2  4433.9  4455.2  4472.8  4486.6  4497.2  4508.2  4518.1  4520.1
    4530  4540.7  4548.7  4550.9  4560.1  4571.6  4586.8  4592.6  4604.2  4618.1
  4627.3  4632.1  4647.3    4668  4672.7  4698.5  4712.2  4722.2  4735.2  4752.1
  4764.2  4771.1  4792.5  4803.9    4939    4939    5061    5061  5411.4  5414.6
  5429.3  5451.7  5456.9  5472.2  5490.7  5498.8  5503.7
  779.39  778.43  777.19  775.28  773.99  772.76  772.24  771.18  770.83  770.68
  769.54  769.27  768.61  768.53  767.87  767.72   767.3  766.86  766.48   765.7
  765.06  764.88  764.05  763.25  763.32   762.6  761.93  761.91  761.52  761.41
  760.89  760.85  760.18     760     760     760     760     760     760  760.04
  760.52   760.8  760.79  761.17  761.45  761.37  761.47
  724.18  724.18  724.18  724.18  724.18  724.18  724.18  724.18  724.18  724.18
  724.18  724.18  724.18  724.18  724.18  724.18  724.18  724.18  724.18  724.18
  724.18  724.18  724.18  724.18  724.18  724.18  724.18  724.18  724.18  724.18
  724.18  724.18  724.18  724.18  724.18     758     758  724.18  724.18  724.18
  724.18  724.18  724.18  724.18  724.18  724.18  724.18
Pier Skew, UpSta & Num, DnSta & Num=  ,4969.5, 2 ,4969.5, 2 , 0 , 0 , 0 ,0,0
       2       2
   748.5     758
       2       2
  752.18     758
Pier Skew, UpSta & Num, DnSta & Num=  ,5030.5, 2 ,5030.5, 2 , 0 , 0 , 0 ,0,0
       2       2
  754.89     758
       2       2
   753.4     758
Abutment Skew #Up #Dn= , 2 , 2
    4939    4955
     758  751.71
    4939    4955
     758  753.19
Abutment Skew #Up #Dn= , 2 , 2
    5045    5061
  754.52     758
    5045    5061
  754.48     758
BR Coef= 1 , 1 , 0 ,1.25, 0 ,,,0.8,0,2,0,
WSPro=,,,, 1 ,,,, 0 ,,,, 0 ,,,,-1 ,-1 ,-1 , 0 , 0 , 0 , 0 , 0
BR U #Sta/Elev= 111
  4479.3  773.48  4482.9  773.59    4489  773.04  4497.4  771.38    4501  770.76
  4513.2  768.81  4537.5     768  4539.2  768.15  4540.1  768.05  4540.9  767.99
  4550.7  767.95  4552.3  767.79  4562.2  767.68  4565.6  767.56  4581.6  767.58
  4583.2  767.66  4584.6  767.57    4594  767.51  4604.2  767.18  4620.6  765.81
  4621.1  765.79  4621.7  765.69  4661.2  762.81  4662.3  762.71  4666.9  762.54
  4691.2  761.98  4699.8  761.48  4706.1  760.15  4707.5  760.01    4716  759.65
  4723.6  759.45    4740  759.31  4741.7  759.18  4745.2  759.01  4752.6  758.79
  4754.9  758.54  4759.5  758.37  4769.7  758.24  4780.7  757.72  4797.4  757.13
  4802.1  756.75  4808.5  755.98  4816.8  755.84  4828.9   755.4  4834.5  755.13
  4836.8  755.07  4847.6  754.99  4858.6  756.78  4860.3  756.96  4862.1  757.18
  4869.7  757.54  4873.4  757.68  4876.7   757.5  4886.8  754.45  4889.1  753.67
    4890  753.61    4891  753.42  4893.9   753.1  4905.5  752.51  4918.5  751.35
  4925.3  751.15  4927.8  750.89    4947  752.58  4968.8  748.72    4972  747.73
  4982.5     747  4986.5   743.6  5013.5   743.6  5017.5     747  5017.6  753.74
  5024.6  754.94  5037.6  754.83  5038.8  754.86  5041.2  754.76    5053  754.02
  5057.1  753.97  5079.4   754.6  5103.1   754.1  5106.2  754.12  5117.1  754.12
    5159  752.71    5167  752.71  5193.2  752.13  5195.8     752  5197.5  752.22
  5222.2  753.71  5228.1  753.34  5239.1  753.19  5247.9   754.4  5248.3  754.42
  5248.8  754.39    5268  753.42  5273.1  754.09    5292  754.65  5295.2  754.29
  5296.8  754.56  5298.2  754.05  5331.8  754.38    5340  755.23  5350.8  754.71
  5352.4  754.67  5376.4  754.69  5381.5  754.86  5392.6  754.37  5395.2  754.56
  5402.4   755.7  5416.8  756.36  5436.3  756.53  5451.6  757.55  5502.1   759.8
  5510.9   760.3
BR U #Mann= 3
  4479.3     .09  4982.5     .05  5017.5     .09
BR D #Sta/Elev= 124
  4352.5  785.02  4361.3  783.33  4369.6  782.14  4371.7  781.74  4383.3  779.73
  4385.4  779.68  4388.3   779.4  4395.8  778.17  4401.5  777.23  4408.8  776.27
  4415.7  776.16  4419.6   775.7  4429.6  773.85    4438  772.82  4446.3  771.19
  4449.5  771.04    4452   770.8  4463.9  770.15  4471.6  769.89  4481.1  769.22
  4488.6  768.87    4493  768.56  4501.4   768.2  4505.2  767.99  4526.6  767.26
    4549  765.93  4551.2  765.73  4574.1  765.54  4578.6  765.41  4586.3  764.96
  4590.8  764.83  4596.5   764.8  4606.2  764.16  4623.2  764.23    4633  763.79
  4635.3  763.75  4656.2  763.02  4675.6  762.43  4679.5  762.22  4693.5  761.08
    4701  760.88  4708.7  760.77  4724.8  760.25  4726.3  760.16    4737  759.69
  4746.9  759.38  4752.2  759.29  4759.4  759.28  4760.4  759.28  4775.2  758.16
  4781.7  757.55  4782.1  757.52  4788.4  757.37  4794.7  757.01    4800  757.08
  4805.5     757  4810.3  756.87  4828.6  756.84  4836.5  757.02  4850.4  756.95
  4863.8  757.35  4888.8  755.64  4902.4   755.7  4910.3  755.34  4918.5  755.15
    4935  754.53    4936  754.46  4936.8  754.38    4967  752.54  4974.8  751.43
  4981.9  747.96  4982.5  745.93  4986.5     744  5013.5     744  5017.5  745.93
  5019.4  750.28  5025.8  752.96  5038.8  754.19  5039.3  754.23  5040.6  754.41
    5043  754.42    5055  754.77  5070.2  754.82    5085  754.26  5085.5  754.24
  5085.7  754.24    5101  753.88  5116.4  753.83  5128.7  753.66  5131.8  753.69
  5146.3   753.3  5149.4  753.28  5159.7  753.38  5181.9  752.88  5189.6  752.87
  5202.4  753.22  5211.2  753.25  5217.5  753.35  5223.1  753.67  5231.9  754.47
  5242.8  753.92  5246.8  753.95  5270.3  753.82  5275.9  753.87  5294.8  754.29
  5316.6  754.55  5329.8  754.56  5347.9  754.85  5365.3  755.39  5368.2  755.37
  5378.1  755.42  5398.3  755.98  5404.1  756.24  5415.4  756.25  5417.2  756.33
    5423  756.38  5430.2  756.58  5443.2  756.82  5453.1  757.15  5456.1  757.28
  5473.5   757.7  5485.6  757.83  5494.7  758.15  5499.1  758.41
BR D #Mann= 5
  4352.5     .09  4395.8     .05  4759.4     .09  4982.5     .05  5017.5     .09
BC Design=,, 0 ,, 0 ,,,,,,
BC HTab HWMax=773.59

Type RM Length L Ch R = 1 ,37990   ,484,484,484
BEGIN DESCRIPTION:
Moir Farm Rd. SR-1652 - DS
END DESCRIPTION:
XS GIS Cut Line= 6
      1661550.99       989382.97      1661683.98       989332.19
      1661824.23       989252.39      1661877.43       989138.75
      1661901.61       988954.97      1662003.16       988432.68
#Sta/Elev= 30
  4352.5  785.02  4395.8  778.17  4419.6   775.7  4446.3  771.19    4493  768.56
  4551.2  765.73  4623.2  764.23  4759.4  759.28  4794.7  757.01  4863.8  757.35
  4918.5  755.15 4932.45  753.43  4974.8  751.43  4981.9  747.96  4982.5  745.93
  4986.5  743.93  5013.5  743.93  5017.5  745.93  5019.4  750.28 5026.56  752.39
 5035.28  752.74 5071.88  751.93 5088.86  754.03  5189.6  752.87  5231.9  754.47
  5275.9  753.87  5378.1  755.42  5398.3  755.98 5402.38  757.16  5499.1  758.41
#Mann= 5 ,-1 , 0
  4352.5     .09       0  4395.8     .05       0  4759.4     .09       0
  4982.5     .05       0  5017.5     .09       0
#XS Ineff= 2 , 0
       0  4902.5     760    5100       0     760
Permanent Ineff=
       F       F
Bank Sta=4982.5,5017.5
Exp/Cntr=0.5,0.3

Type RM Length L Ch R = 1 ,37506   ,506,506,506
BEGIN DESCRIPTION:
Snow Creek 76.0
END DESCRIPTION:
XS GIS Cut Line= 5
      1662438.41       988785.71      1662358.61       988727.68
      1662264.31       988669.65      1662121.65       988534.24
      1661904.02       988212.64
#Sta/Elev= 30
    4851  813.95  4877.1  805.67  4886.8  803.43  4904.4  797.79  4914.6  793.31
  4927.4  786.35  4939.8  777.13  4948.2  772.12  4951.4  771.06  4959.5  764.74
  4969.1  755.82  4980.4     751  4980.6  742.89  5019.4  742.89  5023.9  751.99
  5028.3  752.58  5039.1  751.75    5049  751.14  5073.3     751  5119.4  752.25
  5136.7  751.92  5207.1  753.95  5216.9  754.83  5264.9  757.03  5457.6  760.21
  5500.6  763.36  5571.7  763.83  5629.6   769.2  5638.2  769.56  5645.4  770.69
#Mann= 4 ,-1 , 0
    4851     .07       0  4980.4    .045       0  5023.9     .07       0
  5039.1    .035       0
Bank Sta=4980.4,5023.9
Exp/Cntr=0.3,0.1

Type RM Length L Ch R = 1 ,37000   ,500,500,500
BEGIN DESCRIPTION:
Snow Creek 75.0
END DESCRIPTION:
XS GIS Cut Line= 3
       1662772.1       988333.54      1662554.86       988260.88
      1661918.53       988079.65
#Sta/Elev= 30
  4770.9   818.3  4784.7  811.14  4790.9  807.02  4802.9  797.37  4810.6  789.05
  4836.2  769.03  4850.3  760.24  4859.3  756.32  4893.3  748.93 4925.49  750.46
  4953.5  750.32 4959.34  749.89  4972.5  746.05 4996.11  740.83 5008.36  740.83
 5025.29  747.63  5039.3  749.33 5079.57  751.45 5125.68  751.31  5135.6  752.93
  5212.9  754.19  5293.7  757.47    5379  759.36  5451.9  762.66  5527.6  767.93
  5539.1  767.09  5569.1  767.81  5576.8  766.86  5631.9  776.09  5661.6  779.47
#Mann= 4 ,-1 , 0
  4770.9     .07       0  4972.5    .045       0  5027.1     .07       0
  5027.3    .035       0
Bank Sta=4972.5,5025.29
Exp/Cntr=0.3,0.1

Type RM Length L Ch R = 1 ,36500   ,500,500,500
BEGIN DESCRIPTION:
Snow Creek 74.0
END DESCRIPTION:
XS GIS Cut Line= 4
      1662984.89       987997.43      1662837.28       987868.99
      1662675.38       987770.14      1661995.91       987663.75
#Sta/Elev= 30
  4804.3  784.44  4824.7   776.5  4857.7  766.73  4914.9  756.09 4918.25  754.07
 4929.64  751.99 4937.09  749.83 4964.88  748.64 4977.84  745.25 4992.37  740.01
 5002.58  740.01  5020.3  745.48 5041.36  747.81 5074.82  748.09 5112.11  748.23
  5133.1  749.41 5162.69  749.28    5174  748.56 5190.98  749.37  5313.4  750.14
 5318.75  751.36 5371.88  751.85  5454.9  754.47  5624.1  761.72  5655.6  763.47
  5760.8  771.46  5822.4  771.81  5844.8  781.28  5872.5  789.96  5877.4  790.86
#Mann= 4 ,-1 , 0
  4804.3     .08       0 4977.84     .05       0  5020.3     .08       0
 5074.82     .04       0
Bank Sta=4977.84,5020.3
Exp/Cntr=0.3,0.1

Type RM Length L Ch R = 1 ,36000   ,1410,1410,1410
BEGIN DESCRIPTION:
Snow Creek 73.0
END DESCRIPTION:
XS GIS Cut Line= 6
       1663161.4        987912.8      1663070.11       987529.17
      1662983.81       987412.08      1662838.38       987256.59
      1662542.39       986877.89      1662109.56       986669.93
#Sta/Elev= 30
  4460.2  801.76  4501.5  788.94    4569  766.29  4603.6  758.78  4619.8  756.65
  4650.2  754.25  4715.3   751.8  4777.6  750.99 4796.99  749.74 4877.39  749.35
  4968.6  746.82 4992.21  739.01 5013.02  739.01  5028.5  746.33 5049.04  747.92
 5320.18  749.77    5332   750.9  5468.9  754.54  5543.5  759.14  5573.5  761.97
    5627  768.09  5648.2  773.41  5663.8  774.64    5924  774.92  5985.4   777.1
  6028.3   780.5  6063.5  781.78  6096.5  788.53  6125.1  793.06  6173.8  803.32
#Mann= 4 ,-1 , 0
  4460.2     .07       0  4968.6     .05       0  5028.5     .07       0
 5049.04    .035       0
Bank Sta=4968.6,5028.5
Exp/Cntr=0.3,0.1

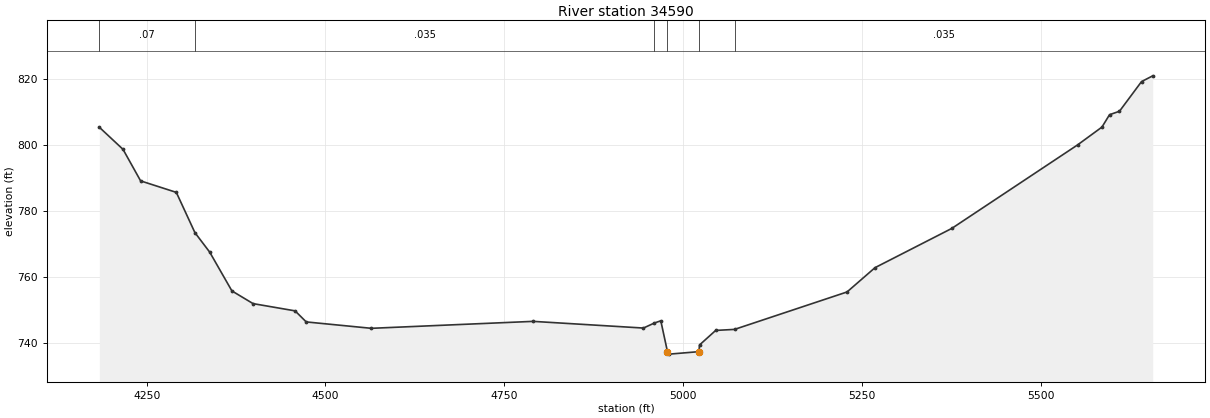
Type RM Length L Ch R = 1 ,34590   ,590,590,590
BEGIN DESCRIPTION:
Snow Creek 71.0
END DESCRIPTION:
XS GIS Cut Line= 4
      1663635.03       987680.37      1663644.75       986924.17
      1663733.43       986752.19      1664069.33        986351.8
#Sta/Elev= 30
  4183.9  805.41    4217   798.7  4241.6  789.12  4291.5  785.63  4317.5   773.4
  4338.2  767.47  4369.2   755.7  4398.8  751.84  4457.5  749.64  4473.1  746.28
  4564.1  744.34  4790.2  746.45  4944.4  744.42  4959.8  745.96  4968.7  746.62
    4978  737.25  4980.5   736.5    5022  737.25  5022.8  739.28  5045.4   743.7
  5071.7  744.01    5229  755.38  5268.1  762.76  5375.4  774.68  5551.2  800.04
  5585.3  805.46  5595.9  809.22  5609.8  810.27  5640.6  819.27  5656.3  821.03
#Mann= 6 ,-1 , 0
  4183.9     .07       0  4317.5    .035       0  4959.8     .09       0
    4978     .05       0    5022     .09       0  5071.7    .035       0
Bank Sta=4978,5022
Exp/Cntr=0.3,0.1