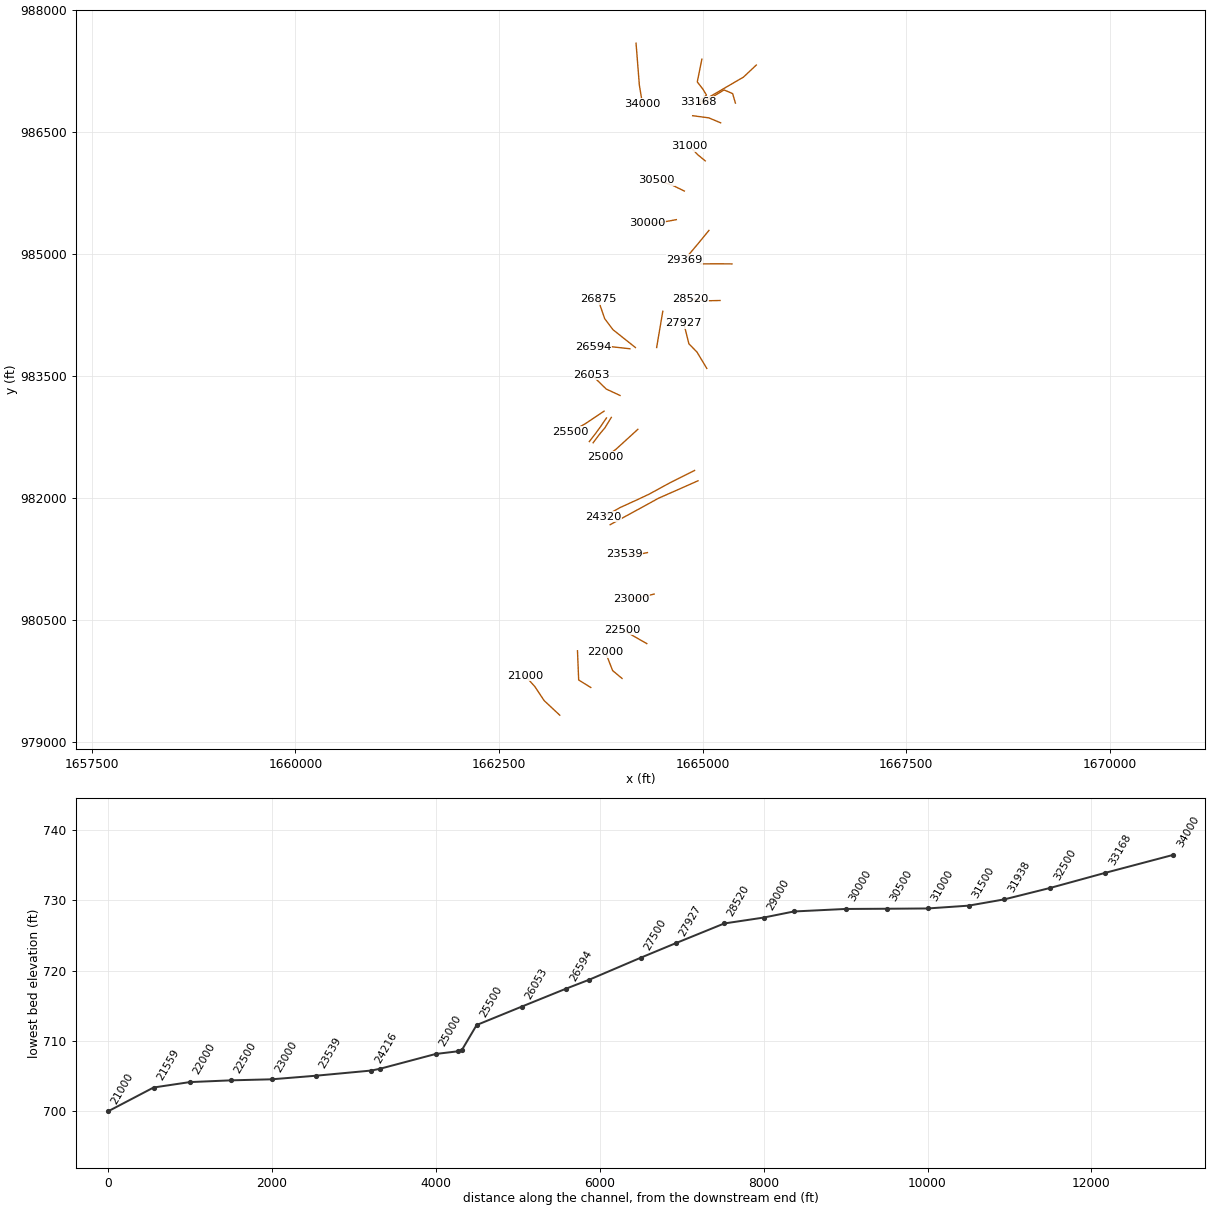
HEC-RAS study lds_snow_crk.prj: Snow Creek Limited Detail Study

--- lds_snow_crk.g02 (geometry) --- (continued)

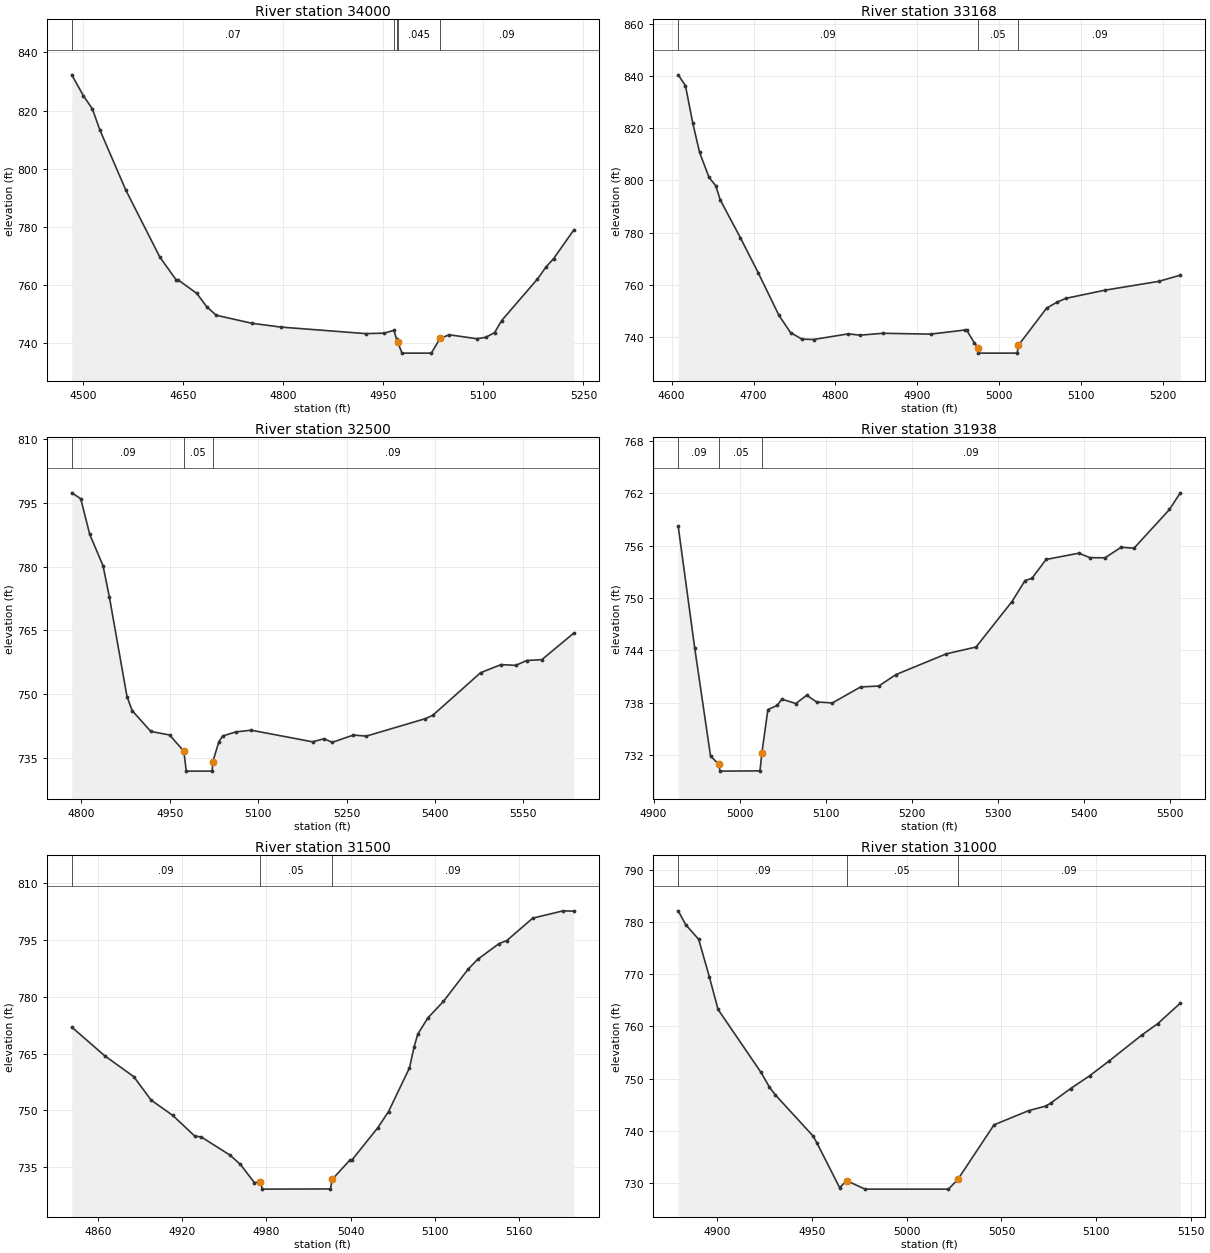
Type RM Length L Ch R = 1 ,34000   ,832,832,832
BEGIN DESCRIPTION:
Snow Creek 69.0
END DESCRIPTION:
XS GIS Cut Line= 3
      1664183.25       987587.05      1664224.03       987071.52
      1664262.59       986838.97
#Sta/Elev= 30
  4482.9  832.29  4500.3   825.1  4513.9  820.53  4524.8  813.44  4563.8  792.69
  4614.9  769.58  4639.3  761.76    4642  761.77  4670.5  757.04  4685.2  752.49
  4699.5  749.55    4753  746.78  4796.2  745.48  4923.6  743.23  4951.2  743.38
  4965.8  744.35  4969.9  741.41  4971.9   740.2    4978  736.51    5022  736.51
  5035.4  741.65    5049  742.82  5090.2  741.47  5103.7  741.95  5116.9  743.59
  5127.5  747.73  5181.2  762.03    5194  766.17  5205.3  769.02  5235.7  778.93
#Mann= 5 ,-1 , 0
  4482.9     .07       0  4965.8    .035       0  4969.9     .08       0
  4971.9    .045       0  5035.4     .09       0
Bank Sta=4971.9,5035.4
Exp/Cntr=0.3,0.1

Type RM Length L Ch R = 1 ,33168   ,668,668,668
BEGIN DESCRIPTION:
Snow Creek 67.0
END DESCRIPTION:
XS GIS Cut Line= 5
      1664991.78       987390.58       1664935.1         987111.
      1665003.11        987024.1      1665048.45       986948.54
      1664946.44        986869.2
#Sta/Elev= 30
  4608.1  840.38  4616.9  836.25  4625.9  821.85  4634.2  810.68  4645.7  801.15
  4653.9  797.97  4659.4  792.54  4684.1     778  4705.9  764.59    4731  748.42
  4745.2  741.81    4759   739.3  4773.3  739.15  4815.7  741.31  4830.1  740.81
  4858.1  741.53  4916.4  741.21  4958.5   742.8  4960.3  742.72  4969.8  737.76
  4974.4  736.08  4974.7  733.94    5022  733.94 5023.34   736.9  5057.8  751.14
  5070.6  753.44  5081.4  754.89  5128.8     758  5194.9   761.4  5221.1  763.75
#Mann= 3 , 0 , 0
  4608.1     .09       0  4974.4     .05       0 5023.34     .09       0
Bank Sta=4974.4,5023.34
Exp/Cntr=0.3,0.1

Type RM Length L Ch R = 1 ,32500   ,562,562,562
BEGIN DESCRIPTION:
Snow Creek 66.0
END DESCRIPTION:
XS GIS Cut Line= 3
      1665660.51        987318.8      1665503.11       987170.51
      1664953.99       986850.31
#Sta/Elev= 30
  4783.7  797.41  4798.9  796.02  4814.2  787.61  4836.8  780.21  4847.6  772.79
  4877.4  749.39  4886.2  746.07  4917.8  741.16  4949.8  740.32  4973.9  736.48
    4978   731.8    5022   731.8  5022.9  733.96  5033.4  738.77    5040   740.1
    5062  741.04  5088.2  741.45  5192.4  738.71  5211.6  739.43  5225.8  738.59
  5261.7  740.31  5283.5  740.05  5383.5  744.16  5396.4  744.97  5477.4     755
  5512.2  756.92    5537  756.73  5555.8  757.88  5581.4  758.08  5635.7  764.35
#Mann= 3 , 0 , 0
  4783.7     .09       0  4973.9     .05       0  5022.9     .09       0
Bank Sta=4973.9,5022.9
Exp/Cntr=0.3,0.1

Type RM Length L Ch R = 1 ,31938   ,438,438,438
BEGIN DESCRIPTION:
Snow Creek 65.0
END DESCRIPTION:
XS GIS Cut Line= 4
       1665403.6       986850.31      1665369.59       986967.43
       1665263.8       987012.77      1664969.11       986831.41
#Sta/Elev= 30
  4928.7  758.21  4947.8   744.3  4966.2  731.89 4975.77  730.95  4977.3  730.16
  5023.6  730.19 5025.82  732.26  5032.8  737.21  5043.5  737.69    5049  738.41
  5065.3  737.91  5077.9  738.86  5089.4  738.09  5107.7  737.98  5140.4  739.81
  5161.6  739.92  5181.5  741.23  5240.1  743.61  5274.5  744.39  5316.2   749.6
  5331.4  752.01  5339.5  752.28  5355.8  754.43  5393.9  755.15  5406.6  754.64
  5424.2  754.62    5443  755.83  5457.9  755.72  5499.1  760.16  5511.7  762.07
#Mann= 3 , 0 , 0
  4928.7     .09       0 4975.77     .05       0 5025.82     .09       0
Bank Sta=4975.77,5025.82
Exp/Cntr=0.3,0.1

Type RM Length L Ch R = 1 ,31500   ,500,500,500
BEGIN DESCRIPTION:
Snow Creek 64.0
END DESCRIPTION:
XS GIS Cut Line= 3
      1665222.24        986608.5       1665075.8       986669.68
      1664878.43        986695.4
#Sta/Elev= 30
  4841.3  771.99  4864.7  764.45  4885.5  758.92  4897.8  752.75  4913.3  748.69
  4928.9  743.26  4933.6  743.01  4953.9  738.26  4961.5  735.76  4971.4  730.97
 4975.57  731.17  4977.1  729.26  5025.6  729.31  5026.8  731.81  5039.3  736.86
  5040.9  736.95  5059.3  745.44    5067  749.73  5081.9  761.24  5085.2  766.79
  5087.8  770.13    5095  774.42  5106.1  778.78  5123.7  787.28  5130.5  789.87
  5145.6  793.99  5151.2  794.81  5169.7  800.73  5191.4  802.66    5199  802.57
#Mann= 3 , 0 , 0
  4841.3     .09       0 4975.57     .05       0  5026.8     .09       0
Bank Sta=4975.57,5026.8
Exp/Cntr=0.3,0.1

Type RM Length L Ch R = 1 ,31000   ,500,500,500
BEGIN DESCRIPTION:
Snow Creek 63.0
END DESCRIPTION:
XS GIS Cut Line= 3
      1665033.34       986140.01      1664940.44       986216.94
      1664840.65       986321.36
#Sta/Elev= 25
  4879.4   782.1  4883.3  779.47  4890.2  776.64  4895.8  769.49  4900.4  763.25
    4923  751.24  4927.5  748.41  4930.5  746.95  4950.7  738.97  4952.7  737.63
  4964.6  729.13 4968.27  730.48    4978  728.86    5022  728.86 5026.96  730.71
  5046.1  741.17  5064.4  743.88  5073.5  744.76    5076  745.32  5086.5   748.1
  5096.5  750.53  5106.8  753.37  5124.4  758.43  5132.4  760.49  5144.4  764.44
#Mann= 3 , 0 , 0
  4879.4     .09       0 4968.27     .05       0 5026.96     .09       0
Bank Sta=4968.27,5026.96
Exp/Cntr=0.3,0.1

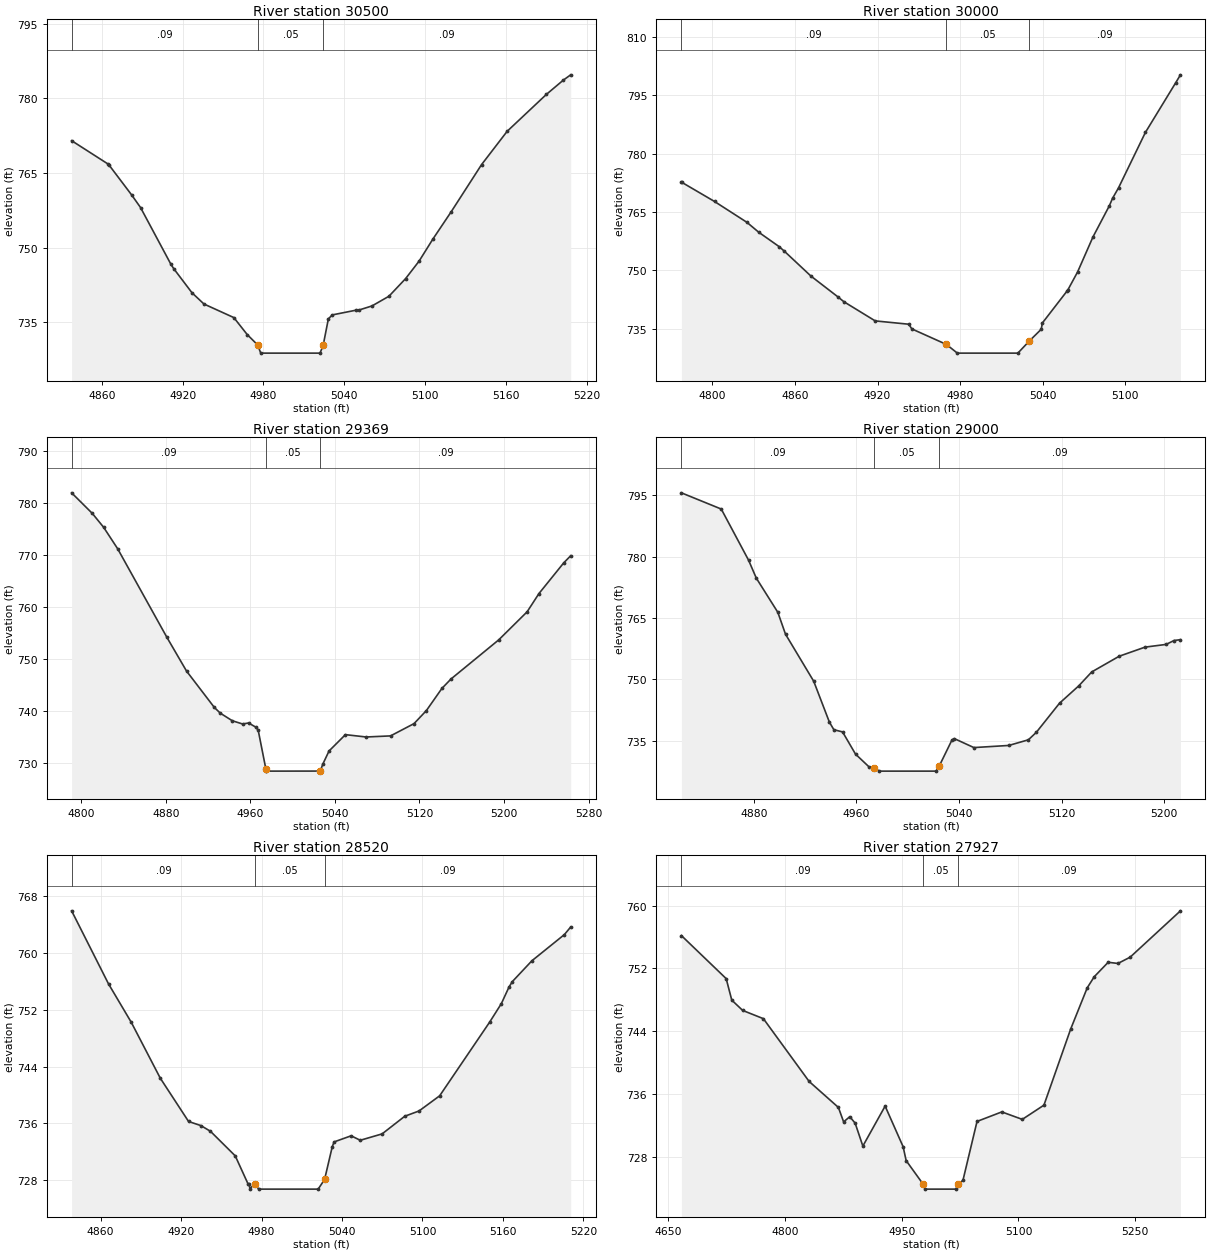
Type RM Length L Ch R = 1 ,30500   ,500,500,500
BEGIN DESCRIPTION:
Snow Creek 62.0
END DESCRIPTION:
XS GIS Cut Line= 3
      1664776.42       985769.75      1664630.55       985841.28
      1664432.61       985905.76
#Sta/Elev= 30
  4837.5  771.51  4864.6  766.81  4865.5  766.54  4882.1   760.6  4888.7  758.07
  4911.3  746.65  4913.3  745.81  4926.9  740.95  4935.8  738.69    4958  735.96
  4967.9  732.56 4975.62  730.48    4978  728.82    5022  728.82 5024.33  730.36
  5028.2   735.7  5031.1   736.5  5048.6  737.44  5050.8  737.47  5060.6   738.3
  5073.2  740.25  5085.6   743.8  5095.6  747.31  5105.7  751.68  5119.5  757.25
    5142   766.7    5161  773.39  5190.2  780.82  5202.7  783.67  5208.2  784.74
#Mann= 3 , 0 , 0
  4837.5     .09       0 4975.62     .05       0 5024.33     .09       0
Bank Sta=4975.62,5024.33
Exp/Cntr=0.3,0.1

Type RM Length L Ch R = 1 ,30000   ,631,631,631
BEGIN DESCRIPTION:
Snow Creek 61.0
END DESCRIPTION:
XS GIS Cut Line= 3
      1664678.19       985418.38      1664459.38       985377.74
      1664319.26       985373.04
#Sta/Elev= 29
  4777.4  772.67  4777.7  772.63  4801.5  767.71    4825  762.37  4833.7   759.8
  4848.4  756.14  4852.2  754.97  4871.6  748.56  4891.4  743.17  4895.5  741.99
  4918.3  737.06  4942.7  736.21  4944.9  735.01 4970.06  731.02    4978  728.79
    5022  728.79 5030.44  731.94    5039  734.92  5039.8  736.52  5057.5  744.61
  5058.3  744.99  5065.4  749.61  5076.6  758.61  5088.5  766.61  5090.8   768.5
  5095.2  771.23  5114.7  785.43  5136.8  798.22  5140.2  800.22
#Mann= 3 , 0 , 0
  4777.4     .09       0 4970.06     .05       0 5030.44     .09       0
Bank Sta=4970.06,5030.44
Exp/Cntr=0.3,0.1

Type RM Length L Ch R = 1 ,29369   ,369,369,369
BEGIN DESCRIPTION:
Snow Creek 60.0
END DESCRIPTION:
XS GIS Cut Line= 3
      1665078.67       985286.14      1664942.66        985119.9
      1664776.42       984923.44
#Sta/Elev= 30
    4791  781.91  4810.6  777.95  4821.3  775.28  4834.5  771.18  4881.1  754.15
  4899.7  747.66    4926  740.67  4931.7  739.56    4943  738.11  4952.7  737.49
  4958.4  737.68  4965.5  736.85  4967.5  736.29  4974.7  728.89  4974.8  728.43
  5026.3  728.44  5028.5  729.72  5034.5   732.3    5050  735.44  5069.6  734.99
  5092.7   735.2  5114.9  737.56  5126.6  740.07  5141.3  744.33  5149.9  746.14
    5195  753.65  5221.9  759.05  5233.1  762.56  5256.5  768.45  5263.1  769.82
#Mann= 3 , 0 , 0
    4791     .09       0  4974.7     .05       0  5026.3     .09       0
Bank Sta=4974.7,5026.3
Exp/Cntr=0.3,0.1

Type RM Length L Ch R = 1 ,29000   ,480,480,480
BEGIN DESCRIPTION:
Snow Creek 59.0
END DESCRIPTION:
XS GIS Cut Line= 3
      1665362.04       984874.32      1665185.57       984875.53
      1664972.89       984874.32
#Sta/Elev= 30
  4823.5  795.63  4854.6  791.66  4875.9  779.15  4881.9  774.78  4898.7  766.41
  4904.7  761.05  4926.7  749.54  4938.9  739.56  4942.4  737.69  4949.2  737.15
  4959.3  731.72  4969.9  728.58 4973.78  728.44  4977.8  727.56  5022.2  727.56
 5024.43  728.71  5034.5  735.17  5036.3  735.52  5051.6  733.32  5078.8  733.84
  5094.1  735.22  5100.3  737.05  5118.4  744.18  5133.3  748.39  5143.5  751.82
  5164.9  755.66  5185.1  757.89  5201.5  758.55  5207.7  759.51  5212.7  759.71
#Mann= 3 , 0 , 0
  4823.5     .09       0 4973.78     .05       0 5024.43     .09       0
Bank Sta=4973.78,5024.43
Exp/Cntr=0.3,0.1

Type RM Length L Ch R = 1 ,28520   ,593,593,593
BEGIN DESCRIPTION:
Snow Creek 58.0
END DESCRIPTION:
XS GIS Cut Line= 3
      1665214.69       984424.72      1665048.45       984420.94
      1664844.43       984447.39
#Sta/Elev= 30
  4838.4  765.97  4865.9  755.67  4882.9  750.24  4904.5  742.37  4925.6  736.26
  4934.8  735.68  4941.9  734.88  4960.4  731.41  4969.9  727.47  4970.8  727.44
  4971.3  726.79 4975.17  727.48  4977.8  726.72  5022.2  726.72 5027.01  728.08
  5032.7  732.68  5034.1  733.38  5046.8  734.24  5053.6  733.61  5069.9  734.51
  5086.8     737  5097.4  737.74  5112.8  739.88  5150.1  750.28  5158.8  752.88
  5164.5  755.22    5167  755.99  5181.6  758.93  5205.8  762.62  5210.5  763.69
#Mann= 3 , 0 , 0
  4838.4     .09       0 4975.17     .05       0 5027.01     .09       0
Bank Sta=4975.17,5027.01
Exp/Cntr=0.3,0.1

Type RM Length L Ch R = 1 ,27927   ,427,427,427
BEGIN DESCRIPTION:
Snow Creek 57.0
END DESCRIPTION:
XS GIS Cut Line= 4
      1665052.23       983589.74      1664931.08       983791.58
      1664832.31       983892.31      1664768.86       984148.91
#Sta/Elev= 30
  4667.2  756.18  4724.7   750.7  4731.9  747.96  4745.9  746.65  4772.5   745.6
  4831.2  737.61  4868.8   734.3  4875.5  732.46  4883.4  733.12  4890.3   732.3
  4900.2  729.38  4928.8  734.47  4951.9   729.3  4955.8  727.53  4977.8   724.5
  4980.3   723.9  5019.7   723.9  5022.2   724.5  5028.7  725.01  5046.8  732.52
  5078.6  733.73  5104.9  732.78  5132.7  734.59    5167  744.27  5188.3  749.53
  5197.3  750.94  5215.2  752.78  5227.7  752.63  5243.4  753.43    5308  759.33
#Mann= 3 ,-1 , 0
  4667.2     .09       0  4977.8     .05       0  5022.2     .09       0
Bank Sta=4977.8,5022.2
Exp/Cntr=0.3,0.1

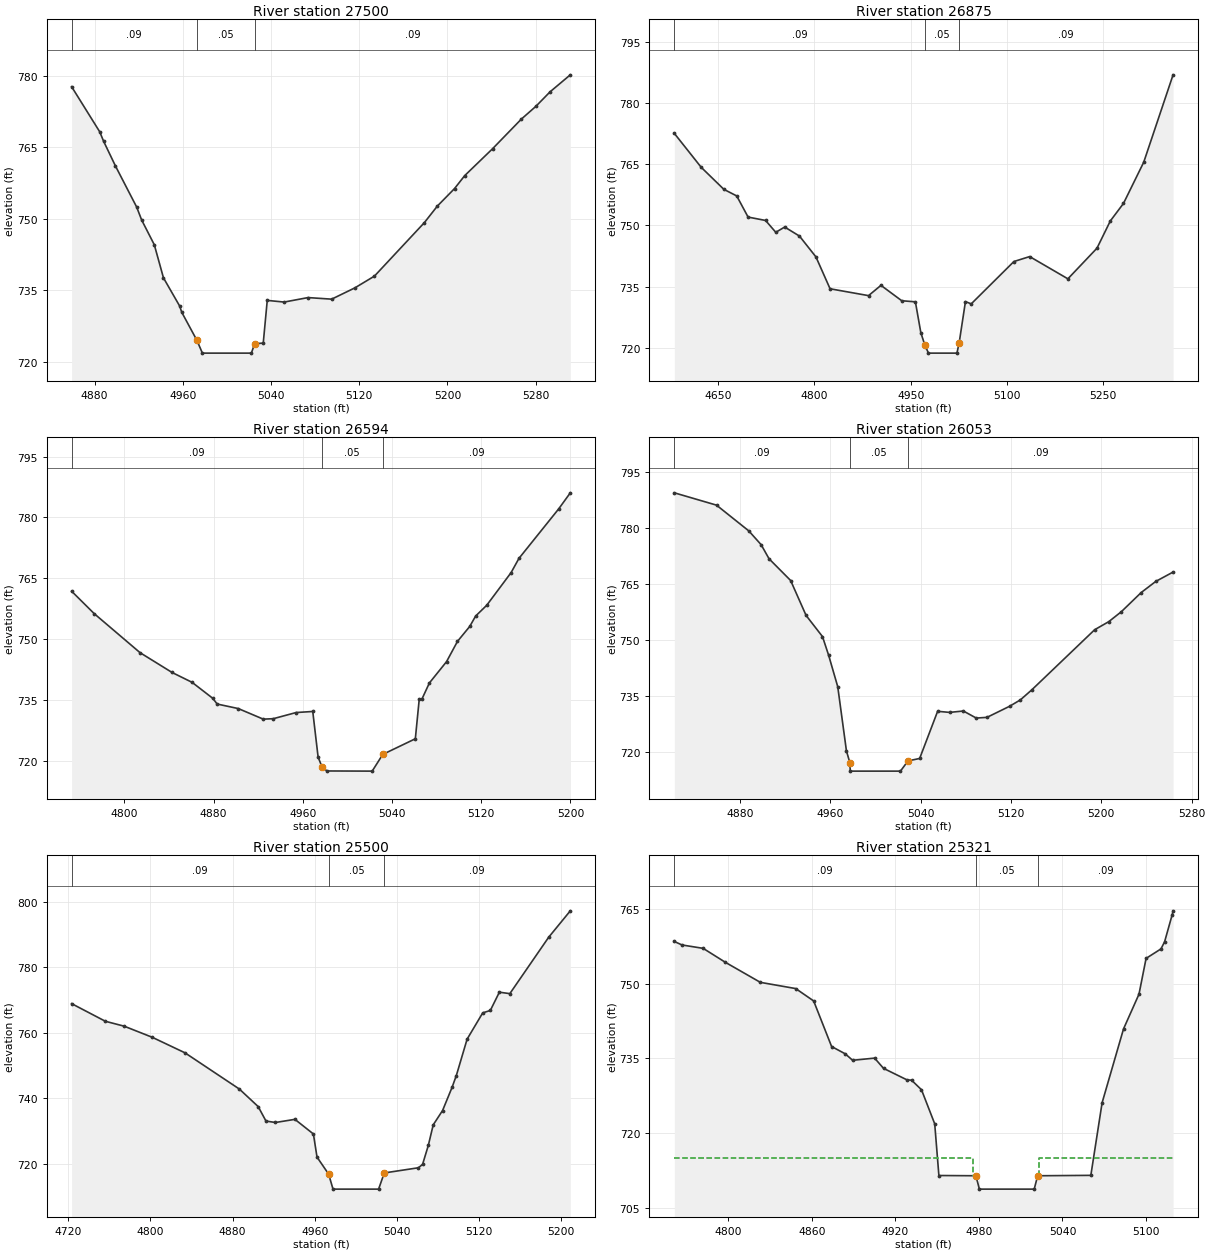
Type RM Length L Ch R = 1 ,27500   ,625,625,625
BEGIN DESCRIPTION:
Snow Creek 56.0
END DESCRIPTION:
XS GIS Cut Line= 3
      1664436.38       983846.66      1664459.64       983985.52
      1664511.95       984292.48
#Sta/Elev= 30
  4859.2  777.67  4884.7  768.21  4888.3  766.19    4899  761.03  4918.2  752.44
  4922.7  749.74  4934.2  744.53  4942.5   737.6  4957.2  731.69  4959.1  730.38
 4972.79  724.52  4977.8  721.83  5022.2  721.83 5025.22  723.81 5032.97  723.93
  5036.6  732.88  5051.9  732.53  5073.6  733.47    5095  733.14  5116.1  735.51
  5133.8  737.97    5179  749.16  5190.9  752.66  5206.4  756.31  5215.7  759.04
  5240.9  764.66    5267  770.87  5280.1  773.53  5293.1   776.6  5311.4  780.15
#Mann= 3 , 0 , 0
  4859.2     .09       0 4972.79     .05       0 5025.22     .09       0
Bank Sta=4972.79,5025.22
Exp/Cntr=0.3,0.1

Type RM Length L Ch R = 1 ,26875   ,281,281,281
BEGIN DESCRIPTION:
Snow Creek 55.0
END DESCRIPTION:
XS GIS Cut Line= 4
      1664175.69       983846.66      1663899.88       984065.79
      1663797.87        984201.8      1663714.75       984443.61
#Sta/Elev= 30
  4581.4  772.55  4623.3  764.24  4658.6  758.85  4678.7  757.23  4696.4  752.05
  4723.7  751.22  4739.6  748.32  4753.5  749.61  4776.6  747.39  4802.3  742.28
  4824.3  734.48  4884.3   732.8  4903.7  735.32  4936.1  731.55  4957.4  731.28
  4965.9  723.72    4972  720.75  4977.8  718.71  5022.2  718.71 5025.62  721.16
  5035.5  731.34  5044.5  730.78  5111.1  741.16  5135.7  742.37  5195.3  736.92
  5240.7  744.43  5261.5   751.1    5282  755.39  5313.6  765.49  5359.4  786.91
#Mann= 3 , 0 , 0
  4581.4     .09       0    4972     .05       0 5025.62     .09       0
Bank Sta=4972,5025.62
Exp/Cntr=0.3,0.1

Type RM Length L Ch R = 1 ,26594   ,541,541,541
BEGIN DESCRIPTION:
Snow Creek 54.0
END DESCRIPTION:
XS GIS Cut Line= 3
      1664107.68       983831.54      1663865.88       983857.99
      1663661.86       983854.21
#Sta/Elev= 30
  4752.6  761.81  4772.9  756.27    4814  746.65  4842.7  741.77  4860.7  739.33
  4879.1  735.42  4883.2  733.98  4902.1  732.87  4924.5  730.26  4933.5  730.37
    4954  731.89  4968.9  732.15  4973.7  720.89 4977.06  718.57 4981.53  717.48
  5022.2  717.44 5031.68  721.56  5060.9  725.42  5064.4  735.18  5066.8   735.2
  5073.5  739.18  5088.9  744.44  5098.7  749.44  5109.7  753.12    5115  755.69
  5124.9  758.33  5146.8   766.4  5153.8  769.89  5189.5  782.12  5199.9  786.07
#Mann= 3 , 0 , 0
  4752.6     .09       0 4977.06     .05       0 5031.68     .09       0
Bank Sta=4977.06,5031.68
Exp/Cntr=0.3,0.1

Type RM Length L Ch R = 1 ,26053   ,553,553,553
BEGIN DESCRIPTION:
Snow Creek 53.0
END DESCRIPTION:
XS GIS Cut Line= 3
      1663986.78       983257.26      1663816.76        983336.6
      1663635.41       983514.18
#Sta/Elev= 30
  4822.1  789.41  4859.4  786.11    4888  779.21  4898.9  775.52  4905.9  771.75
    4925  765.93  4938.7  756.57  4953.2  750.91  4958.6  745.95  4966.7  737.49
  4974.4   720.3  4977.4  717.16  4977.8  714.88  5022.2  714.88  5028.9  717.62
  5039.2  718.27  5055.1   730.9  5065.7  730.61  5077.9  730.98  5089.3  729.09
  5098.8  729.28  5118.8  732.25  5128.3  733.95  5138.4  736.63  5194.1  752.75
  5206.6  754.91  5217.7  757.57  5235.3  762.71  5248.2  765.69  5263.5  768.19
#Mann= 3 , 0 , 0
  4822.1     .09       0  4977.4     .05       0  5028.9     .09       0
Bank Sta=4977.4,5028.9
Exp/Cntr=0.3,0.1

Type RM Length L Ch R = 1 ,25500   ,179,179,179
BEGIN DESCRIPTION:
Snow Creek 52.0
END DESCRIPTION:
XS GIS Cut Line= 3
      1663790.32       983064.57      1663560.47       982910.26
       1663378.5       982807.66
#Sta/Elev= 30
  4723.2  768.89  4756.1   763.5  4774.4     762  4801.6  758.63  4833.6  753.87
  4886.6   742.8  4904.9  737.45  4912.5  733.03  4921.7  732.59  4940.7  733.55
  4958.7  729.08  4962.2  722.03 4973.49  716.84  4977.8  712.24  5022.2  712.24
 5027.71  717.18  5060.9  718.76    5065  719.78  5070.6  725.58  5075.4  731.88
  5084.5  736.25  5093.7  743.29  5097.9  746.93  5108.4  758.05  5123.6  766.07
    5131   766.8  5139.8  772.38    5150  771.94  5187.8  789.15  5208.9  797.23
#Mann= 3 , 0 , 0
  4723.2     .09       0 4973.49     .05       0 5027.71     .09       0
Bank Sta=4973.49,5027.71
Exp/Cntr=0.5,0.3

Type RM Length L Ch R = 1 ,25321   ,45,45,45
BEGIN DESCRIPTION:
Dam - US
END DESCRIPTION:
XS GIS Cut Line= 4
      1663819.77       982981.01      1663743.17       982867.87
      1663688.36       982793.38      1663609.66       982690.79
#Sta/Elev= 30
  4761.1  758.52  4766.6  757.82  4781.8  757.14  4797.7  754.34  4822.9   750.3
  4848.3  749.05  4861.2  746.56  4874.1  737.39  4883.9  735.92  4889.2  734.62
    4905  735.06  4911.4     733  4928.2  730.69  4931.6  730.61  4938.7  728.69
  4948.2  721.84  4951.2  711.44  4977.8  711.39  4980.3   708.7  5019.7   708.7
  5022.2  711.39  5060.4  711.47  5068.5  726.08  5083.9  740.94    5095  747.92
  5100.1  755.12  5110.8  757.03  5113.4  758.46  5118.9  763.94  5119.5  764.69
#Mann= 3 ,-1 , 0
  4761.1     .09       0  4977.8     .05       0  5022.2     .09       0
#XS Ineff= 2 , 0
       0    4976     715    5023       0     715
Permanent Ineff=
       F       F
Bank Sta=4977.8,5022.2
Exp/Cntr=0.5,0.3

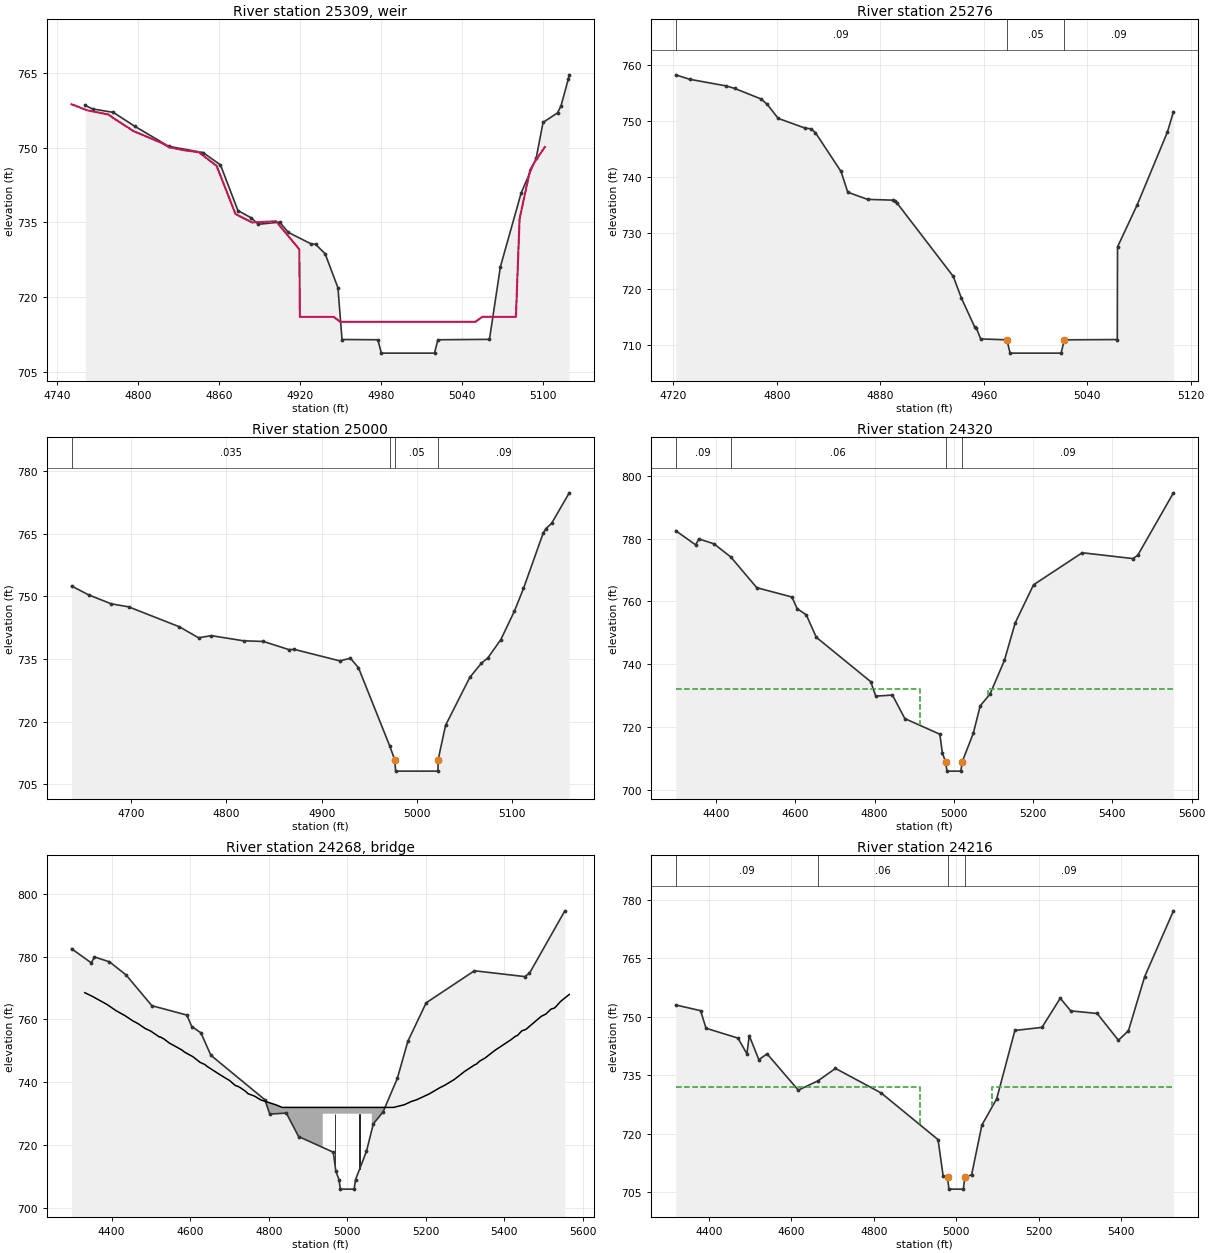
Type RM Length L Ch R = 5 ,25309   ,,,
BEGIN DESCRIPTION:
Dam
Structure ID: Dam
Approximate Survey Structure
END DESCRIPTION:
IW Pilot Flow=0
#Inline Weir SE= 24
  4750.9  758.77  4762.4  757.55  4778.2   756.7  4781.4  756.07  4796.7  753.38
  4818.1  750.93    4823  750.13  4833.9  749.53  4845.1  749.12  4858.3  746.38
  4872.3  736.69  4884.6  734.98  4902.3  735.23  4919.6  729.58    4920     716
    4945     716    4950     715    5050     715    5055     716    5080     716
  5082.7  735.68  5090.5  745.54  5094.1  747.26  5101.4  750.15
IW Dist,WD,Coef,Skew,MaxSub,Min_El,Is_Ogee,SpillHt,DesHd
7,10,3,0,0.95,, 0 ,,,1,1,

Type RM Length L Ch R = 1 ,25276   ,276,276,276
BEGIN DESCRIPTION:
Dam - DS
END DESCRIPTION:
XS GIS Cut Line= 4
       1663879.5       982988.04       1663802.2       982861.55
      1663734.74       982780.73      1663656.04       982676.03
#Sta/Elev= 30
    4722  758.31  4732.8  757.51  4760.9  756.33  4767.6  755.87    4788  753.98
  4792.8     753  4801.1  750.52  4822.1  748.76  4826.4  748.65  4829.9  747.96
  4849.7  741.01  4854.9   737.3  4870.2  736.02  4889.8  735.88  4891.4  735.75
  4892.8  735.41  4936.4  722.23  4942.7  718.34  4952.8  713.26  4954.1  713.05
  4957.6  711.04  4977.8  710.88  4980.3   708.5  5019.7   708.5  5022.2  710.88
  5063.1  710.93  5063.3  727.52  5078.6   735.1  5101.8  748.05  5106.5   751.7
#Mann= 3 ,-1 , 0
    4722     .09       0  4977.8     .05       0  5022.2     .09       0
Bank Sta=4977.8,5022.2
Exp/Cntr=0.5,0.3

Type RM Length L Ch R = 1 ,25000   ,680,680,680
BEGIN DESCRIPTION:
Snow Creek 51.0
END DESCRIPTION:
XS GIS Cut Line= 3
      1664205.92       982841.66      1663937.89       982597.08
      1663809.21       982501.63
#Sta/Elev= 30
  4637.2  752.48  4655.1  750.37  4678.8  748.22  4697.2  747.49  4750.5  742.71
  4770.6  740.08  4784.2  740.58    4818  739.35  4838.8  739.19  4865.6  737.24
  4871.3  737.29    4919  734.54  4930.3  735.17  4938.7  732.89  4971.7  714.06
  4976.7  710.89  4977.8  708.11  5022.2  708.11 5022.44  710.88  5030.2  719.08
  5055.7  730.59  5067.9  733.99  5074.7  735.26  5088.3  739.64  5102.5  746.43
  5112.1  751.89  5132.9  765.23  5135.7  766.25  5141.6  767.49  5160.2  774.82
#Mann= 4 ,-1 , 0
  4637.2    .035       0  4971.7     .09       0  4976.7     .05       0
 5022.44     .09       0
Bank Sta=4976.7,5022.44
Exp/Cntr=0.5,0.3

Type RM Length L Ch R = 1 ,24320   ,104,104,104
BEGIN DESCRIPTION:
Sheppard Mill Rd. SR-1674 - US
END DESCRIPTION:
XS GIS Cut Line= 6
      1664902.21       982336.04      1664586.55       982177.16
      1664341.97       982043.37        1664204.       981978.57
       1663984.5       981878.23      1663783.81       981765.34
#Sta/Elev= 30
  4297.9  782.49  4348.1     778  4356.3  779.88  4394.5  778.32  4436.9  774.13
  4502.4  764.37  4591.3  761.39  4604.1  757.72  4627.3  755.74  4652.7  748.59
  4790.2  734.44  4802.6  729.86  4844.8   730.2  4876.1  722.72  4964.5  717.74
  4970.8  711.77    4979     709  4982.5     706  5017.5     706    5021     709
  5048.9  718.04  5066.4  726.77  5091.1  730.53  5127.4   741.2  5154.4  753.08
  5200.9  765.28  5323.8  775.48  5451.7  773.63  5463.8  774.65  5554.1  794.55
#Mann= 4 ,-1 , 0
  4297.9     .09       0  4436.9     .06       0    4979    .045       0
    5021     .09       0
#XS Ineff= 2 , 0
       0  4913.5     732  5086.5       0     732
Permanent Ineff=
       F       F
Bank Sta=4979,5021
Exp/Cntr=0.5,0.3

Type RM Length L Ch R = 3 ,24268   ,,,
BEGIN DESCRIPTION:
Sheppard Mill Rd. SR-1674
Structure ID: Sheppard Mill Rd. SR-1674
Approximate Survey Structure
END DESCRIPTION:
Bridge Culvert--1,0,-1,-1, 0
Deck Dist Width WeirC Skew NumUp NumDn MinLoCord MaxHiCord MaxSubmerge Is_Ogee
39.5,25,3,0, 60, 60, , , , 0, 1,1,,
  4331.7  4351.9    4388  4410.9  4433.9  4452.9  4467.4  4484.9  4499.9  4521.6
    4523  4533.2  4546.7  4578.7  4585.1  4607.1  4624.9  4637.1  4643.2  4676.6
  4700.1    4715  4721.1  4728.4  4740.3  4747.6  4763.6  4779.9  4818.7  4834.3
  4937.5  4937.5  5062.5  5062.5    5118  5145.4  5162.8    5176  5208.6  5234.8
    5248  5272.4  5298.6  5324.4  5329.2  5337.2  5351.1  5376.7  5416.8  5428.4
  5433.6  5444.4    5455  5494.1  5505.7  5519.2  5526.9    5532  5542.5  5565.3
   768.5  767.26  764.77   762.8   761.2  759.62  758.63  757.14  756.26   754.4
  754.47  753.78  752.49  750.29  749.64  748.12  746.35  745.66  745.04  742.34
  740.57  738.96  738.73  738.21  737.19  736.34  735.61  734.38   732.8     732
     732     732     732     732     732  732.85  733.88   734.4  736.29  738.21
  739.03  740.87  743.43  745.55  745.79  746.74  747.73  750.22  753.53  754.65
  754.92  756.35  756.83  760.99   761.7  763.31  763.57  764.14  765.64  767.95
     686     686     686     686     686     686     686     686     686     686
     686     686     686     686     686     686     686     686     686     686
     686     686     686     686     686     686     686     686     686     686
     686     730     730     686     686     686     686     686     686     686
     686     686     686     686     686     686     686     686     686     686
     686     686     686     686     686     686     686     686     686     686
  4331.7  4351.9    4388  4410.9  4433.9  4452.9  4467.4  4484.9  4499.9  4521.6
    4523  4533.2  4546.7  4578.7  4585.1  4607.1  4624.9  4637.1  4643.2  4676.6
  4700.1    4715  4721.1  4728.4  4740.3  4747.6  4763.6  4779.9  4818.7  4834.3
  4937.5  4937.5  5062.5  5062.5    5118  5145.4  5162.8    5176  5208.6  5234.8
    5248  5272.4  5298.6  5324.4  5329.2  5337.2  5351.1  5376.7  5416.8  5428.4
  5433.6  5444.4    5455  5494.1  5505.7  5519.2  5526.9    5532  5542.5  5565.3
   768.5  767.26  764.77   762.8   761.2  759.62  758.63  757.14  756.26   754.4
  754.47  753.78  752.49  750.29  749.64  748.12  746.35  745.66  745.04  742.34
  740.57  738.96  738.73  738.21  737.19  736.34  735.61  734.38   732.8     732
     732     732     732     732     732  732.85  733.88   734.4  736.29  738.21
  739.03  740.87  743.43  745.55  745.79  746.74  747.73  750.22  753.53  754.65
  754.92  756.35  756.83  760.99   761.7  763.31  763.57  764.14  765.64  767.95
     686     686     686     686     686     686     686     686     686     686
     686     686     686     686     686     686     686     686     686     686
     686     686     686     686     686     686     686     686     686     686
     686     730     730     686     686     686     686     686     686     686
     686     686     686     686     686     686     686     686     686     686
     686     686     686     686     686     686     686     686     686     686
Pier Skew, UpSta & Num, DnSta & Num=  ,4968.8, 2 ,4968.8, 2 , 0 , 0 , 0 ,0,0
       2       2
  713.67     730
       2       2
  708.61     730
Pier Skew, UpSta & Num, DnSta & Num=  ,5031.3, 2 ,5031.3, 2 , 0 , 0 , 0 ,0,0
       2       2
  708.03     730
       2       2
  708.22     730
Abutment Skew #Up #Dn= , 2 , 2
  4937.5    4955
     730  718.22
  4937.5    4955
     730  718.55
Abutment Skew #Up #Dn= , 2 , 2
    5045  5062.5
  715.39     730
    5045  5062.5
  714.53     730
BR Coef= 1 , 1 , 0 ,1.25, 0 ,,,0.8,0,2,0,
WSPro=,,,, 1 ,,,, 0 ,,,, 0 ,,,,-1 ,-1 ,-1 , 0 , 0 , 0 , 0 , 0
BC Design=,, 0 ,, 0 ,,,,,,
BC HTab HWMax=794.55

Type RM Length L Ch R = 1 ,24216   ,677,677,677
BEGIN DESCRIPTION:
Sheppard Mill Rd. SR-1674 -DS
END DESCRIPTION:
XS GIS Cut Line= 4
      1664944.02       982208.52      1664456.94        981993.2
      1664321.06       981917.95      1663865.34       981669.18
#Sta/Elev= 30
  4319.9  753.01  4380.1  751.54  4393.4  747.03  4470.7  744.51  4492.6  740.45
  4498.1  745.15  4521.5  738.95  4541.4  740.47  4617.1  731.15  4664.8  733.53
  4707.3  736.72  4818.1  730.43  4956.1  718.45  4968.4  709.16    4979  708.75
  4982.5  705.75  5017.5  705.75    5021  708.75  5037.5  709.45  5062.4  722.19
  5098.3  728.93  5142.4  746.46  5208.1  747.25  5252.4  754.73  5277.9  751.49
    5342  750.82  5393.5  743.95  5417.8  746.39  5457.2  760.28    5527  777.16
#Mann= 4 ,-1 , 0
  4319.9     .09       0  4664.8     .06       0    4979     .05       0
    5021     .09       0
#XS Ineff= 2 , 0
       0 4913.25     732 5086.75       0     732
Permanent Ineff=
       F       F
Bank Sta=4979,5021
Exp/Cntr=0.5,0.3

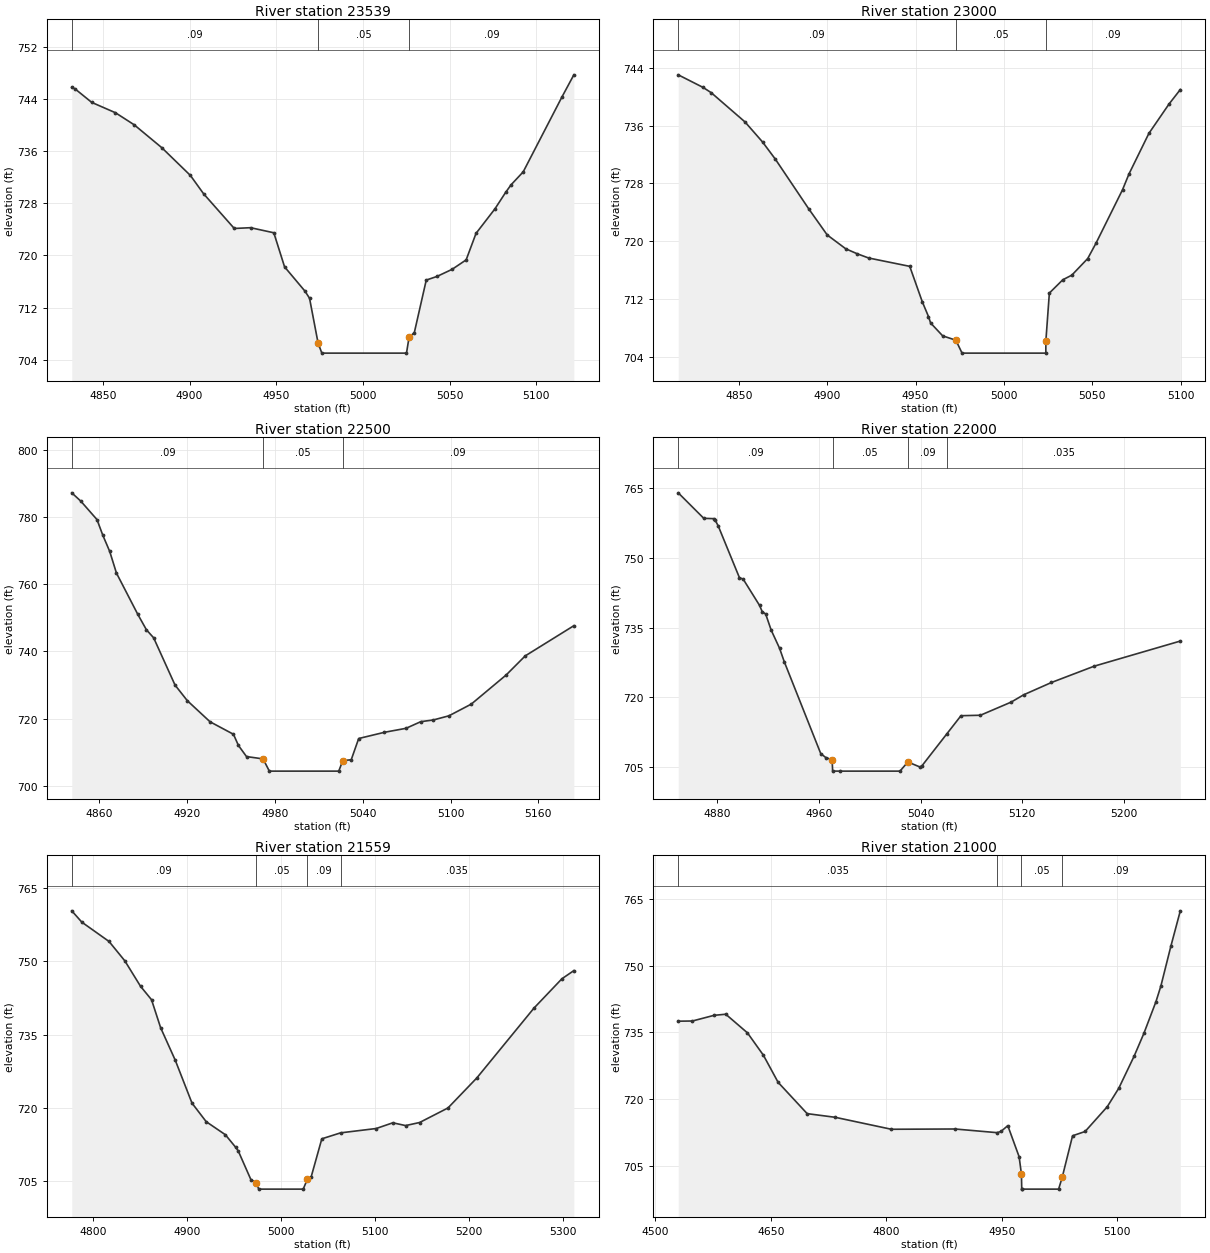
Type RM Length L Ch R = 1 ,23539   ,539,539,539
BEGIN DESCRIPTION:
Snow Creek 48.0
END DESCRIPTION:
XS GIS Cut Line= 4
      1664323.15       981326.35      1664191.45       981299.17
      1664132.92       981301.26      1664036.76       981309.62
#Sta/Elev= 30
  4832.1  745.83  4834.1  745.54  4843.6  743.49  4857.3   741.9  4868.1  740.05
    4884  736.54  4900.5  732.28  4908.1  729.47  4925.8  724.14  4935.2  724.26
  4948.6  723.48  4954.8  718.25  4966.6  714.51  4969.2  713.43 4974.13  706.55
  4976.3  705.01  5025.1  705.01  5026.6  707.46  5029.6  708.14  5036.5  716.22
  5042.7  716.78  5051.4  717.87  5059.5  719.32  5065.2  723.39  5076.1  727.15
  5082.3  729.69  5085.4  730.84  5092.4  732.83  5114.7   744.3  5121.6  747.72
#Mann= 3 , 0 , 0
  4832.1     .09       0 4974.13     .05       0  5026.6     .09       0
Bank Sta=4974.13,5026.6
Exp/Cntr=0.3,0.1

Type RM Length L Ch R = 1 ,23000   ,500,500,500
BEGIN DESCRIPTION:
Snow Creek 47.0
END DESCRIPTION:
XS GIS Cut Line= 3
      1664404.68       980816.27        1664226.       980771.31
      1664126.65       980761.92
#Sta/Elev= 30
  4815.7  743.05  4829.8   741.3  4834.4  740.57  4853.5  736.52  4863.4  733.75
  4870.7  731.35  4889.7  724.43    4900  720.87  4910.5  718.95    4917  718.26
  4923.4  717.68  4946.7  716.52  4953.8  711.61  4957.3  709.57  4958.5  708.68
 4965.34  706.89 4972.79  706.29  4976.3   704.5  5023.7   704.5 5023.73  706.21
  5025.7  712.82  5033.3  714.66  5038.4   715.3  5047.4   717.6  5052.1  719.73
  5067.1  727.13  5070.8  729.34    5082  734.93  5093.4     739  5099.8  741.01
#Mann= 3 , 0 , 0
  4815.7     .09       0 4972.79     .05       0 5023.73     .09       0
Bank Sta=4972.79,5023.73
Exp/Cntr=0.3,0.1

Type RM Length L Ch R = 1 ,22500   ,500,500,500
BEGIN DESCRIPTION:
Snow Creek 46.0
END DESCRIPTION:
XS GIS Cut Line= 3
      1664314.79       980207.95      1664176.93       980286.44
      1664017.95       980379.37
#Sta/Elev= 30
  4841.4  787.12  4847.6  784.63  4858.6  779.17  4862.6   774.5  4867.3   769.7
  4871.9  763.26  4886.5  750.96  4892.4  746.37  4897.3     744  4911.9  729.95
  4920.3   725.3  4935.8  719.03  4951.8  715.31  4955.2  711.98  4960.7  708.68
    4972  707.99  4976.3  704.35  5023.7  704.35 5026.42  707.48  5032.2  707.73
  5037.3  714.05  5054.9   715.9  5069.6  717.08  5079.7  719.06  5088.2  719.56
  5098.9   720.8  5114.2  724.29    5138  732.95    5151  738.62  5184.2   747.6
#Mann= 3 , 0 , 0
  4841.4     .09       0    4972     .05       0 5026.42     .09       0
Bank Sta=4972,5026.42
Exp/Cntr=0.3,0.1

Type RM Length L Ch R = 1 ,22000   ,441,441,441
BEGIN DESCRIPTION:
Snow Creek 45.0
END DESCRIPTION:
XS GIS Cut Line= 3
      1664011.68        979779.4      1663895.78        979875.9
      1663806.81       980103.42
#Sta/Elev= 30
  4849.2  764.01  4869.3  758.52  4877.3  758.45  4878.3  758.08  4880.6  756.93
  4897.3  745.78  4900.4  745.39  4913.2  739.77  4915.3  738.42    4918  737.93
  4922.3  734.48  4928.9  730.57  4932.6  727.68 4961.37  707.86 4965.34  707.02
 4970.31  706.55  4970.7  704.11  4976.3   704.1  5023.7   704.1 5029.89  706.07
  5039.5  704.98    5041  705.25  5060.7  712.17  5071.7  716.03    5087  716.13
  5111.2  718.96  5121.1  720.54  5142.9  723.18  5176.6   726.7  5244.3   732.1
#Mann= 4 ,-1 , 0
  4849.2     .09       0  4970.7     .05       0 5029.89     .09       0
  5060.7    .035       0
Bank Sta=4970.31,5029.89
Exp/Cntr=0.3,0.1

Type RM Length L Ch R = 1 ,21559   ,559,559,559
BEGIN DESCRIPTION:
Snow Creek 44.0
END DESCRIPTION:
XS GIS Cut Line= 4
      1663627.03       979668.61      1663478.61       979760.59
      1663476.52       979812.85      1663463.97       980120.15
#Sta/Elev= 30
  4777.3  760.35    4788  758.03    4817  754.07  4833.8   750.1  4850.5  744.89
  4862.2  742.14  4871.9   736.4  4887.5  729.73  4905.3  720.95  4920.4  717.15
  4940.8  714.48  4951.9  711.87  4954.5  711.17  4968.1  705.23 4973.88  704.64
  4976.3  703.33  5023.7  703.33  5028.1  705.36  5032.1   705.8  5043.5  713.64
  5063.5  714.86  5101.4  715.75  5119.1  716.92  5132.7  716.35  5147.6  716.98
  5177.8  719.96  5208.5  726.11  5269.4  740.43  5299.1  746.43  5311.8   748.1
#Mann= 4 ,-1 , 0
  4777.3     .09       0 4973.88     .05       0  5028.1     .09       0
  5063.5    .035       0
Bank Sta=4973.88,5028.1
Exp/Cntr=0.3,0.1

Type RM Length L Ch R = 1 ,21000   ,500,500,500
BEGIN DESCRIPTION:
Snow Creek 43.0
END DESCRIPTION:
XS GIS Cut Line= 4
      1663246.57       979327.86      1663054.24       979507.64
      1662940.06       979680.28      1662818.02       979814.94
#Sta/Elev= 30
  4529.8  737.53  4548.2  737.57  4576.3  738.84  4591.5  739.09  4619.7  734.91
  4640.4   729.9  4659.5  723.83  4697.2  716.82  4733.6     716  4806.5  713.32
  4889.2  713.38  4943.7  712.56  4948.8  712.82  4957.7  714.13  4972.4  707.17
  4975.4  703.28  4975.8  699.96  4976.3  699.91  5023.7  699.91  5028.3  702.52
  5041.8  711.86  5058.1  712.82  5086.9  718.38  5101.9  722.54  5121.7  729.68
  5134.4   734.8  5150.1  741.91  5156.5  745.43  5169.4   754.3  5181.7  762.25
#Mann= 4 ,-1 , 0
  4529.8    .035       0  4943.7     .09       0  4975.4     .05       0
  5028.3     .09       0
Bank Sta=4975.4,5028.3
Exp/Cntr=0.3,0.1