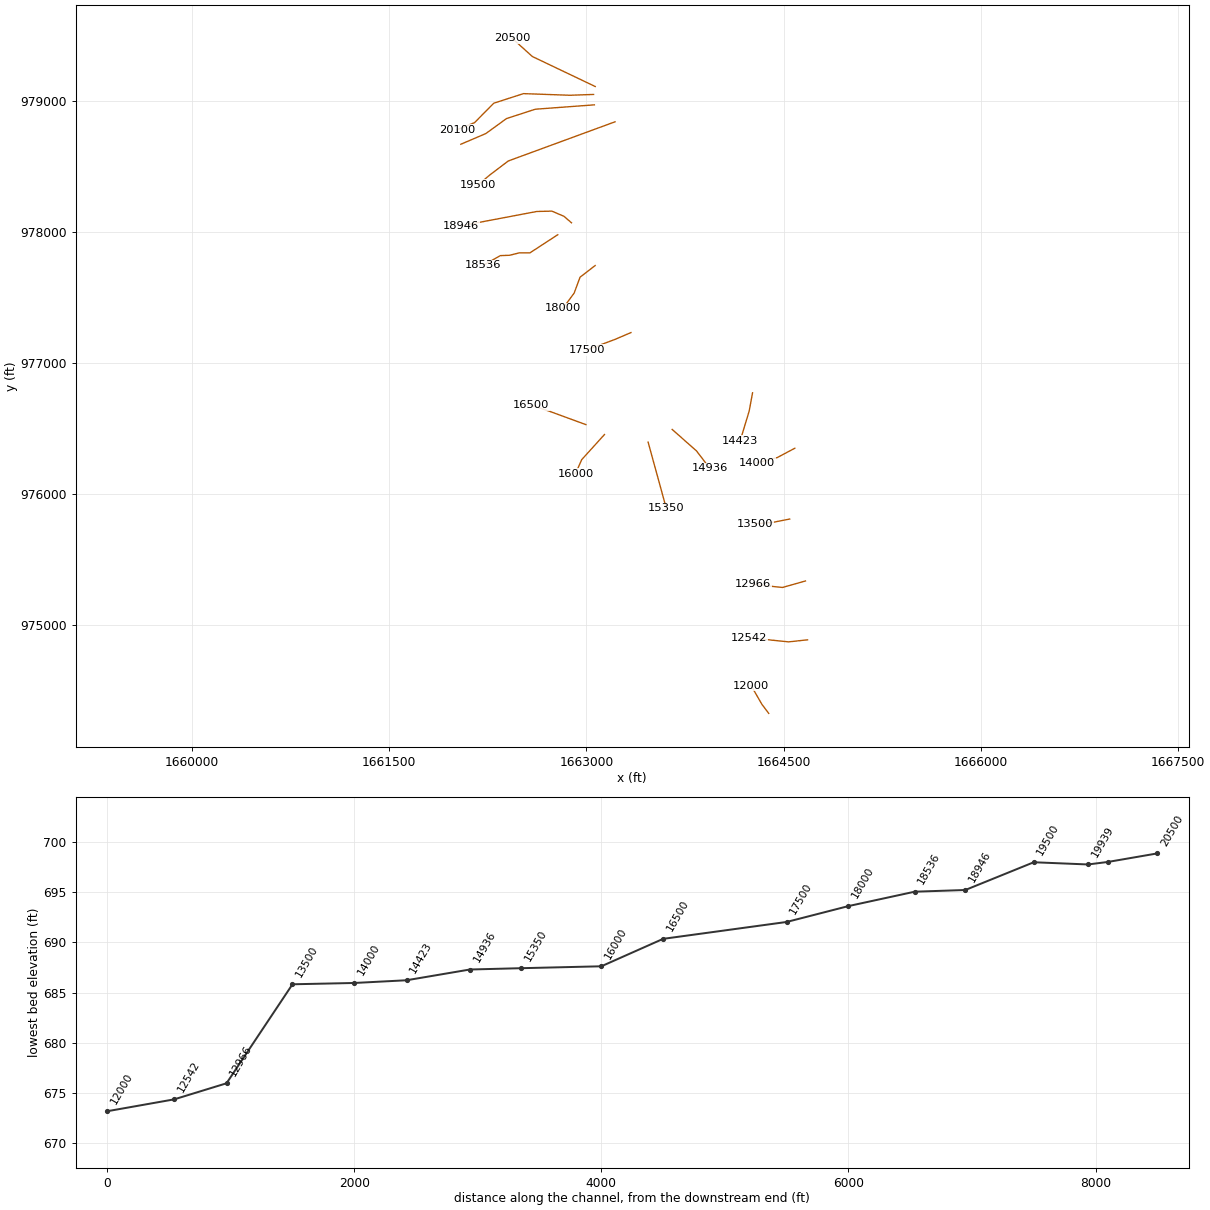
HEC-RAS study lds_snow_crk.prj: Snow Creek Limited Detail Study

--- lds_snow_crk.g02 (geometry) --- (continued)

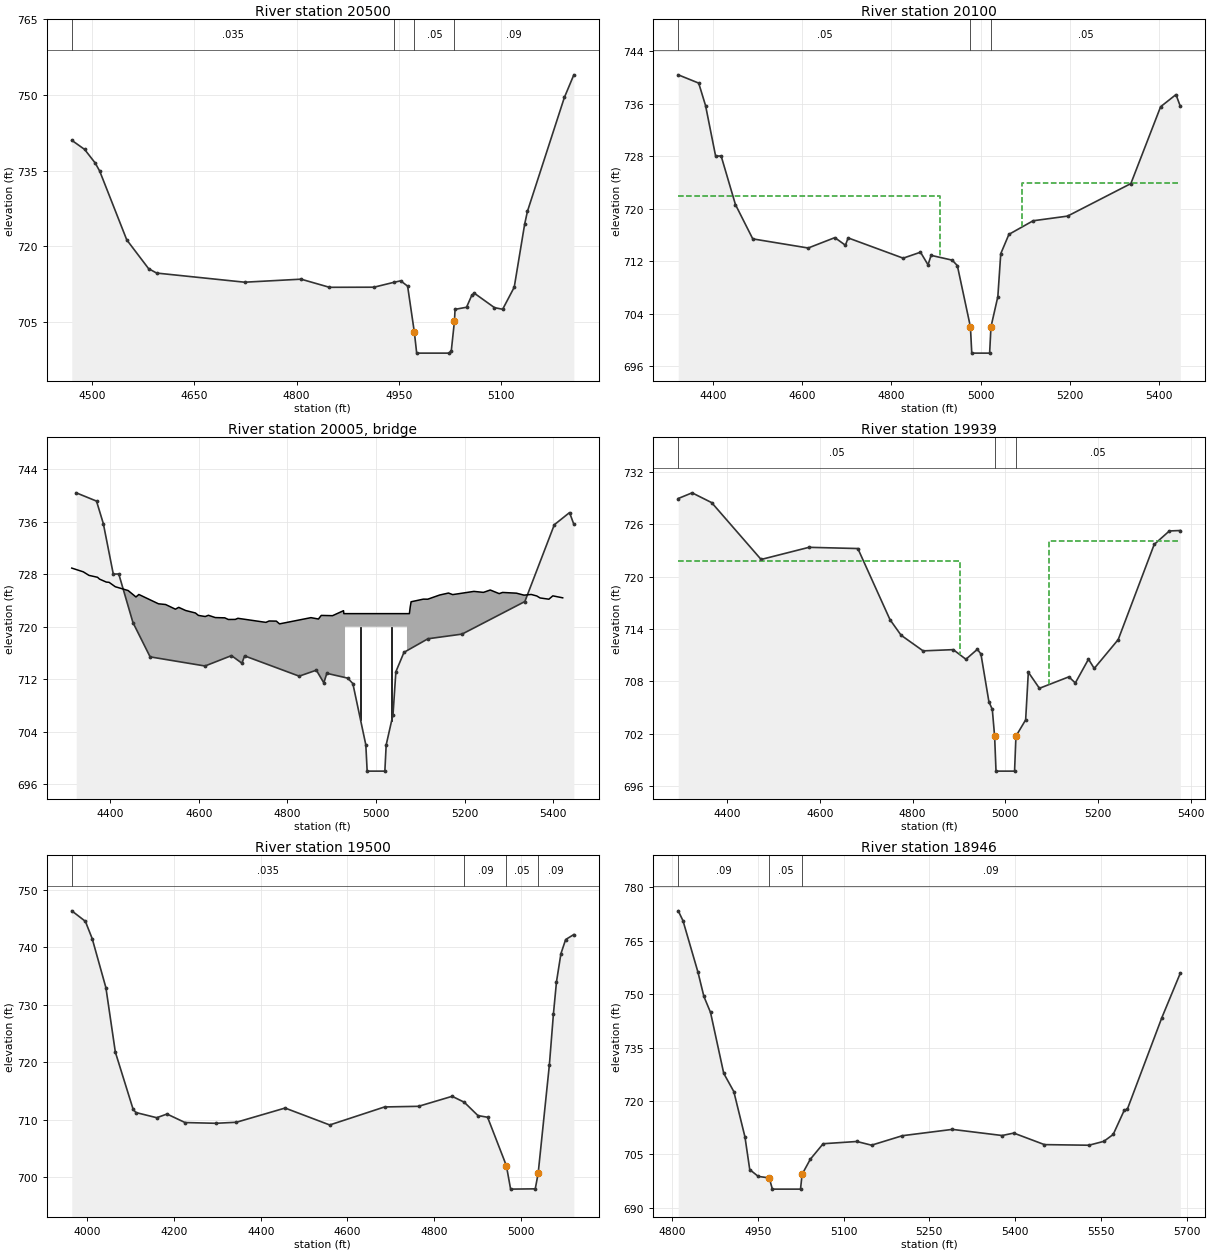
Type RM Length L Ch R = 1 ,20500   ,400,400,400
BEGIN DESCRIPTION:
Snow Creek 42.0
END DESCRIPTION:
XS GIS Cut Line= 3
      1663066.79       979112.55      1662588.85       979341.51
      1662435.47       979480.47
#Sta/Elev= 30
    4470  741.01  4488.9   739.2  4504.5  736.49    4511  734.91  4550.7  721.29
  4582.8  715.58  4594.6  714.71  4723.8   712.9  4806.6   713.5  4848.2  711.89
  4913.6  711.91  4942.9  712.88  4952.8  713.17    4963  712.12 4972.89  702.98
  4976.3  698.85  5023.7  698.85  5027.1   699.3  5031.8  705.26  5032.6  707.52
  5049.5  707.94  5057.2  710.31  5060.8  710.73  5090.5  707.86  5102.5  707.54
  5119.5  711.91  5134.8   724.4  5138.9  726.95  5193.1   749.5    5207  753.98
#Mann= 4 ,-1 , 0
    4470    .035       0  4942.9     .09       0 4972.89     .05       0
  5031.8     .09       0
Bank Sta=4972.89,5031.8
Exp/Cntr=0.5,0.3

Type RM Length L Ch R = 1 ,20100   ,161,161,161
BEGIN DESCRIPTION:
Phillips Rd. SR-1673 -US
END DESCRIPTION:
XS GIS Cut Line= 6
      1663054.24       979051.92      1662872.37       979045.65
      1662521.18       979058.19      1662295.41       978985.03
      1662149.07        978836.6      1662015.28       978782.25
#Sta/Elev= 30
  4322.7  740.41  4368.5  739.15  4383.9  735.72  4406.4  728.03  4418.8  728.04
  4450.8  720.64  4489.6  715.41  4613.7  714.02  4673.4   715.6  4697.1  714.44
  4703.1  715.56  4826.4  712.47  4865.2  713.38  4882.1  711.45  4888.9   712.9
 4936.13  712.17  4947.7  711.34    4977     702    4980     698    5020     698
    5023     702  5038.4  706.61  5044.9  713.15  5063.2   716.1  5117.4  718.17
  5194.5  718.88  5336.3  723.84  5402.9  735.55  5437.3   737.4    5447  735.61
#Mann= 3 , 0 , 0
  4322.7     .05       0    4977     .04       0    5023     .05       0
#XS Ineff= 2 , 0
       0    4908  722.02    5092       0   723.9
Permanent Ineff=
       F       F
Bank Sta=4977,5023
Exp/Cntr=0.5,0.3

Type RM Length L Ch R = 3 ,20005   ,,,
BEGIN DESCRIPTION:
Phillips Rd. SR-1673
Structure ID: Phillips Rd
Approximate Survey Structure
END DESCRIPTION:
Bridge Culvert--1,0,-1,-1, 0
Deck Dist Width WeirC Skew NumUp NumDn MinLoCord MaxHiCord MaxSubmerge Is_Ogee
77.5,35,3,0, 60, 60, , , , 0, 1,1,,
  4312.6  4338.6  4351.5  4370.8  4375.3  4390.6  4396.9  4410.9    4440  4457.6
  4464.2  4508.5  4524.6  4546.8  4554.2  4569.8    4592  4598.8  4614.1  4621.3
  4636.9  4658.3  4666.3  4682.1  4687.9  4751.2  4758.5  4774.8    4782    4853
  4869.9  4876.3  4901.8  4926.6  4927.3    4930    4930    5070    5070  5075.4
  5077.3  5079.3    5107  5116.9  5143.9  5163.8  5173.2  5221.2  5242.7  5258.1
  5278.3  5285.9  5317.3  5334.3  5350.8  5363.3  5370.7  5390.6  5399.5  5421.8
  728.94  728.37  727.83  727.54  727.26  726.81  726.77   726.1  725.52  724.54
  724.92   723.5  723.39  722.68  722.96  722.48   722.1  721.73  721.56  721.75
   721.4  721.36  721.11  721.12  721.29  720.67  720.88  720.86  720.44  721.39
  721.18  721.73  721.69  722.45     722     722     722     722     722     722
  723.01  723.81  724.21   724.2  724.84  725.14   724.9  725.39  725.24   725.6
  725.05  725.23  725.12  724.82  724.92  724.69  724.39   724.2  724.71  724.41
     678     678     678     678     678     678     678     678     678     678
     678     678     678     678     678     678     678     678     678     678
     678     678     678     678     678     678     678     678     678     678
     678     678     678     678     678     678     720     720     678     678
     678     678     678     678     678     678     678     678     678     678
     678     678     678     678     678     678     678     678     678     678
  4312.6  4338.6  4351.5  4370.8  4375.3  4390.6  4396.9  4410.9    4440  4457.6
  4464.2  4508.5  4524.6  4546.8  4554.2  4569.8    4592  4598.8  4614.1  4621.3
  4636.9  4658.3  4666.3  4682.1  4687.9  4751.2  4758.5  4774.8    4782    4853
  4869.9  4876.3  4901.8  4926.6  4927.3    4930    4930    5070    5070  5075.4
  5077.3  5079.3    5107  5116.9  5143.9  5163.8  5173.2  5221.2  5242.7  5258.1
  5278.3  5285.9  5317.3  5334.3  5350.8  5363.3  5370.7  5390.6  5399.5  5421.8
  728.94  728.37  727.83  727.54  727.26  726.81  726.77   726.1  725.52  724.54
  724.92   723.5  723.39  722.68  722.96  722.48   722.1  721.73  721.56  721.75
   721.4  721.36  721.11  721.12  721.29  720.67  720.88  720.86  720.44  721.39
  721.18  721.73  721.69  722.45     722     722     722     722     722     722
  723.01  723.81  724.21   724.2  724.84  725.14   724.9  725.39  725.24   725.6
  725.05  725.23  725.12  724.82  724.92  724.69  724.39   724.2  724.71  724.41
     678     678     678     678     678     678     678     678     678     678
     678     678     678     678     678     678     678     678     678     678
     678     678     678     678     678     678     678     678     678     678
     678     678     678     678     678     678     720     720     678     678
     678     678     678     678     678     678     678     678     678     678
     678     678     678     678     678     678     678     678     678     678
Pier Skew, UpSta & Num, DnSta & Num=  ,4965, 2 ,4965, 2 , 0 , 0 , 0 ,0,0
       2       2
  705.16     720
       2       2
  705.63     720
Pier Skew, UpSta & Num, DnSta & Num=  ,5035, 2 ,5035, 2 , 0 , 0 , 0 ,0,0
       2       2
   699.3     720
       2       2
  699.06     720
Abutment Skew #Up #Dn= , 2 , 2
    4930    4964
     720  705.91
    4930    4964
     720   705.9
Abutment Skew #Up #Dn= , 2 , 2
    5036    5070
  699.07     720
    5036    5070
  698.83     720
BR Coef= 1 , 1 , 0 ,1.25, 0 ,,,0.8,0,2,0,
WSPro=,,,, 1 ,,,, 0 ,,,, 0 ,,,,-1 ,-1 ,-1 , 0 , 0 , 0 , 0 , 0
BC Design=,, 0 ,, 0 ,,,,,,
BC HTab HWMax=740.41

Type RM Length L Ch R = 1 ,19939   ,439,439,439
BEGIN DESCRIPTION:
Phillips Rd. SR-1673 - DS
END DESCRIPTION:
XS GIS Cut Line= 6
      1663060.51       978972.48      1662611.07       978939.04
      1662391.53       978867.37      1662326.76       978819.88
      1662234.78       978752.99      1662044.55       978671.46
#Sta/Elev= 30
  4294.8  728.92  4324.7  729.57  4366.9  728.45  4473.5  721.95  4576.8  723.34
  4682.1   723.2  4751.4  715.07  4775.3  713.29  4822.8   711.5  4887.8  711.64
  4915.1  710.54  4939.8  711.68  4947.5  711.14  4964.7  705.68    4972  704.81
    4977  701.75    4980  697.75    5020  697.75    5023  701.75  5043.9  703.61
  5049.7  709.06  5073.6  707.22  5137.1  708.53    5151  707.83  5179.4  710.55
  5191.8  709.49  5243.5  712.79  5321.1  723.67  5353.8  725.21  5377.4  725.26
#Mann= 3 ,-1 , 0
  4294.8     .05       0    4977     .04       0    5023     .05       0
#XS Ineff= 2 , 0
       0    4902  721.74  5094.1       0  724.03
Permanent Ineff=
       F       F
Bank Sta=4977,5023
Exp/Cntr=0.5,0.3

Type RM Length L Ch R = 1 ,19500   ,554,554,554
BEGIN DESCRIPTION:
Snow Creek 40.0
END DESCRIPTION:
XS GIS Cut Line= 4
       1663217.3       978842.88       1662406.2       978543.94
      1662269.69        978440.5      1662176.25       978362.07
#Sta/Elev= 30
  3964.3  746.33  3995.6  744.51  4011.4   741.5    4043  732.98  4064.8  721.77
  4105.8  711.84  4112.2  711.28  4160.2  710.38  4183.9  711.02  4225.5  709.54
  4296.6  709.41  4343.9  709.59  4456.2  712.06  4559.1  709.12  4685.5  712.25
  4763.9  712.36  4841.4   714.1  4869.3  713.07  4900.9  710.75  4923.1  710.46
 4966.44  702.04  4976.2  697.97    5033  698.02  5039.7  700.69  5065.6  719.58
  5074.9   728.4    5082  734.01  5092.2  738.88  5103.1  741.34    5122  742.21
#Mann= 4 ,-1 , 0
  3964.3    .035       0  4869.3     .09       0 4966.44     .05       0
  5039.7     .09       0
#XS Ineff= 2 , 0
       0    4800                       0
Permanent Ineff=
       F       F
Bank Sta=4966.44,5039.7
Exp/Cntr=0.3,0.1

Type RM Length L Ch R = 1 ,18946   ,410,410,410
BEGIN DESCRIPTION:
Snow Creek 39.0
END DESCRIPTION:
XS GIS Cut Line= 5
      1662886.22       978071.76      1662828.73       978121.41
      1662737.28        978160.6       1662622.3       978157.99
      1662044.81       978048.24
#Sta/Elev= 30
  4810.7  773.43    4819  770.66  4845.2  756.19  4855.6  749.36  4867.2  744.87
  4890.3  727.75  4907.9  722.64  4927.4   709.9  4935.8   700.7  4950.7  698.78
 4969.81  698.37  4975.4  695.21  5024.6  695.21 5027.41  699.39  5041.7   703.6
  5064.2  707.97  5123.2   708.6  5148.8  707.56  5202.9  710.23  5290.2     712
  5377.2  710.28  5397.7  710.96  5451.3  707.72  5529.1  707.55  5555.2  708.64
  5571.6  710.58  5591.2  717.47  5596.2  717.62  5656.7   743.4    5689  755.92
#Mann= 3 , 0 , 0
  4810.7     .09       0 4969.81     .05       0 5027.41     .09       0
#XS Ineff= 2 , 0
       0                    5300       0
Permanent Ineff=
       F       F
Bank Sta=4969.81,5027.41
Exp/Cntr=0.3,0.1

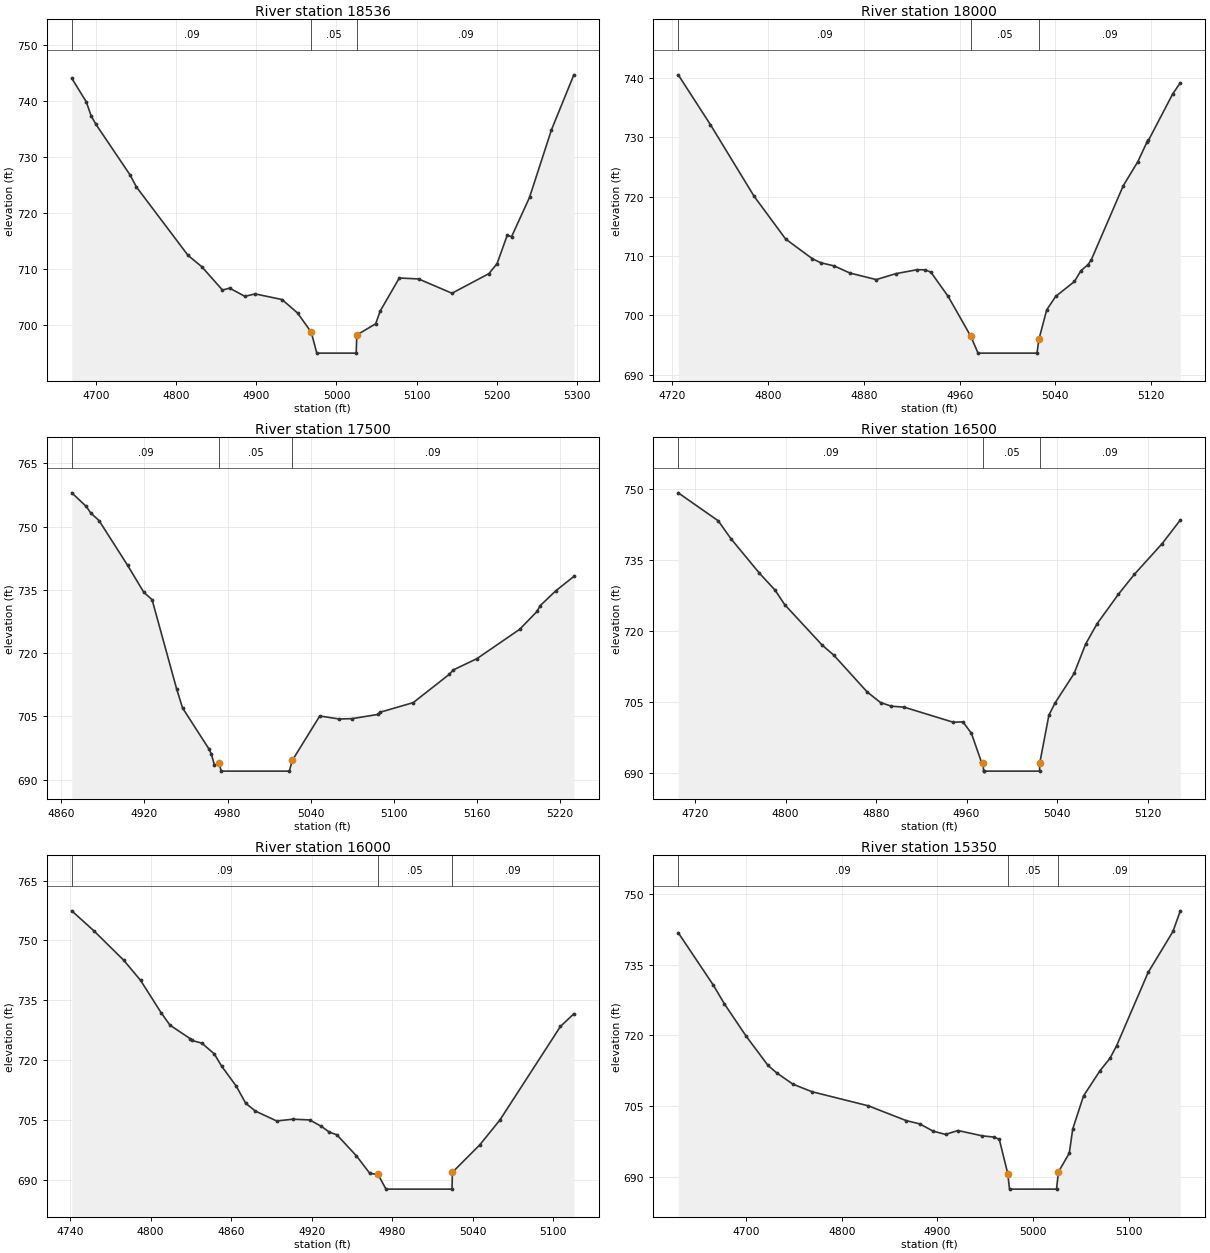
Type RM Length L Ch R = 1 ,18536   ,536,536,536
BEGIN DESCRIPTION:
Snow Creek 38.0
END DESCRIPTION:
XS GIS Cut Line= 6
       1662781.7        977980.3      1662570.04       977841.81
      1662489.03       977841.81      1662415.87       977823.51
      1662345.32        977820.9      1662217.27       977747.74
#Sta/Elev= 30
  4669.2  744.06  4687.3  739.86  4693.5  737.33  4699.4  735.84    4742  726.83
    4750  724.67  4814.5  712.47  4831.6  710.46  4857.5  706.29  4866.5  706.63
  4885.5  705.17  4898.4   705.6  4931.9   704.6  4951.4  702.19 4968.42  698.78
  4975.4  695.04  5024.6  695.04 5025.42  698.27    5049  700.28  5054.5  702.52
  5078.5  708.44  5102.6  708.27  5144.3  705.72  5190.5  709.22  5200.7  711.01
  5213.3  716.04  5218.8  715.81  5241.2  722.81  5268.6  734.85  5296.6  744.67
#Mann= 3 , 0 , 0
  4669.2     .09       0 4968.42     .05       0 5025.42     .09       0
Bank Sta=4968.42,5025.42
Exp/Cntr=0.3,0.1

Type RM Length L Ch R = 1 ,18000   ,500,500,500
BEGIN DESCRIPTION:
Snow Creek 37.0
END DESCRIPTION:
XS GIS Cut Line= 4
      1663066.53       977745.12      1662951.55       977656.28
      1662906.63       977534.59       1662820.9       977418.49
#Sta/Elev= 30
    4725  740.54  4751.9  732.13  4788.3  720.08  4814.7  712.85    4837  709.53
  4844.1  708.85  4855.2  708.32  4868.3  707.12  4890.4  706.01  4906.7  707.01
  4924.6  707.68  4931.4  707.66  4936.1  707.24  4950.4  703.18 4969.12  696.53
  4975.4  693.61  5024.6  693.61 5026.22  695.92  5032.7   700.9  5040.2  703.17
  5055.9  705.69  5061.3  707.51  5067.3  708.55    5070  709.37  5096.7  721.86
  5108.7  725.85  5116.5  729.22  5117.7  729.49    5138  737.34  5144.3  739.19
#Mann= 3 , 0 , 0
    4725     .09       0 4969.12     .05       0 5026.22     .09       0
Bank Sta=4969.12,5026.22
Exp/Cntr=0.3,0.1

Type RM Length L Ch R = 1 ,17500   ,1000,1000,1000
BEGIN DESCRIPTION:
Snow Creek 36.0
END DESCRIPTION:
XS GIS Cut Line= 3
      1663338.29       977232.96      1663216.53       977180.66
       1663001.2       977099.69
#Sta/Elev= 30
  4867.5     758    4878  754.76  4881.2  753.22  4887.2  751.42  4907.9  740.78
  4919.5  734.43  4925.5  732.68  4943.2  711.56  4947.5  707.01  4966.4  697.37
  4968.3   696.1  4970.5  693.47 4973.93  693.93  4975.4  692.03  5024.6  692.03
  5026.8  694.59  5046.6   705.1  5060.6  704.39  5069.9  704.47  5088.4  705.46
  5090.2  705.99  5114.1  708.27    5140  714.94    5143  716.01  5160.1  718.69
  5190.9  725.63  5203.5  729.88  5205.8  731.25    5217  734.76  5230.1  738.18
#Mann= 3 , 0 , 0
  4867.5     .09       0 4973.93     .05       0  5026.8     .09       0
Bank Sta=4973.93,5026.8
Exp/Cntr=0.3,0.1

Type RM Length L Ch R = 1 ,16500   ,500,500,500
BEGIN DESCRIPTION:
Snow Creek 34.0
END DESCRIPTION:
XS GIS Cut Line= 3
      1662995.97       976530.04      1662719.21       976631.85
      1662577.88       976678.99
#Sta/Elev= 30
  4705.1  749.14  4740.4  743.24  4751.7  739.45  4776.9  732.16  4790.7  728.59
  4799.2  725.53  4832.4  716.96  4842.6  714.86  4872.2  707.06    4884  704.83
  4893.6  704.07  4904.9  703.86  4948.2  700.68  4956.8  700.76  4964.3  698.34
    4973  692.38  4974.5   692.1  4975.1  690.38  4975.4  690.35  5024.6  690.35
 5024.73  692.04  5032.8  702.16  5038.2  704.73  5055.1  710.98  5065.3   717.2
  5075.4  721.48  5094.3  727.72  5108.3   731.9  5132.8  738.37    5149  743.39
#Mann= 3 , 0 , 0
  4705.1     .09       0  4974.5     .05       0 5024.73     .09       0
Bank Sta=4974.5,5024.73
Exp/Cntr=0.3,0.1

Type RM Length L Ch R = 1 ,16000   ,650,650,650
BEGIN DESCRIPTION:
Snow Creek 33.0
END DESCRIPTION:
XS GIS Cut Line= 3
      1663137.08       976454.26      1662963.71       976262.14
      1662917.58       976156.37
#Sta/Elev= 30
  4741.2  757.43  4757.7  752.41  4779.9  745.04  4792.5  739.98  4807.7  731.92
  4814.4  728.75  4829.5  725.36  4830.8  724.91  4838.1  724.25  4847.4  721.55
  4852.9  718.46  4863.8  713.45  4870.8  709.18    4878  707.21  4893.9  704.72
    4906  705.16  4918.5  704.98  4927.3  703.35  4933.1  701.94  4938.8  701.24
  4953.4  695.95  4963.3  691.59 4969.46  691.29  4975.4  687.62  5024.6  687.62
 5024.88  691.84  5045.3  698.73  5060.3  704.96  5105.4  728.42  5115.4  731.61
#Mann= 3 , 0 , 0
  4741.2     .09       0 4969.46     .05       0 5024.88     .09       0
Bank Sta=4969.46,5024.88
Exp/Cntr=0.3,0.1

Type RM Length L Ch R = 1 ,15350   ,414,414,414
BEGIN DESCRIPTION:
Snow Creek 32.0
END DESCRIPTION:
XS GIS Cut Line= 3
      1663468.94       976396.77      1663568.24       976033.56
      1663607.43       975889.84
#Sta/Elev= 30
  4628.6  741.77  4665.1  730.74  4676.9   726.7  4699.7  719.85  4722.6  713.64
  4731.6  712.08  4748.7  709.67  4768.5  708.08  4827.7  705.08  4867.3  701.95
  4881.4  701.26  4895.5  699.71  4908.4  699.03  4921.5  699.85  4946.9  698.72
  4959.2  698.46  4964.7  697.98 4973.58  690.71  4975.4  687.43  5024.6  687.43
 5026.61  691.07    5038  695.07  5041.6  700.19  5052.9  707.19  5070.2  712.55
  5080.5  715.13  5087.5  717.82  5120.5  733.34  5146.5  742.04  5154.2  746.41
#Mann= 3 , 0 , 0
  4628.6     .09       0 4973.58     .05       0 5026.61     .09       0
Bank Sta=4973.58,5026.61
Exp/Cntr=0.3,0.1

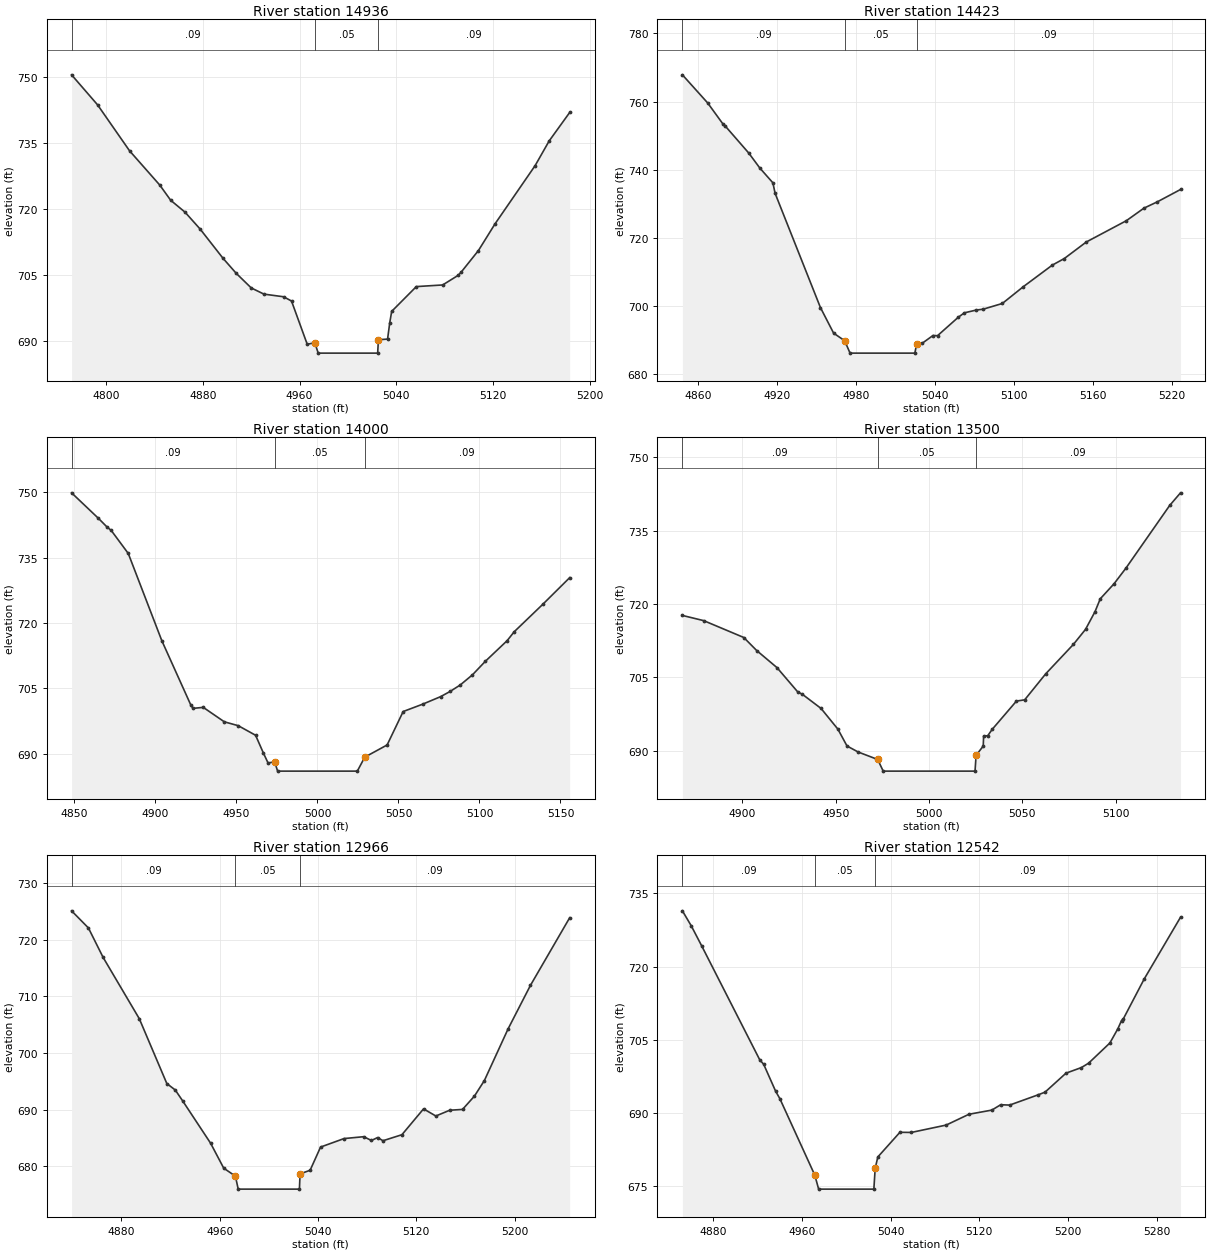
Type RM Length L Ch R = 1 ,14936   ,513,513,513
BEGIN DESCRIPTION:
Snow Creek 31.0
END DESCRIPTION:
XS GIS Cut Line= 3
      1663651.85       976493.46      1663837.38       976328.83
      1663936.68       976198.18
#Sta/Elev= 30
  4771.3   750.5  4792.8  743.69  4819.3  733.24  4844.3  725.46  4853.3  722.02
  4865.2  719.31  4877.7  715.47  4896.7  708.81  4907.6  705.41    4920   702.1
  4930.5   700.7  4946.7   700.1  4953.3  699.14  4966.3  689.32 4972.59  689.66
  4975.4   687.3  5024.6   687.3 5025.22  690.34  5032.8  690.49  5034.6   694.2
  5036.2  696.78  5056.6  702.41  5078.4  702.78  5091.3  704.98  5093.9  705.76
    5108   710.6  5121.8  716.69  5154.9  729.88  5166.5  735.48  5183.5  741.95
#Mann= 3 , 0 , 0
  4771.3     .09       0 4972.59     .05       0 5025.22     .09       0
Bank Sta=4972.59,5025.22
Exp/Cntr=0.3,0.1

Type RM Length L Ch R = 1 ,14423   ,423,423,423
BEGIN DESCRIPTION:
Snow Creek 30.0
END DESCRIPTION:
XS GIS Cut Line= 3
      1664263.31       976773.06      1664237.18       976631.95
      1664169.24       976407.23
#Sta/Elev= 30
  4848.1  767.85  4867.3   759.6    4879  753.37  4880.7   752.8  4898.5   744.9
  4906.9  740.51  4916.8  736.18  4918.5  733.08  4952.9   699.6  4962.9   692.1
  4971.3  689.86  4975.4  686.23  5024.6  686.23 5025.92  688.84 5030.39  689.18
 5038.33  691.39  5041.8  691.34  5057.6  696.76  5062.2  698.05  5071.3  698.87
  5076.4  699.11    5091  700.79    5107  705.73    5129  712.05  5138.1  713.98
  5154.8  718.83  5185.2  725.07  5198.5  728.74  5208.8  730.62  5226.3  734.22
#Mann= 3 , 0 , 0
  4848.1     .09       0  4971.3     .05       0 5025.92     .09       0
Bank Sta=4971.3,5025.92
Exp/Cntr=0.3,0.1

Type RM Length L Ch R = 1 ,14000   ,500,500,500
BEGIN DESCRIPTION:
Snow Creek 29.0
END DESCRIPTION:
XS GIS Cut Line= 3
      1664584.72       976349.74      1664450.81       976278.25
       1664299.9       976239.99
#Sta/Elev= 30
  4848.2   749.9  4864.8  744.03    4870  742.08  4872.7  741.25  4883.2  735.97
  4903.9  715.94  4921.8  701.16  4923.2  700.38  4929.5  700.61  4942.5  697.29
  4951.1   696.4  4961.8   694.2  4966.6  690.13  4969.5  687.83 4973.58   688.1
  4975.4  685.96  5024.6  685.96  5029.2  689.17    5043  691.97  5052.9  699.65
    5065  701.35    5076  703.07  5081.9  704.27  5088.1  705.74  5095.7  708.09
  5103.6  711.18  5117.1  715.94  5121.5     718    5139  724.25  5155.7  730.41
#Mann= 3 , 0 , 0
  4848.2     .09       0 4973.58     .05       0  5029.2     .09       0
Bank Sta=4973.58,5029.2
Exp/Cntr=0.3,0.1

Type RM Length L Ch R = 1 ,13500   ,534,534,534
BEGIN DESCRIPTION:
Snow Creek 28.0
END DESCRIPTION:
XS GIS Cut Line= 3
      1664545.53       975808.83      1664415.81       975783.38
      1664281.61       975772.25
#Sta/Elev= 30
  4867.8  717.65  4879.2  716.59  4900.7  713.14  4907.6  710.48  4918.5  706.98
  4929.6  702.02  4932.1  701.53  4942.1  698.64  4951.1  694.42    4956  690.97
  4961.9  689.75 4972.44  688.21  4975.4  685.83  5024.6  685.83 5025.17  689.05
    5029  690.96  5029.2     693  5031.4  693.06  5033.8  694.37  5046.8  700.15
  5051.2   700.4  5062.5  705.73  5077.3  711.73  5083.8   714.8  5088.9  718.43
  5091.7  721.05  5099.1  724.13  5105.4  727.29  5128.9  740.13  5134.7  742.71
#Mann= 3 , 0 , 0
  4867.8     .09       0 4972.44     .05       0 5025.17     .09       0
Bank Sta=4972.44,5025.17
Exp/Cntr=0.3,0.1

Type RM Length L Ch R = 1 ,12966   ,424,424,424
BEGIN DESCRIPTION:
Snow Creek 27.0
END DESCRIPTION:
XS GIS Cut Line= 3
      1664665.73       975335.86      1664490.65       975286.22
      1664268.54       975309.73
#Sta/Elev= 30
  4839.5  725.08  4853.2  722.06  4865.2  716.85  4894.6  706.05    4917  694.61
  4923.9  693.46  4929.8  691.58  4952.6  684.09  4963.3  679.68 4972.79  678.27
  4975.1  675.98  5024.9  675.98 5025.42  678.67  5033.6  679.31  5042.1   683.4
  5061.2   684.9  5077.2  685.23  5083.5  684.56  5088.5  685.08  5092.9  684.52
  5108.3  685.58  5125.9  690.14  5135.9  688.88  5147.2   689.9  5157.6  690.04
  5167.3  692.39  5175.4  695.14  5194.7  704.26  5212.9  711.94  5244.8  723.86
#Mann= 3 , 0 , 0
  4839.5     .09       0 4972.79     .05       0 5025.42     .09       0
Bank Sta=4972.79,5025.42
Exp/Cntr=0.3,0.1

Type RM Length L Ch R = 1 ,12542   ,542,542,542
BEGIN DESCRIPTION:
Snow Creek 26.0
END DESCRIPTION:
XS GIS Cut Line= 3
      1664681.41       974886.42      1664537.69       974870.74
      1664234.57       974902.09
#Sta/Elev= 30
  4852.2  731.43  4860.2  728.35  4869.7   724.2    4922  700.87  4925.5  699.98
  4936.3  694.45  4940.1  692.93  4971.6  677.26  4975.1  674.38  5024.9  674.38
  5026.1  678.66  5028.5  680.98  5048.4  686.03  5058.7     686  5090.1  687.51
  5110.7  689.73  5131.3  690.58  5139.3  691.68  5147.4  691.61  5173.3  693.73
  5179.3  694.26  5198.2  698.15  5212.1   699.3  5218.6   700.2  5237.8  704.34
    5245  707.26  5248.3  708.93  5249.8  709.23  5268.7  717.44  5301.5  730.11
#Mann= 3 , 0 , 0
  4852.2     .09       0  4971.6     .05       0  5026.1     .09       0
Bank Sta=4971.6,5026.1
Exp/Cntr=0.3,0.1

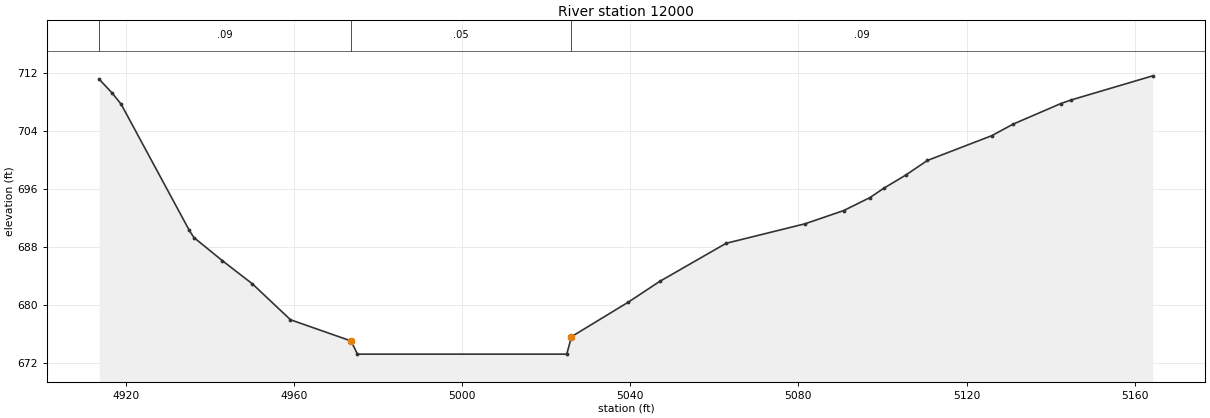
Type RM Length L Ch R = 1 ,12000   ,452,452,452
BEGIN DESCRIPTION:
Snow Creek 25.0
END DESCRIPTION:
XS GIS Cut Line= 3
      1664386.13        974324.6      1664334.38       974393.66
      1664252.86       974536.26
#Sta/Elev= 26
  4913.7  711.16  4916.8  709.24  4918.9  707.72  4935.1   690.3  4936.2  689.31
 4942.99   686.1 4950.13   682.9 4959.17  677.95 4973.58  675.02  4975.1   673.2
  5024.9   673.2 5026.02  675.61 5039.48  680.36 5046.99  683.24  5062.8  688.51
  5081.6  691.21  5090.8  693.04    5097  694.82  5100.3  696.11  5105.6  697.96
  5110.7  699.96    5126  703.38  5131.1  704.98  5142.4  707.81  5144.8   708.3
  5164.3  711.65
#Mann= 3 , 0 , 0
  4913.7     .09       0 4973.58     .05       0 5026.02     .09       0
Bank Sta=4973.58,5026.02
Exp/Cntr=0.3,0.1