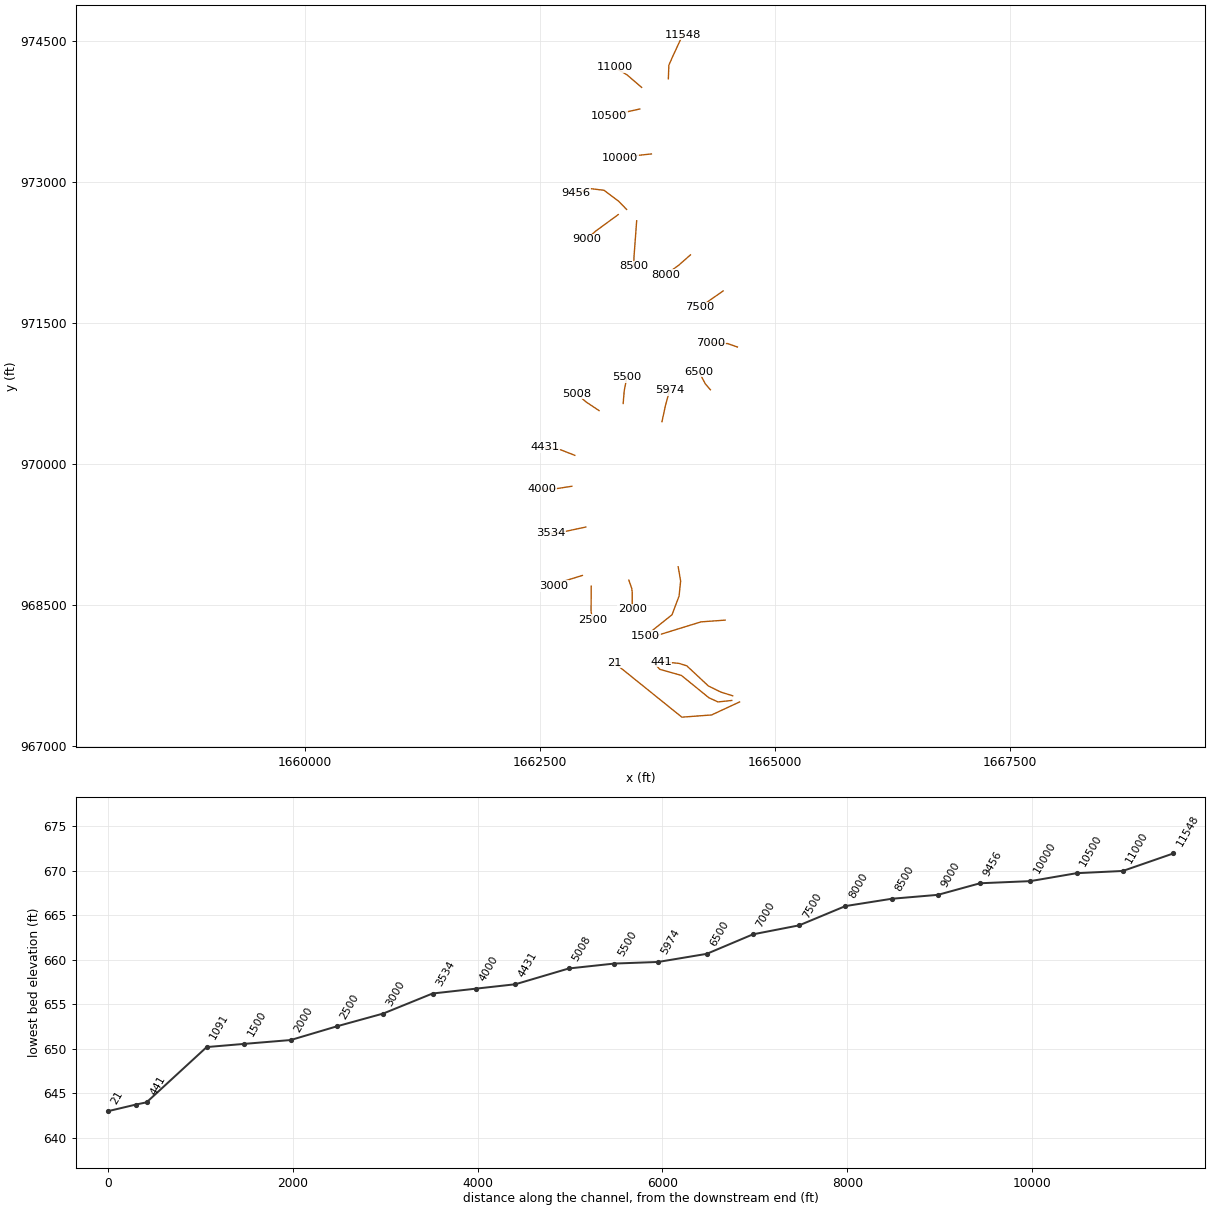
HEC-RAS study lds_snow_crk.prj: Snow Creek Limited Detail Study

--- lds_snow_crk.g02 (geometry) --- (continued)

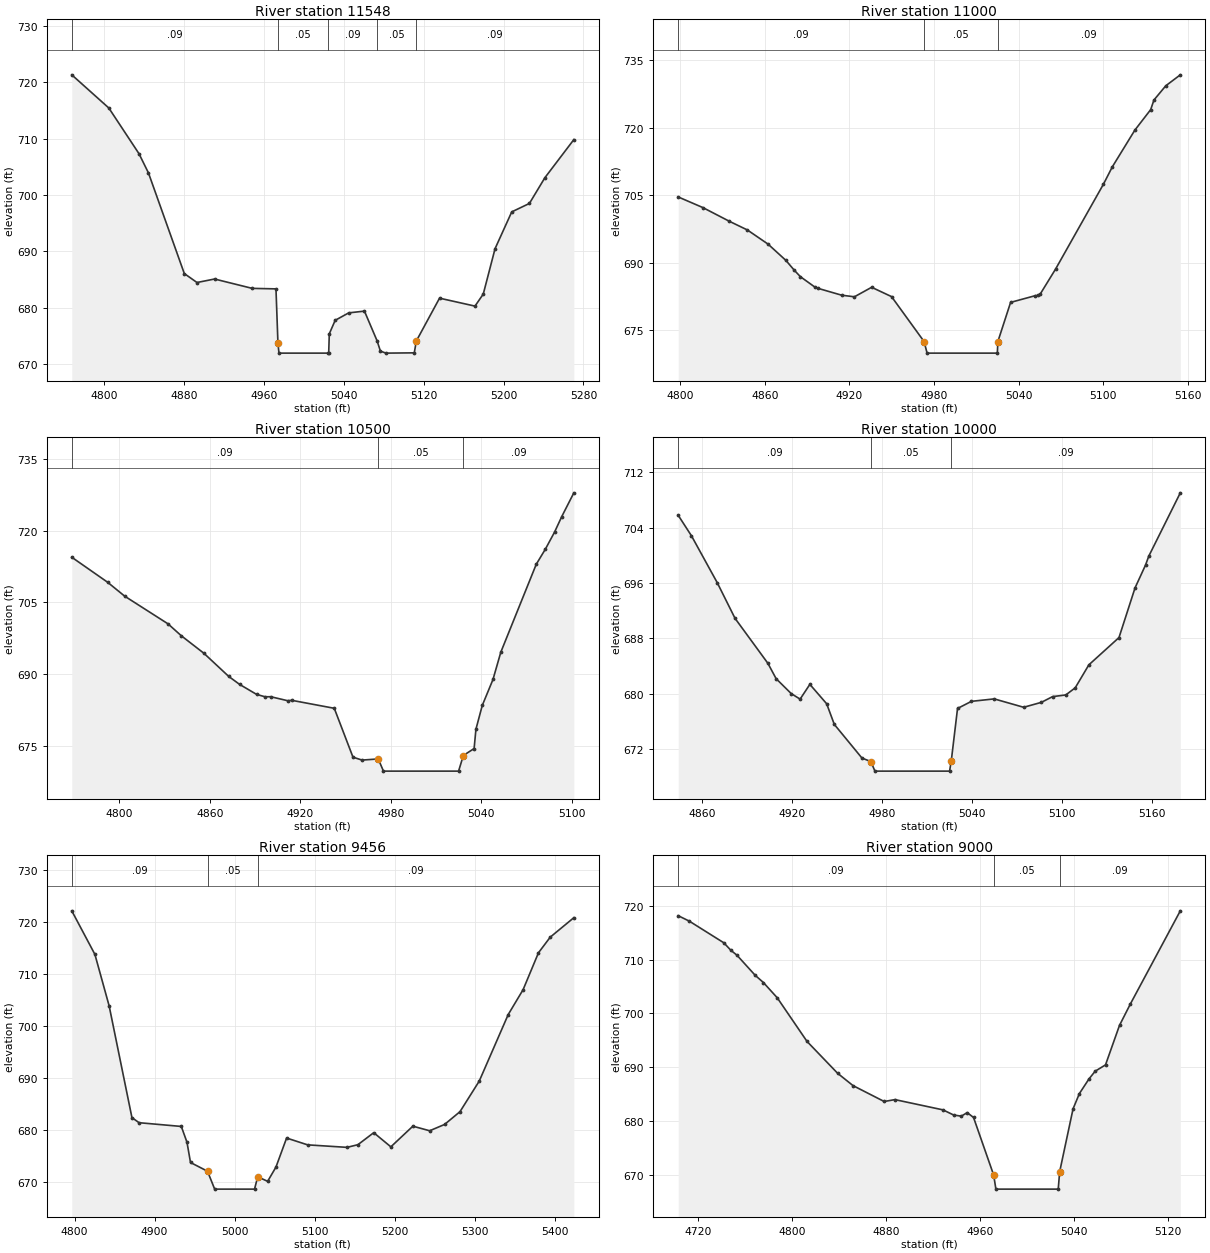
Type RM Length L Ch R = 1 ,11548   ,548,548,548
BEGIN DESCRIPTION:
Snow Creek 24.0
END DESCRIPTION:
XS GIS Cut Line= 4
      1663868.74       974102.49      1663873.97       974246.21
      1663910.55       974329.83      1664022.91       974572.85
#Sta/Elev= 30
  4767.6  721.35  4804.7  715.46  4834.9  707.35  4844.4  703.93  4880.3  686.06
    4893  684.47  4910.6  685.09  4948.3  683.43  4972.1  683.34 4974.08  673.67
  4975.1  671.93  5024.1  671.93  5024.9  671.93  5025.5  675.36  5031.4  677.76
 5044.98  679.08  5060.7  679.39  5073.3  674.14  5076.7  672.29  5082.2  671.93
  5110.6  671.98  5112.7   674.1  5135.9  681.69  5171.4  680.28  5179.7  682.42
  5191.5  690.48  5208.2  697.01  5225.9  698.51  5241.4  703.08  5270.4  709.85
#Mann= 5 ,-1 , 0
  4767.6     .09       0 4974.08     .05       0  5024.1     .09       0
  5073.3     .05       0  5112.7     .09       0
Bank Sta=4974.08,5112.7
Exp/Cntr=0.3,0.1

Type RM Length L Ch R = 1 ,11000   ,500,500,500
BEGIN DESCRIPTION:
Snow Creek 23.0
END DESCRIPTION:
XS GIS Cut Line= 3
      1663583.91       974011.03      1663431.23        974142.3
      1663299.09       974222.69
#Sta/Elev= 30
  4798.7  704.61  4816.2  702.25  4834.9  699.22  4847.7  697.29  4862.4  694.14
    4875  690.54    4881  688.34  4885.3  686.92  4895.4  684.65  4897.6  684.35
  4914.6  682.81  4923.6  682.46  4935.8  684.57  4949.9   682.5 4972.99  672.52
  4975.1  669.96  5024.9  669.96 5025.27  672.52  5034.3  681.22  5051.9  682.72
    5054  682.75  5055.3  683.07  5066.2  688.62  5100.1  707.44  5106.4  711.29
  5122.4  719.45  5133.6  723.99  5135.9  726.12  5144.3  729.28  5154.6  731.71
#Mann= 3 , 0 , 0
  4798.7     .09       0 4972.99     .05       0 5025.27     .09       0
Bank Sta=4972.99,5025.27
Exp/Cntr=0.3,0.1

Type RM Length L Ch R = 1 ,10500   ,500,500,500
BEGIN DESCRIPTION:
Snow Creek 22.0
END DESCRIPTION:
XS GIS Cut Line= 3
      1663565.62       973781.08      1663339.71       973730.69
       1663241.6        973705.3
#Sta/Elev= 30
  4768.5  714.47  4792.2  709.25  4803.6  706.32  4832.3  700.53  4841.1  698.04
  4856.1  694.37  4872.5  689.54  4879.7  687.87    4891  685.77  4896.6  685.27
  4900.4  685.28  4911.7  684.44  4914.3  684.53  4942.5  682.86  4954.9  672.63
 4960.92  672.02 4971.65  672.26  4975.1  669.71  5024.9  669.71 5028.05  672.98
  5035.2  674.44  5036.4  678.48  5040.6  683.46  5047.7  688.89  5052.9  694.61
  5076.4  713.01  5082.4  716.15  5088.5  719.72  5093.3  722.99  5101.3  727.95
#Mann= 3 , 0 , 0
  4768.5     .09       0 4971.65     .05       0 5028.05     .09       0
Bank Sta=4971.65,5028.05
Exp/Cntr=0.3,0.1

Type RM Length L Ch R = 1 ,10000   ,544,544,544
BEGIN DESCRIPTION:
Snow Creek 21.0
END DESCRIPTION:
XS GIS Cut Line= 3
      1663688.44       973302.89      1663533.25       973285.93
      1663356.58       973258.47
#Sta/Elev= 30
  4843.9  705.76  4852.7  702.81  4869.9  696.04  4881.8  690.88  4903.7  684.39
  4909.2  682.17  4919.3  680.01  4925.2  679.22  4931.7  681.35  4942.9  678.55
    4948  675.57 4966.44  670.71 4972.39   670.2  4975.1  668.82  5024.9  668.82
 5026.02  670.29  5030.2  677.87  5039.5   678.9  5054.7  679.25  5074.3  678.04
  5086.1  678.75  5093.6  679.58  5102.4  679.82  5108.7  680.85  5117.8  684.17
  5137.9  688.11  5148.6  695.28  5155.6  698.58  5157.8  699.88  5178.8  709.01
#Mann= 3 , 0 , 0
  4843.9     .09       0 4972.39     .05       0 5026.02     .09       0
Bank Sta=4972.39,5026.02
Exp/Cntr=0.3,0.1

Type RM Length L Ch R = 1 ,9456    ,456,456,456
BEGIN DESCRIPTION:
Snow Creek 20.0
END DESCRIPTION:
XS GIS Cut Line= 5
      1663424.52       972712.33       1663340.9       972798.57
      1663184.11       972916.15      1663032.56       972934.45
        1662881.       972887.41
#Sta/Elev= 30
  4796.5  722.08  4825.4  713.71  4843.2  703.81  4871.7  682.33  4880.6  681.35
  4933.4  680.63  4940.5  677.59  4944.9   673.7 4966.14  672.02  4975.1  668.58
  5024.9  668.58  5028.9  670.95  5041.3  670.08  5051.7  672.82    5065   678.4
  5091.3  677.09  5140.5  676.61  5154.1  677.12  5173.9  679.43  5195.3  676.71
  5222.8  680.68  5243.8   679.8  5262.4  681.01  5281.7  683.47  5305.8  689.36
    5342  702.15  5360.6  706.93  5379.8  714.02  5394.5  717.02    5424  720.76
#Mann= 3 , 0 , 0
  4796.5     .09       0 4966.14     .05       0  5028.9     .09       0
Bank Sta=4966.14,5028.9
Exp/Cntr=0.3,0.1

Type RM Length L Ch R = 1 ,9000    ,500,500,500
BEGIN DESCRIPTION:
Snow Creek 19.0
END DESCRIPTION:
XS GIS Cut Line= 3
      1663335.67       972657.46      1663096.26       972482.42
      1662998.59       972396.15
#Sta/Elev= 30
  4703.4   718.2  4712.8  717.19  4742.2  713.15  4748.1  711.77  4753.3  710.85
  4768.8  707.11  4775.8  705.76  4787.6  702.91  4812.9  694.79  4838.9  688.86
    4852  686.56  4878.5   683.6  4887.7  683.95  4928.5  682.04  4937.6  681.08
  4944.1  680.87  4949.1  681.53  4954.5  680.62  4971.6   669.9  4973.5  667.28
  5026.5  667.28 5027.71  670.51  5039.1  682.23  5044.5  685.08  5052.6  687.79
  5057.9  689.24  5066.7  690.42  5078.6  697.78  5087.9  701.79  5130.3  719.11
#Mann= 3 , 0 , 0
  4703.4     .09       0  4971.6     .05       0 5027.71     .09       0
Bank Sta=4971.6,5027.71
Exp/Cntr=0.3,0.1

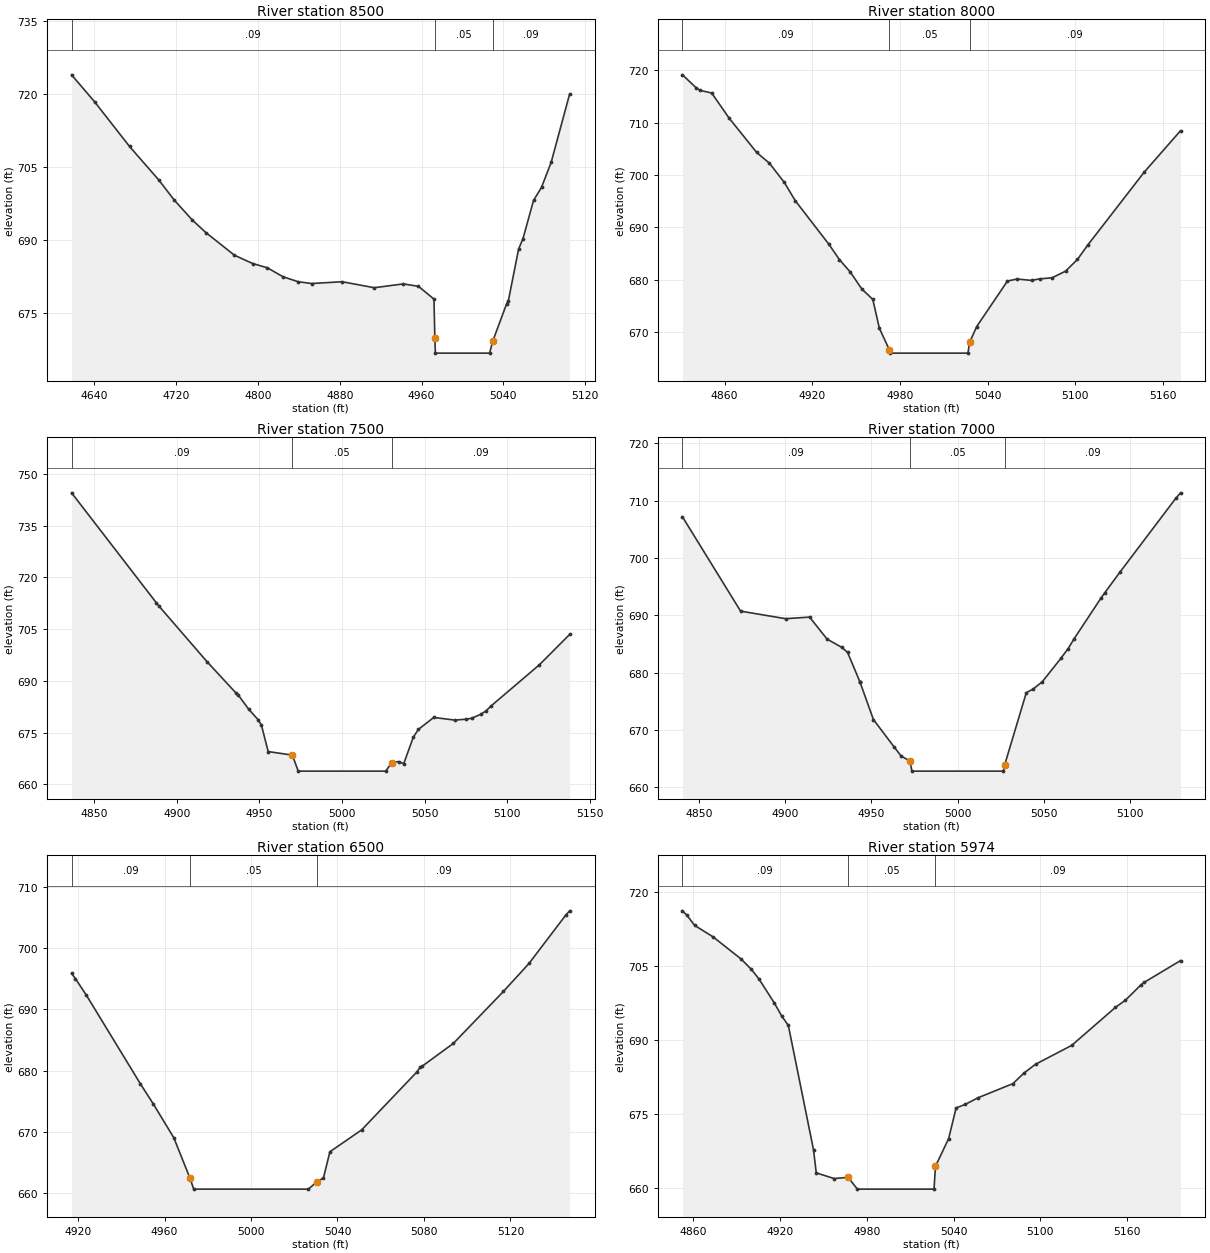
Type RM Length L Ch R = 1 ,8500    ,500,500,500
BEGIN DESCRIPTION:
Snow Creek 18.0
END DESCRIPTION:
XS GIS Cut Line= 3
      1663531.65       972592.13      1663503.38       972210.87
       1663500.3        972106.1
#Sta/Elev= 30
  4617.7  723.98  4640.5  718.37  4674.4  709.27    4703  702.39    4718  698.29
  4735.7  694.19    4749   691.6    4777  686.94  4794.8  685.24  4809.3  684.35
  4824.4  682.53  4839.3   681.5  4852.5  681.13  4882.3   681.5  4913.7  680.27
  4942.2  681.05  4956.9  680.56  4972.1  677.94 4972.99  669.88  4973.5  666.84
  5026.5  666.84 5029.59  669.29  5043.1  676.91  5044.9  677.61  5054.9  688.21
  5059.2  690.36  5069.5  698.19  5077.3  700.88  5086.7  705.99  5104.8  720.04
#Mann= 3 , 0 , 0
  4617.7     .09       0 4972.99     .05       0 5029.59     .09       0
Bank Sta=4972.99,5029.59
Exp/Cntr=0.3,0.1

Type RM Length L Ch R = 1 ,8000    ,500,500,500
BEGIN DESCRIPTION:
Snow Creek 17.0
END DESCRIPTION:
XS GIS Cut Line= 3
      1664103.92       972228.92      1663977.12       972117.44
      1663837.38       972017.26
#Sta/Elev= 30
  4831.2  719.13  4840.6  716.65  4843.2  716.17  4851.2  715.66  4863.2  710.84
    4882  704.31  4890.7  702.26  4900.9  698.59  4908.3  695.14  4931.3  686.82
  4938.6  683.86    4946   681.5  4953.8  678.29  4961.4  676.27  4965.9  670.77
  4972.8  666.62  4972.9  666.02  5026.5  666.02 5027.61  668.06  5032.5   671.1
  5053.5  679.77    5060  680.16    5070   679.9  5075.5  680.19    5084  680.39
  5093.3  681.67  5101.4   683.9  5108.3  686.59  5147.1  700.57  5171.9  708.46
#Mann= 3 , 0 , 0
  4831.2     .09       0  4972.8     .05       0 5027.61     .09       0
Bank Sta=4972.8,5027.61
Exp/Cntr=0.3,0.1

Type RM Length L Ch R = 1 ,7500    ,500,500,500
BEGIN DESCRIPTION:
Snow Creek 16.0
END DESCRIPTION:
XS GIS Cut Line= 3
      1664451.46       971844.79      1664316.67       971751.69
      1664205.83       971669.72
#Sta/Elev= 27
  4836.2  744.52  4887.6  712.62  4889.2  711.66  4918.2  695.61  4935.7  686.54
  4937.2  685.89  4943.5   681.8  4949.1  678.82  4951.2  677.19  4955.3  669.53
 4969.96   668.5  4973.5  663.86  5026.5  663.86 5030.09  666.29 5034.26  666.63
  5037.4  666.01  5043.2  673.69  5046.3  675.96  5055.6  679.42  5068.5  678.64
    5075  678.91  5078.5  679.17    5084  680.32  5087.3  681.33  5090.1  682.66
  5119.6  694.69  5137.9  703.47
#Mann= 3 , 0 , 0
  4836.2     .09       0 4969.96     .05       0 5030.09     .09       0
Bank Sta=4969.96,5030.09
Exp/Cntr=0.3,0.1

Type RM Length L Ch R = 1 ,7000    ,500,500,500
BEGIN DESCRIPTION:
Snow Creek 15.0
END DESCRIPTION:
XS GIS Cut Line= 4
      1664603.01       971249.01      1664498.49       971285.59
      1664449.74       971285.34       1664320.8       971293.43
#Sta/Elev= 28
  4840.5  707.18  4874.2  690.74  4900.3  689.42  4914.2   689.7  4924.3  685.87
  4932.8  684.43  4936.2  683.56  4943.3  678.46  4943.4  678.37  4943.5   678.3
  4951.2  671.84 4963.01  667.14 4967.18  665.51 4972.39  664.59  4973.5  662.85
  5026.5  662.85 5027.31  663.98  5039.8  676.51  5043.9  677.19    5049   678.4
  5059.8  682.49  5064.1  684.22  5067.5  685.91  5083.3   693.1  5085.2   693.9
  5094.3  697.62  5126.5  710.42  5129.2  711.36
#Mann= 3 , 0 , 0
  4840.5     .09       0 4972.39     .05       0 5027.31     .09       0
Bank Sta=4972.39,5027.31
Exp/Cntr=0.3,0.1

Type RM Length L Ch R = 1 ,6500    ,526,526,526
BEGIN DESCRIPTION:
Snow Creek 14.0
END DESCRIPTION:
XS GIS Cut Line= 3
      1664315.58       970794.34      1664261.64       970857.44
      1664192.76        970987.7
#Sta/Elev= 21
    4917  695.85  4918.8  694.99  4923.9  692.27  4948.8  677.86  4954.8  674.56
  4964.3  669.04 4971.75  662.47  4973.5  660.66  5026.5  660.66 5030.59  661.87
  5033.5  662.47  5036.5  666.75  5051.2  670.33  5076.7  679.76  5078.3  680.56
  5079.1  680.69  5093.6  684.43  5116.8  692.92  5128.6  697.47  5145.5  705.31
  5147.4  706.06
#Mann= 3 , 0 , 0
    4917     .09       0 4971.75     .05       0 5030.59     .09       0
Bank Sta=4971.75,5030.59
Exp/Cntr=0.3,0.1

Type RM Length L Ch R = 1 ,5974    ,474,474,474
BEGIN DESCRIPTION:
Snow Creek 13.0
END DESCRIPTION:
XS GIS Cut Line= 3
       1663800.8       970454.64      1663837.38       970624.49
      1663881.81       970789.11
#Sta/Elev= 30
  4852.6   716.2  4855.8  715.27    4861  713.25  4873.8  710.91  4893.1  706.44
  4900.3  704.31  4905.7  702.29  4916.2  697.47  4921.2  694.87  4925.8  692.95
  4943.2  667.73  4945.1  663.05  4957.4   661.9 4967.13  662.14  4973.5  659.75
  5026.5  659.75  5027.5  664.36  5036.6     670  5041.8  676.23  5048.2  676.95
  5056.9  678.28  5081.1  681.16  5088.7   683.3  5096.7  685.08  5121.7  688.91
  5151.9  696.61  5158.8  698.07  5169.5  701.16  5171.7  701.67  5196.9  706.11
#Mann= 3 , 0 , 0
  4852.6     .09       0 4967.13     .05       0  5027.5     .09       0
Bank Sta=4967.13,5027.5
Exp/Cntr=0.3,0.1

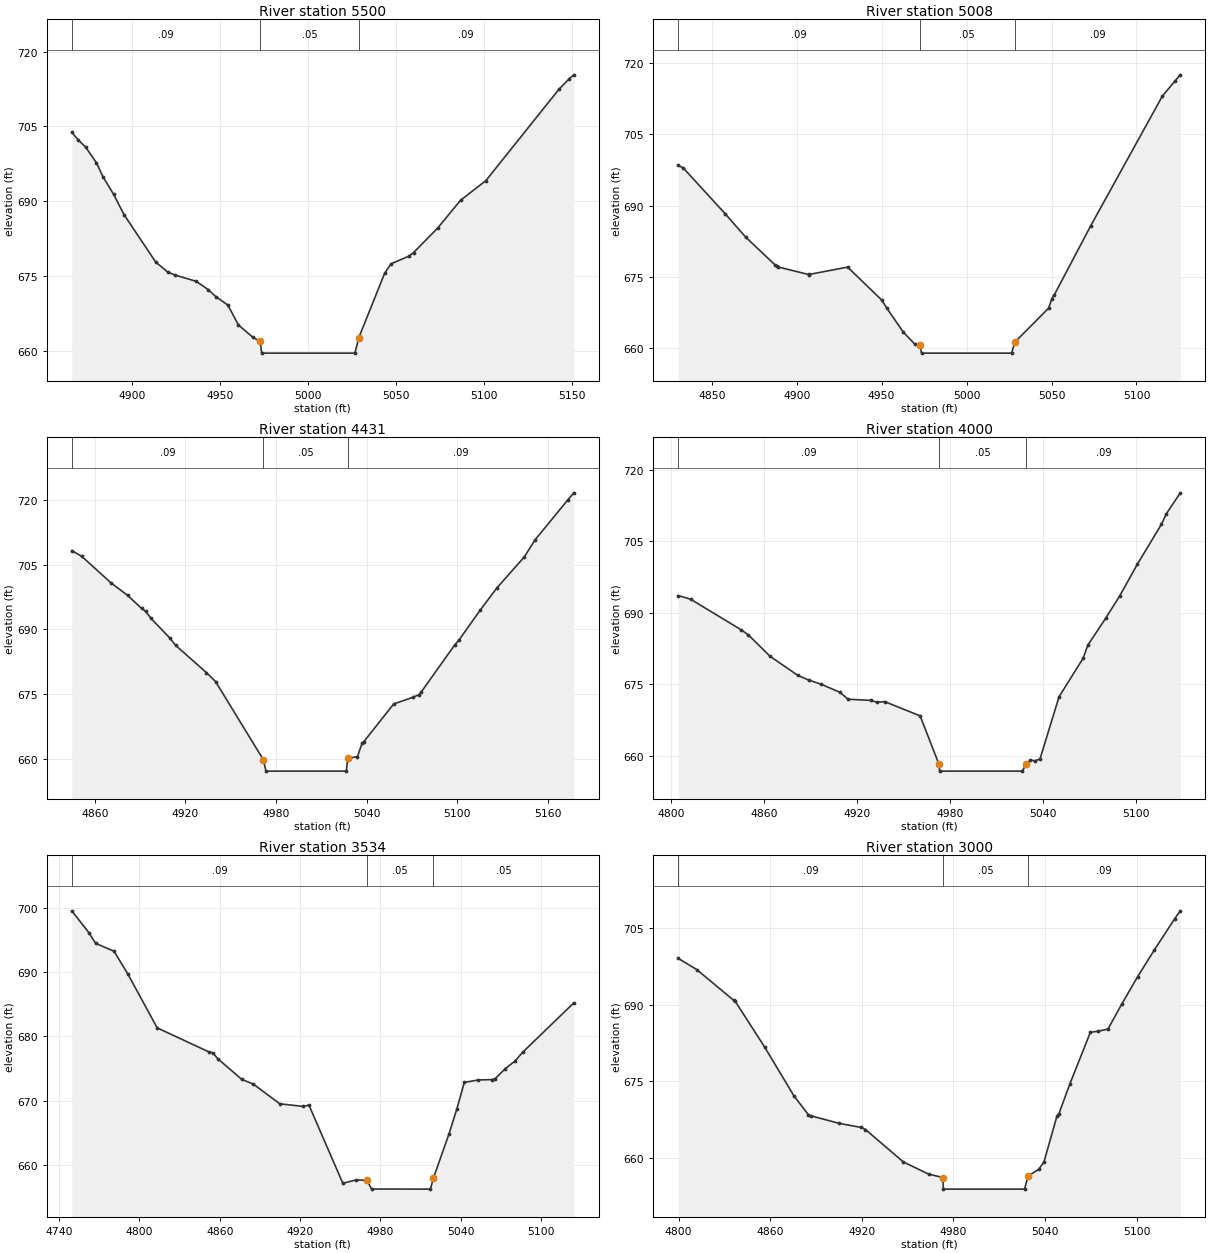
Type RM Length L Ch R = 1 ,5500    ,492,492,492
BEGIN DESCRIPTION:
Snow Creek 12.0
END DESCRIPTION:
XS GIS Cut Line= 3
      1663387.93         970648.      1663399.17       970781.98
      1663427.13       970930.22
#Sta/Elev= 30
  4865.6   703.8  4869.3  702.29  4873.5  700.84  4879.6  697.72  4883.3  694.92
  4889.4  691.37  4895.3  687.32  4913.3  677.81  4920.1  675.82  4924.5  675.19
  4936.3  673.96  4943.2  672.28  4947.4  670.91  4954.3   669.2  4960.3  665.21
 4968.52  662.74 4972.69   661.9  4973.5  659.57  5026.5  659.57 5028.65  662.62
  5043.4  675.58    5047  677.46  5057.3  679.02  5059.8  679.71  5073.5  684.62
  5086.5  690.19  5100.9  694.13  5142.4  712.42  5148.3  714.55  5150.9  715.33
#Mann= 3 , 0 , 0
  4865.6     .09       0 4972.69     .05       0 5028.65     .09       0
Bank Sta=4972.69,5028.65
Exp/Cntr=0.3,0.1

Type RM Length L Ch R = 1 ,5008    ,577,577,577
BEGIN DESCRIPTION:
Snow Creek 11.0
END DESCRIPTION:
XS GIS Cut Line= 3
      1663131.85       970572.22      1662990.75        970666.3
      1662896.68       970749.91
#Sta/Elev= 25
  4830.3  698.48  4833.3   697.9    4858  688.27  4869.9  683.42  4887.1  677.61
  4888.2  677.29  4889.2  677.11  4907.2  675.52  4907.5  675.56    4930  677.09
    4950  670.19    4953  668.51  4962.8  663.41  4969.4  660.97 4972.39  660.83
  4973.5  659.02  5026.5  659.02 5028.35  661.31  5048.3  668.47  5050.2  670.49
  5051.6  671.24  5073.1  685.79  5115.2  712.99  5122.5  716.12  5125.8  717.48
#Mann= 3 , 0 , 0
  4830.3     .09       0 4972.39     .05       0 5028.35     .09       0
Bank Sta=4972.39,5028.35
Exp/Cntr=0.3,0.1

Type RM Length L Ch R = 1 ,4431    ,431,431,431
BEGIN DESCRIPTION:
Snow Creek 10.0
END DESCRIPTION:
XS GIS Cut Line= 3
      1662873.16       970096.64      1662726.82       970154.13
      1662554.36       970185.49
#Sta/Elev= 30
  4844.8  708.22  4851.3  706.94  4871.1  700.68  4881.8  697.88  4891.1  694.85
  4893.7  694.21  4897.2  692.59  4909.6  688.07  4913.6  686.33  4933.9  680.05
    4940  677.97  4971.6  659.93  4973.4  657.25  5026.6  657.25 5027.61   660.2
    5034  660.62  5037.1  663.72  5038.2  664.05    5058  672.78  5070.8  674.32
  5074.9  674.96  5076.1  675.48  5098.5  686.47  5101.3  687.59  5115.3  694.48
  5126.5  699.68  5144.6  706.81  5151.4  710.63  5173.4     720  5177.3  721.59
#Mann= 3 , 0 , 0
  4844.8     .09       0  4971.6     .05       0 5027.61     .09       0
Bank Sta=4971.6,5027.61
Exp/Cntr=0.3,0.1

Type RM Length L Ch R = 1 ,4000    ,466,466,466
BEGIN DESCRIPTION:
Snow Creek 9.0
END DESCRIPTION:
XS GIS Cut Line= 3
       1662841.8        969767.4      1662648.95       969737.39
      1662520.39       969736.04
#Sta/Elev= 30
  4804.8   693.6  4812.8  692.84  4845.4  686.41    4850  685.36    4864  680.86
    4882  676.83  4888.9  675.87  4896.9     675    4909  673.31  4914.4  671.84
  4929.1   671.6  4932.7  671.23  4938.1  671.32  4960.8  668.35  4972.9  658.25
  4973.4  656.75  5026.6  656.75 5029.39  658.21 5031.83  659.05 5034.96  658.93
  5038.1   659.3  5050.4  672.36    5066  680.49  5068.9  683.16  5080.4  688.81
  5089.5  693.52  5100.9  700.19  5116.4  708.55  5119.6  710.78  5128.6  715.17
#Mann= 3 , 0 , 0
  4804.8     .09       0  4972.9     .05       0 5029.39     .09       0
Bank Sta=4972.9,5029.39
Exp/Cntr=0.3,0.1

Type RM Length L Ch R = 1 ,3534    ,534,534,534
BEGIN DESCRIPTION:
Snow Creek 8.0
END DESCRIPTION:
XS GIS Cut Line= 3
      1662990.75       969333.63      1662745.12       969281.36
       1662622.3       969265.69
#Sta/Elev= 30
  4749.5  699.55  4762.3  696.14  4767.3  694.49  4781.1  693.25  4791.3  689.73
  4813.3  681.32  4851.9  677.58  4854.9  677.44  4858.5  676.52  4876.4  673.31
  4885.1  672.56  4904.8   669.5  4922.4  669.09  4926.6   669.3  4951.9  657.12
 4961.87  657.65 4969.91  657.57  4973.4  656.23 5017.28  656.21 5019.51  657.91
  5031.2  664.83  5037.1  668.74  5042.6  672.83  5053.1  673.21  5063.3  673.27
  5065.7  673.42    5073  674.93  5080.7   676.2  5086.1  677.51  5124.4  685.22
#Mann= 3 , 0 , 0
  4749.5     .09       0 4969.91     .05       0 5019.51     .05       0
Bank Sta=4969.91,5019.51
Exp/Cntr=0.3,0.1

Type RM Length L Ch R = 1 ,3000    ,500,500,500
BEGIN DESCRIPTION:
Snow Creek 7.0
END DESCRIPTION:
XS GIS Cut Line= 3
      1662954.16       968818.85      1662762.94       968759.58
      1662645.82       968706.49
#Sta/Elev= 30
  4799.8  699.05  4811.9  696.87  4836.2  690.83  4837.1  690.67  4856.4  681.72
  4875.6  672.17  4885.1  668.48  4886.6  668.29  4905.1  666.82  4919.6  666.02
  4922.4  665.61  4947.2  659.28  4963.7   656.9 4973.24  656.22  4973.4  653.96
  5026.6  653.96 5028.85  656.53  5035.8   657.8  5039.3  659.26  5047.8  668.22
  5049.1  668.71  5056.3  674.54  5069.7  684.61  5074.5   684.8  5081.2  685.23
  5090.1  690.04  5100.6  695.45  5111.6   700.7  5124.9  706.79  5128.6  708.34
#Mann= 3 , 0 , 0
  4799.8     .09       0 4973.24     .05       0 5028.85     .09       0
Bank Sta=4973.24,5028.85
Exp/Cntr=0.3,0.1

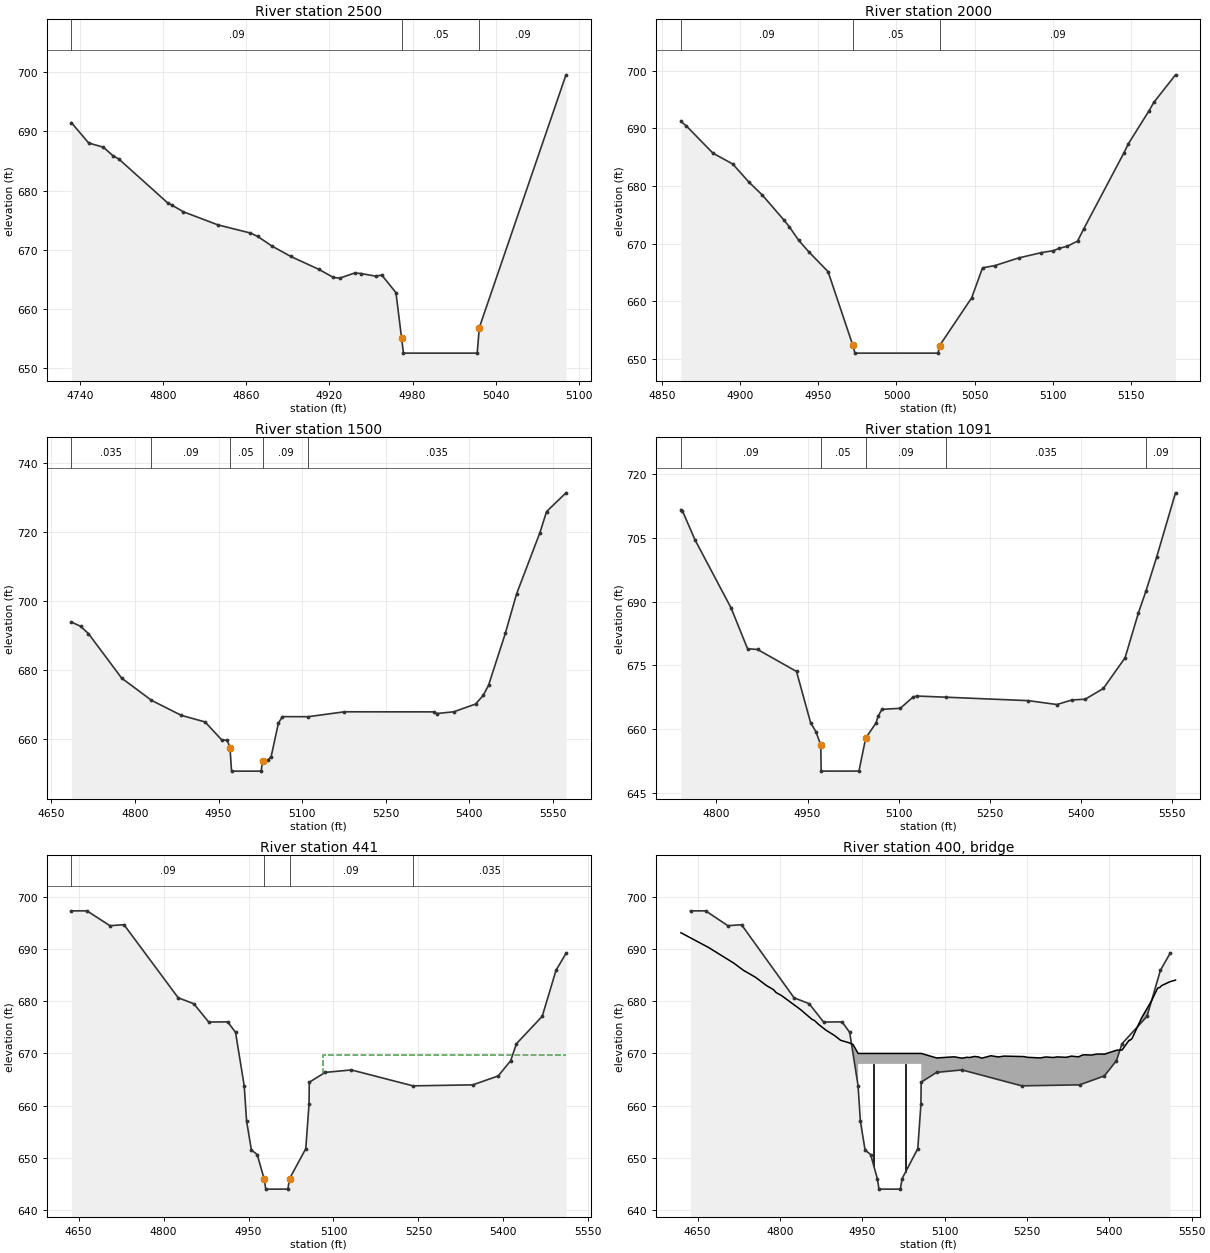
Type RM Length L Ch R = 1 ,2500    ,500,500,500
BEGIN DESCRIPTION:
Snow Creek 6.0
END DESCRIPTION:
XS GIS Cut Line= 3
      1663048.23       968703.87      1663046.38       968437.88
       1663061.3        968348.5
#Sta/Elev= 26
    4734  691.46  4746.5  688.02  4757.1  687.31  4764.1  685.85  4768.1  685.34
  4803.5  677.89  4806.3  677.56  4814.7  676.41  4839.8  674.18  4862.9  672.83
  4868.2  672.26  4878.5  670.63    4892  668.88  4912.6  666.66  4922.9  665.31
  4927.5   665.2  4938.3  666.07  4942.7  665.98  4953.4  665.53  4957.8  665.72
    4968  662.74  4972.1  655.02  4973.4  652.53  5026.6  652.53  5028.1  656.84
  5090.6  699.54
#Mann= 3 , 0 , 0
    4734     .09       0  4972.1     .05       0  5028.1     .09       0
Bank Sta=4972.1,5028.1
Exp/Cntr=0.3,0.1

Type RM Length L Ch R = 1 ,2000    ,500,500,500
BEGIN DESCRIPTION:
Snow Creek 5.0
END DESCRIPTION:
XS GIS Cut Line= 4
      1663448.03        968769.2      1663479.39       968680.36
      1663484.68       968636.88      1663484.62       968458.24
#Sta/Elev= 30
    4862  691.21  4865.4  690.46  4882.5  685.71  4895.2  683.82  4905.5  680.69
  4913.9   678.5  4928.2  674.02  4931.5  672.89  4937.4  670.58  4943.8   668.6
  4956.2  665.14    4972  652.38  4973.4  650.99  5026.6  650.99 5027.61   652.3
  5048.1  660.58  5055.1   665.8    5063  666.19  5078.1  667.51  5092.4  668.42
  5100.5  668.79  5103.9  669.16  5109.3  669.55  5115.9  670.44  5119.8  672.54
  5145.6  685.77  5148.5  687.38  5161.6  693.04  5164.7  694.52  5178.6  699.31
#Mann= 3 , 0 , 0
    4862     .09       0    4972     .05       0 5027.61     .09       0
Bank Sta=4972,5027.61
Exp/Cntr=0.3,0.1

Type RM Length L Ch R = 1 ,1500    ,409,409,409
BEGIN DESCRIPTION:
Snow Creek 4.0
END DESCRIPTION:
XS GIS Cut Line= 5
      1663973.26       968910.31      1663999.39       968758.75
      1663982.63       968599.18      1663907.94       968400.76
        1663625.         968175.
#Sta/Elev= 30
  4685.8  693.82  4702.2  692.62  4716.4  690.48  4776.1  677.55  4829.6  671.12
  4882.9  666.77  4925.9  664.83 4955.37  659.69 4965.83  659.48  4970.6  657.32
  4973.4  650.56  5026.6  650.56    5029  653.44 5038.93  653.78  5044.5  654.77
  5057.6  664.54  5064.9  666.38  5111.2  666.36    5176  667.78  5337.4  667.76
  5342.3  667.28  5372.6  667.79  5411.7  670.04  5425.4  672.55  5434.9  675.48
    5465  690.53  5485.4  702.07    5527   719.7  5539.1  725.89    5574  731.34
#Mann= 5 ,-1 , 0
  4685.8    .035       0  4829.6     .09       0  4970.6     .05       0
    5029     .09       0  5111.2    .035       0
Bank Sta=4970.6,5029
Exp/Cntr=0.3,0.1

Type RM Length L Ch R = 1 ,1091    ,650,650,650
BEGIN DESCRIPTION:
Snow Creek 3.0
END DESCRIPTION:
XS GIS Cut Line= 3
      1664472.36       968343.27      1664216.28       968324.98
      1663683.21       968160.35
#Sta/Elev= 30
  4741.5  711.54  4743.8  711.35  4764.6  704.51  4824.2  688.47  4851.3  678.91
  4867.8  678.75  4931.9  673.59 4955.07  661.58 4963.97  659.43  4971.9  656.26
  4972.5   650.2  5034.7  650.21  5045.9  657.98 5062.81  661.49 5066.26  663.08
  5072.6   664.7  5102.8  664.94  5124.2  667.63  5130.3  667.82  5178.1  667.55
  5313.8  666.74  5360.8  665.83  5385.5   666.9  5407.4  667.08  5437.3   669.6
    5473   676.8    5495  687.33  5507.5  692.49  5524.9  700.35  5556.1  715.51
#Mann= 5 ,-1 , 0
  4741.5     .09       0  4971.9     .05       0  5045.9     .09       0
  5178.1    .035       0  5507.5     .09       0
Bank Sta=4971.9,5045.9
Exp/Cntr=0.5,0.3

Type RM Length L Ch R = 1 ,441     ,115,115,115
BEGIN DESCRIPTION:
Pitzer Rd. SR-1697 - US
END DESCRIPTION:
XS GIS Cut Line= 6
      1664553.37       967538.44      1664427.94       967577.64
      1664294.67       967642.96      1664064.72       967857.24
       1663981.1       967883.37      1663790.35       967901.66
#Sta/Elev= 30
  4637.2  697.33  4664.8  697.32  4705.2  694.48  4730.1  694.67  4825.8  680.67
  4853.3  679.53  4879.7  676.02  4913.2  676.05  4927.1  674.05  4942.4   663.8
 4946.59  657.04 4955.14  651.49 4965.31  650.63  4977.5     646  4980.5     644
  5019.5     644  5022.5     646 5051.19  651.77 5056.89  660.31 5057.31  664.48
  5085.4  666.37  5131.7  666.84  5240.5  663.79    5346  663.98    5391  665.69
    5413  668.61  5423.2  671.87  5468.7  677.11  5493.1  685.93  5510.7  689.18
#Mann= 4 ,-1 , 0
  4637.2     .09       0  4977.5     .05       0  5022.5     .09       0
  5240.5    .035       0
#XS Ineff= 2 , 0
       0  4918.5  669.99  5081.5       0  669.77
Permanent Ineff=
       F       F
Bank Sta=4977.5,5022.5
Exp/Cntr=0.5,0.3

Type RM Length L Ch R = 3 ,400     ,,,
BEGIN DESCRIPTION:
Pitzer Rd. SR-1697
Structure ID: Pitzer Rd. SR-1697
Approximate Survey Structure
END DESCRIPTION:
Bridge Culvert--1,0,-1,-1, 0
Deck Dist Width WeirC Skew NumUp NumDn MinLoCord MaxHiCord MaxSubmerge Is_Ogee
32,24,3,0, 60, 60, , , , 0, 1,1,,
  4619.7  4669.8  4716.1  4733.5  4755.8  4775.7  4788.5    4793  4802.7  4837.6
  4858.7  4862.9  4870.4  4883.9  4899.7  4910.6  4926.7  4933.2  4942.5  4942.5
  5057.5  5057.5  5085.6  5117.2  5131.8  5140.9  5145.9  5154.1  5160.7  5167.8
  5184.4    5198  5208.3    5245  5250.7  5274.2  5284.4  5298.2  5304.9  5321.6
  5330.8  5343.9  5350.6  5354.6  5367.7  5376.8  5388.6  5389.8  5413.6  5423.2
  5436.2  5437.4  5441.5  5458.8  5477.3    5488  5492.1  5495.2    5510  5520.6
  693.13  690.32   687.3  685.94  684.58     683  682.21  681.67  681.11  678.41
  676.51  676.32  675.57  674.46  673.42  672.52  672.02  671.71     670     670
     670     670  669.13  669.36  669.09  669.27  669.22  669.42  669.36   669.1
  669.56  669.33  669.49   669.4  669.26  669.14  669.33  669.22  669.34  669.26
  669.49  669.35  669.68  669.74  669.69  669.87   669.9  669.82  670.63  670.65
  672.54   672.5  672.87  676.81  680.16  682.51  682.65  682.99  683.73  684.06
     624     624     624     624     624     624     624     624     624     624
     624     624     624     624     624     624     624     624     624     668
     668     624     624     624     624     624     624     624     624     624
     624     624     624     624     624     624     624     624     624     624
     624     624     624     624     624     624     624     624     624     624
     624     624     624     624     624     624     624     624     624     624
  4619.7  4669.8  4716.1  4733.5  4755.8  4775.7  4788.5    4793  4802.7  4837.6
  4858.7  4862.9  4870.4  4883.9  4899.7  4910.6  4926.7  4933.2  4942.5  4942.5
  5057.5  5057.5  5085.6  5117.2  5131.8  5140.9  5145.9  5154.1  5160.7  5167.8
  5184.4    5198  5208.3    5245  5250.7  5274.2  5284.4  5298.2  5304.9  5321.6
  5330.8  5343.9  5350.6  5354.6  5367.7  5376.8  5388.6  5389.8  5413.6  5423.2
  5436.2  5437.4  5441.5  5458.8  5477.3    5488  5492.1  5495.2    5510  5520.6
  693.13  690.32   687.3  685.94  684.58     683  682.21  681.67  681.11  678.41
  676.51  676.32  675.57  674.46  673.42  672.52  672.02  671.71     670     670
     670     670  669.13  669.36  669.09  669.27  669.22  669.42  669.36   669.1
  669.56  669.33  669.49   669.4  669.26  669.14  669.33  669.22  669.34  669.26
  669.49  669.35  669.68  669.74  669.69  669.87   669.9  669.82  670.63  670.65
  672.54   672.5  672.87  676.81  680.16  682.51  682.65  682.99  683.73  684.06
     624     624     624     624     624     624     624     624     624     624
     624     624     624     624     624     624     624     624     624     668
     668     624     624     624     624     624     624     624     624     624
     624     624     624     624     624     624     624     624     624     624
     624     624     624     624     624     624     624     624     624     624
     624     624     624     624     624     624     624     624     624     624
Pier Skew, UpSta & Num, DnSta & Num=  ,4971.3, 2 ,4971.3, 2 , 0 , 0 , 0 ,0,0
       2       2
  650.31     668
       2       2
  649.67     668
Pier Skew, UpSta & Num, DnSta & Num=  ,5028.8, 2 ,5028.8, 2 , 0 , 0 , 0 ,0,0
       2       2
  648.95     668
       2       2
  648.62     668
Abutment Skew #Up #Dn= , 2 , 2
  4942.5    4957
     666  652.31
  4942.5    4957
     666  650.32
Abutment Skew #Up #Dn= , 2 , 2
    5043  5057.5
  651.44     666
    5043  5057.5
  652.94     666
BR Coef= 1 , 1 , 0 ,1.25, 0 ,,,0.8,0,2,0,
WSPro=,,,, 1 ,,,, 0 ,,,, 0 ,,,,-1 ,-1 ,-1 , 0 , 0 , 0 , 0 , 0
BC Design=,, 0 ,, 0 ,,,,,,
BC HTab HWMax=697.33

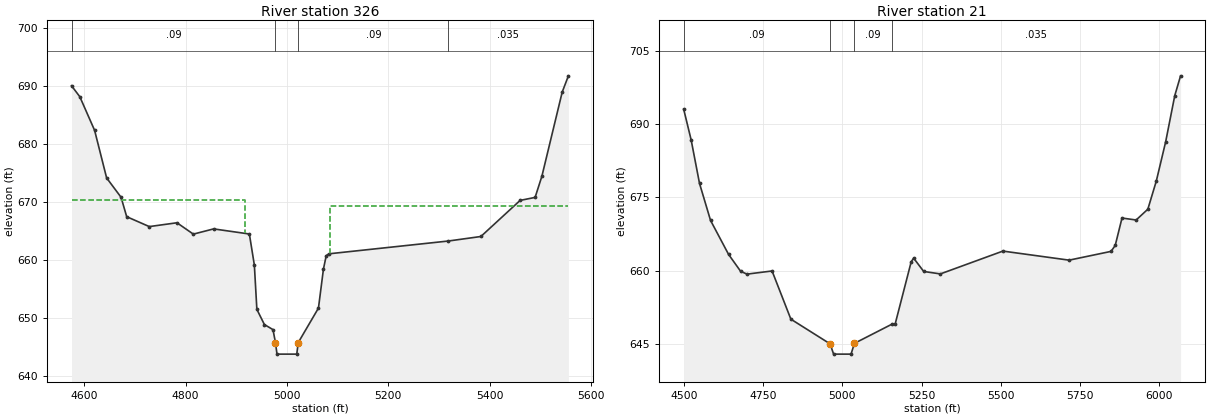
Type RM Length L Ch R = 1 ,326     ,305,305,305
BEGIN DESCRIPTION:
Pitzer Rd. SR-1697 - DS
END DESCRIPTION:
XS GIS Cut Line= 6
      1664542.91       967488.79      1664396.58       967473.11
       1664299.9       967517.54      1664007.23       967755.33
      1663777.35       967820.05      1663705.75       967899.37
#Sta/Elev= 30
    4575  690.09  4591.4  688.19  4620.6  682.38  4644.3  674.17  4672.8  670.83
  4683.9  667.48  4728.5  665.77  4783.1  666.43  4815.4  664.47  4855.5  665.37
    4926  664.49 4935.84  659.13 4940.79  651.48 4955.63  648.86 4972.59  647.98
  4977.5  645.75  4980.5  643.75  5019.5  643.75  5022.5  645.75 5062.34   651.7
 5072.24  658.47  5077.7  660.75  5082.9  661.07  5318.8  663.28  5382.9  664.06
  5460.3  670.29  5489.9  670.81  5503.3  674.47  5543.4     689  5555.6   691.8
#Mann= 4 ,-1 , 0
    4575     .09       0  4977.5     .06       0  5022.5     .09       0
  5318.8    .035       0
#XS Ineff= 2 , 0
       0 4918.25  670.37  5084.6       0  669.32
Permanent Ineff=
       F       F
Bank Sta=4977.5,5022.5
Exp/Cntr=0.5,0.3

Type RM Length L Ch R = 1 ,21      ,0,0,0
BEGIN DESCRIPTION:
Snow Creek 1.0
END DESCRIPTION:
XS GIS Cut Line= 4
      1664626.53       967473.11      1664328.64       967334.62
      1664012.46        967311.1      1663294.19       967889.57
#Sta/Elev= 30
  4499.4  693.02  4522.9  686.76  4549.4  677.85  4584.2   670.3  4641.1  663.36
  4679.1  659.91  4699.3  659.34  4778.3  659.98  4837.6  650.14 4961.27   645.1
  4972.5     643  5027.5     643 5038.13   645.2  5156.3  649.11  5166.6  649.13
  5217.3  661.86    5225   662.6  5256.7  659.88  5309.3  659.38  5506.6  664.04
  5715.6  662.19  5847.8  663.98    5861  665.19  5882.4  670.79    5927  670.39
  5963.9  672.59  5990.6  678.33  6020.1  686.34  6048.9  695.79  6067.2  699.83
#Mann= 4 ,-1 , 0
  4499.4     .09       0 4961.27     .05       0 5038.13     .09       0
  5156.3    .035       0
Bank Sta=4961.27,5038.13
Exp/Cntr=0.3,0.1

Chan Stop Cuts=-1
Use User Specified Reach Order=0
User Specified Reach Order=Snow Creek      ,Reach-1